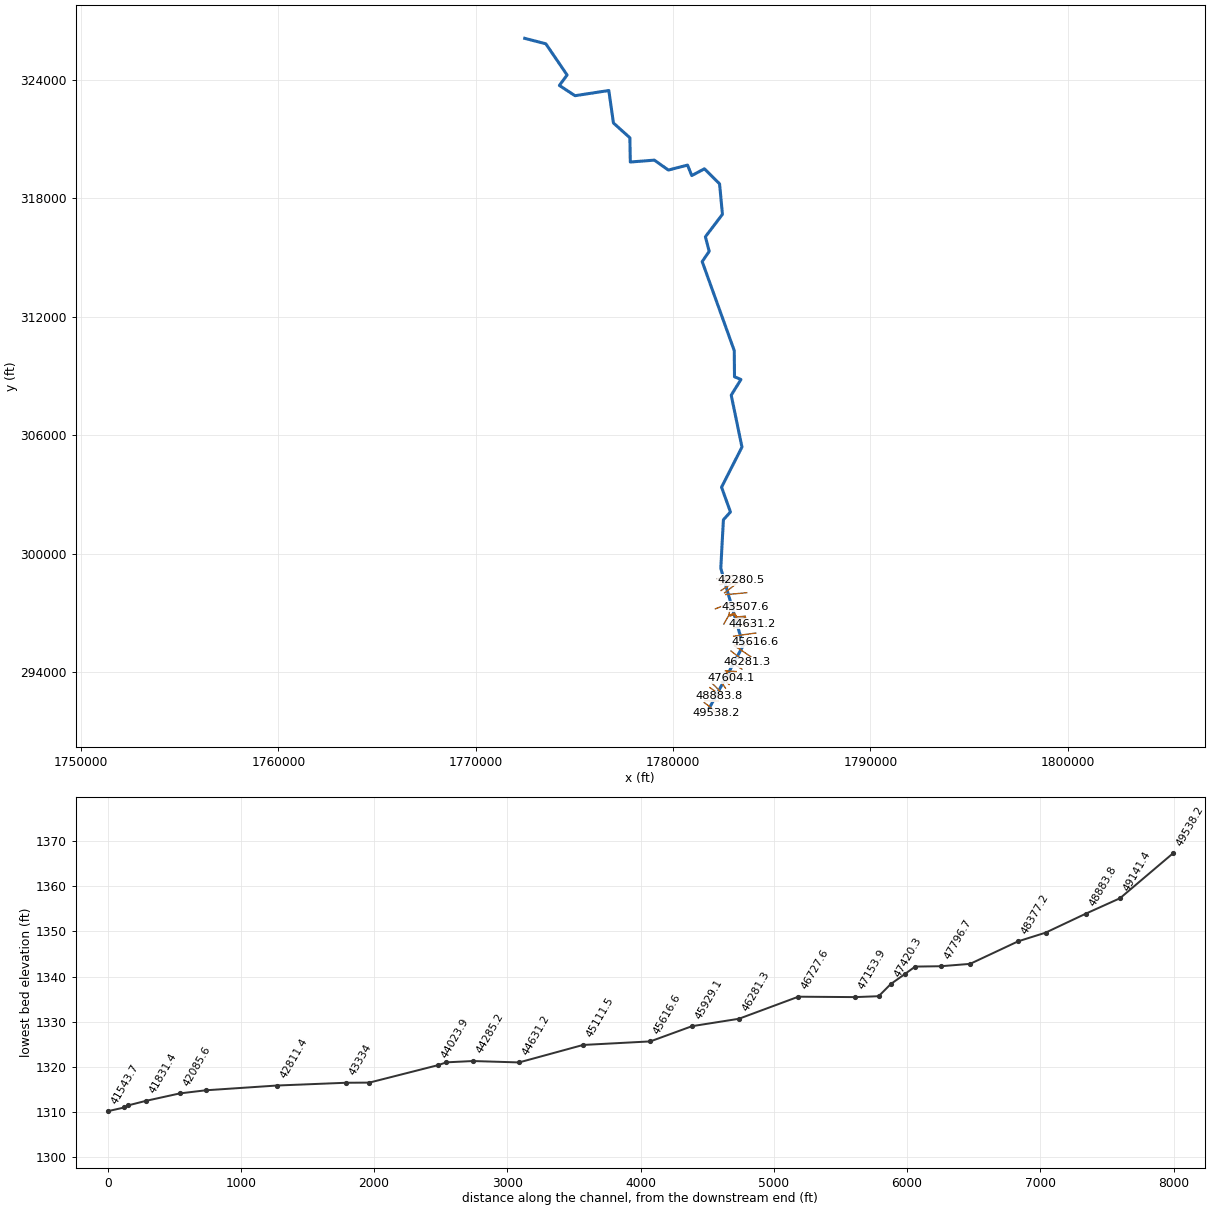
--- HusteadFrk.prj (project) ---

Proj Title=HusteadFrk
Current Plan=p01
Default Exp/Contr=0,0
English Units
Geom File=g01
Flow File=f01
Plan File=p01
BEGIN DESCRIPTION:
END DESCRIPTION:
DSS Export Rating Curves= 0
DSS Export Rating Curve Sorted= 0
DSS Export Volume Flow Curves= 0
DXF OffsetX= 0
DXF OffsetY= 0
DXF ScaleX= 0
DXF ScaleY= 0

--- HusteadFrk.p01 (plan) ---

Plan Title=Floodplain
Program Version=4.00
Geom File=g01
Flow File=f01
K Sum by GR=0
Std Step Tol=0.01
Critical Tol=0.01
Num of Std Step Trials=20
Max Error Tol=0.3
Flow Tol Ratio=0.001
Split Flow NTrial=30
Split Flow Tol=0.02
Split Flow Ratio=0.02
Log Output Level=0
Friction Slope Method=1
Unsteady Friction Slope Method=2
Unsteady Bridges Friction Slope Method=1
Global Log Level=0
CheckData=False
Run HTab=0
Run UNet=0
Run PostProcess=0
UNET Theta=0
UNET Theta Warmup=0
UNET ZTol=0
UNET ZSATol=0
UNET MxIter=0
UNET MaxInSteps=0
UNET DtIC=0
UNET DtMin=0
UNET MaxCRTS=0
UNET WFStab=0
UNET SFStab=0
UNET WFX=0
UNET SFX=0
UNET DSS MLevel=0
UNET DZMax Abort=0
UNET Convert EG Bridges=0
UNET Use Existing IB Tables=0
UNET Froude Limit=0
UNET Froude Power=0
Write IC File=0
Echo Input=False
Echo Output=False
Write Detailed=0

--- HusteadFrk.f01 (steady flow) ---

Flow Title=NFF Regression Equation
Program Version=4.00
Number of Profiles=1
Profile Names=P100yr
River Rch & RM=HusteadFrk,Main      ,49538.2
     166
River Rch & RM=HusteadFrk,Main      ,45929.1
     302
River Rch & RM=HusteadFrk,Main      ,45616.6
     440
River Rch & RM=HusteadFrk,Main      ,43507.6
     491
River Rch & RM=HusteadFrk,Main      ,43334
     707
River Rch & RM=HusteadFrk,Main      ,40692.9
     796
River Rch & RM=HusteadFrk,Main      ,39357.9
     874
River Rch & RM=HusteadFrk,Main      ,38564.5
     895
River Rch & RM=HusteadFrk,Main      ,35535.2
     993
River Rch & RM=HusteadFrk,Main      ,32925
    1102
River Rch & RM=HusteadFrk,Main      ,30026.5
    1197
River Rch & RM=HusteadFrk,Main      ,26365.5
    1259
River Rch & RM=HusteadFrk,Main      ,24026.1
    1321
River Rch & RM=HusteadFrk,Main      ,23709.7
    1545
River Rch & RM=HusteadFrk,Main      ,19999.9
    1637
River Rch & RM=HusteadFrk,Main      ,19168.3
    1809
River Rch & RM=HusteadFrk,Main      ,18917.9
    2767
River Rch & RM=HusteadFrk,Main      ,16184.5
    3036
River Rch & RM=HusteadFrk,Main      ,8909.1
    3355
River Rch & RM=HusteadFrk,Main      ,71.4
    3725
Boundary for River Rch & Prof#=HusteadFrk,Main      ,1
Up Type=0
Dn Type=3
Dn Slope=0.003599

--- HusteadFrk.g01 (geometry) ---

Geom Title=USGS 10m DEM
Program Version=4.10

River Reach=HusteadFrk      ,Main
Reach XY= 30
      1781829.23      292188.481     1783550.114      295363.909
     1782414.941      299274.178     1782547.041       301732.92
     1782904.458      302128.006     1782453.468      303381.643
     1783488.092      305414.716     1782943.014      308041.471
     1783435.574      308833.961     1783109.654       308974.86
     1783096.977      310300.288     1781472.095      314805.319
     1781828.507      315324.948      1781634.67      316061.754
     1782498.853       317198.27     1782352.623      318743.026
     1781585.425      319502.643     1780944.046      319160.742
     1780730.551      319690.562     1779760.311      319440.099
     1779047.871      319941.753     1777830.504       319847.39
      1777808.36      321073.108     1776975.889      321824.263
     1776740.992      323467.763     1775027.545      323204.505
     1774237.257      323724.827     1774627.642      324253.103
     1773551.119      325831.656      1772482.32      326109.416

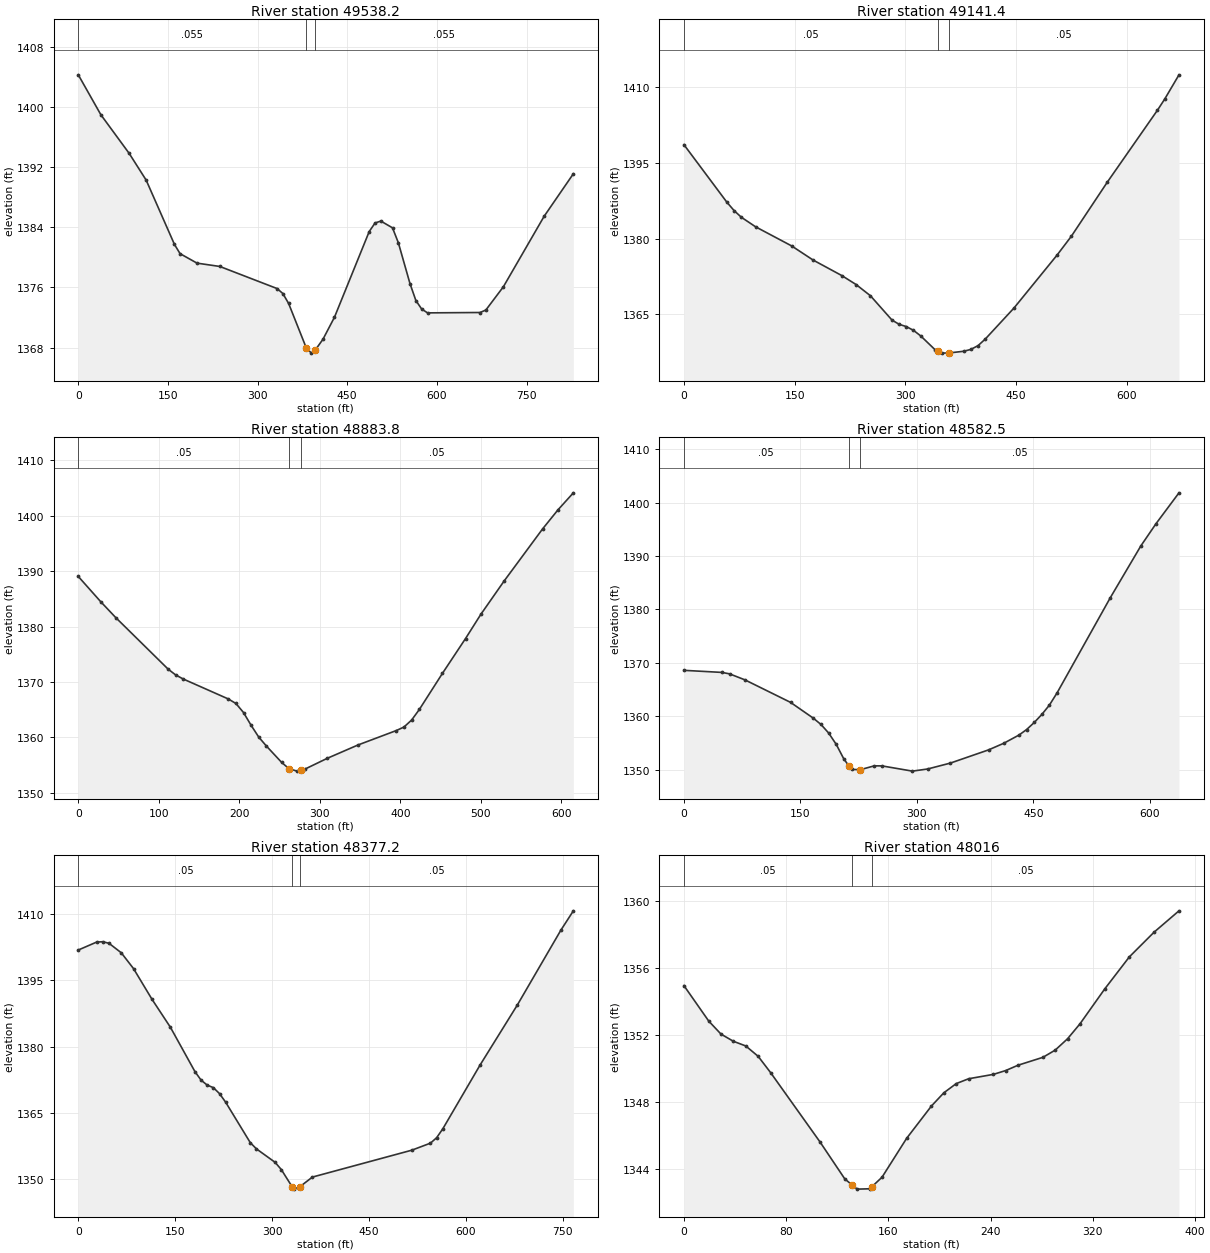
Type RM Length L Ch R = 1 ,49538.2 ,379.2,396.9,413.8
XS GIS Cut Line= 4
     1781574.639      292475.526     1781751.636      292348.902
     1781925.248       292197.86     1782195.732      291929.953
#Sta/Elev= 30
       0 1404.26    37.8 1398.95    85.2 1393.81   113.6 1390.26   160.9 1381.72
   170.3 1380.49   198.7 1379.23   236.8 1378.79   332.7 1375.85   342.3 1375.19
   351.9 1373.88   381.6 1367.94   390.2 1367.27   396.6 1367.69   409.4 1369.11
   428.6 1372.03   486.8 1383.43   496.6 1384.57   506.3 1384.82   525.8 1383.92
   535.6 1381.93   555.1 1376.49   564.9 1374.26   574.6 1373.13   584.4 1372.62
   672.3 1372.67     682    1373   711.3 1376.09   779.6 1385.47   828.4 1391.11
#Mann= 3 , 0 , 0
       0    .055       0   381.6    .045       0   396.6    .055       0
Bank Sta=381.6,396.6
XS Rating Curve= 0 ,0
Exp/Cntr=0.3,0.1

Type RM Length L Ch R = 1 ,49141.4 ,260.1,257.6,255
XS GIS Cut Line= 2
     1781620.211      292569.276     1782290.784      292556.255
#Sta/Elev= 30
       0 1398.66    58.3 1387.23      68 1385.59    77.8 1384.27    97.2 1382.37
   145.8  1378.6     175 1375.79   213.8 1372.72   233.3 1370.93   252.7 1368.71
   281.9 1363.89   291.6 1363.05   301.3  1362.6     311 1361.86   320.8 1360.75
   340.2 1358.02   344.4 1357.73   349.9 1357.34   359.4 1357.38   379.1 1357.71
   388.8 1358.08   398.5 1358.83   408.2 1360.12   447.1 1366.27   505.4 1376.75
   524.9 1380.51   573.5 1391.21   641.5 1405.48   651.3 1407.68   670.7  1412.5
#Mann= 3 , 0 , 0
       0     .05       0   344.4    .045       0   359.4     .05       0
Bank Sta=344.4,359.4
XS Rating Curve= 0 ,0
Exp/Cntr=0.3,0.1

Type RM Length L Ch R = 1 ,48883.8 ,312.3,301.3,290.2
XS GIS Cut Line= 4
     1781716.566      292857.688     1781881.845       292831.54
     1782088.442      292803.763     1782326.809      292784.771
#Sta/Elev= 30
       0 1389.05    27.9 1384.49    46.5 1381.63   111.6 1372.32   120.8 1371.29
   130.2 1370.55   186.3 1366.94   195.8 1366.12   205.2 1364.49   214.7 1362.17
   224.2 1360.04   233.7 1358.43   252.6 1355.48   261.6 1354.36   271.6 1353.91
   276.6 1354.09     281 1354.24   309.5 1356.24   347.4 1358.63   394.9 1361.23
   404.5 1361.87     414 1363.13   423.6 1365.04   452.3 1371.56     481 1377.85
   500.1 1382.24   528.8 1388.21   576.6 1397.62   595.8 1401.08   614.9 1404.15
#Mann= 3 , 0 , 0
       0     .05       0   261.6    .045       0   276.6     .05       0
Bank Sta=261.6,276.6
XS Rating Curve= 0 ,0
Exp/Cntr=0.3,0.1

Type RM Length L Ch R = 1 ,48582.5 ,209,205.3,200.8
XS GIS Cut Line= 2
     1781861.242      293235.581     1782382.943      292869.262
#Sta/Elev= 30
       0 1368.59      49  1368.2    58.8 1367.93    78.5 1366.81   137.3 1362.59
   166.7 1359.62   176.5 1358.45   186.3 1356.86   196.1 1354.73     206 1351.97
   212.1 1350.76   215.8 1350.03   227.1 1349.98   245.2  1350.7     255 1350.69
   294.2 1349.71   313.8 1350.11   343.2 1351.22   392.3 1353.69   411.9 1354.93
   431.5 1356.47   441.3  1357.5   451.1 1358.82   460.9 1360.33   470.7 1362.09
   480.6 1364.39   549.2 1382.23   588.4  1391.9     608 1396.08   637.5 1401.84
#Mann= 3 , 0 , 0
       0     .05       0   212.1    .045       0   227.1     .05       0
Bank Sta=212.1,227.1
XS Rating Curve= 0 ,0
Exp/Cntr=0.3,0.1

Type RM Length L Ch R = 1 ,48377.2 ,365.3,361.1,357.3
XS GIS Cut Line= 4
      1781968.65      293458.277     1782152.678      293279.457
     1782265.525      293161.402     1782505.109      292911.402
#Sta/Elev= 30
       0 1401.79    28.5 1403.59      38 1403.66    47.5 1403.31    66.5 1401.17
    85.5 1397.59     114 1390.68   142.6 1384.34   180.6 1374.32   190.1  1372.4
   199.6 1371.28   209.1 1370.71   218.6 1369.36   228.1 1367.42   266.2 1358.29
   275.8 1356.88   304.6 1353.85   314.2 1352.22  331.34 1348.24   333.4  1347.8
   343.1 1348.36   362.3 1350.52   516.1 1356.59     545 1358.18   554.6 1359.41
   564.2 1361.43   621.9 1375.84   679.6  1389.4   746.9 1406.28   766.2 1410.64
#Mann= 3 , 0 , 0
       0     .05       0  331.34    .045       0   343.1     .05       0
Bank Sta=331.34,343.1
XS Rating Curve= 0 ,0
Exp/Cntr=0.3,0.1

Type RM Length L Ch R = 1 ,48016   ,214.1,219.3,224.5
XS GIS Cut Line= 2
     1782434.158      293527.248      1782652.04      293206.935
#Sta/Elev= 30
       0 1354.97    19.4 1352.85      29 1352.07    38.7 1351.64    48.4 1351.36
    58.1 1350.74    67.8 1349.77   106.5 1345.62   125.9 1343.41   131.9 1343.03
   135.6  1342.8   145.3 1342.82   146.9 1342.93     155 1343.51   174.3 1345.84
   193.7 1347.77   203.4 1348.56   213.1 1349.11   222.8  1349.4   242.1 1349.66
   251.8 1349.89   261.5 1350.21   280.9 1350.68   290.5 1351.11   300.2 1351.79
   309.9 1352.68   329.3 1354.77   348.6 1356.69     368 1358.17   387.4 1359.44
#Mann= 3 , 0 , 0
       0     .05       0   131.9    .045       0   146.9     .05       0
Bank Sta=131.9,146.9
XS Rating Curve= 0 ,0
Exp/Cntr=0.3,0.1

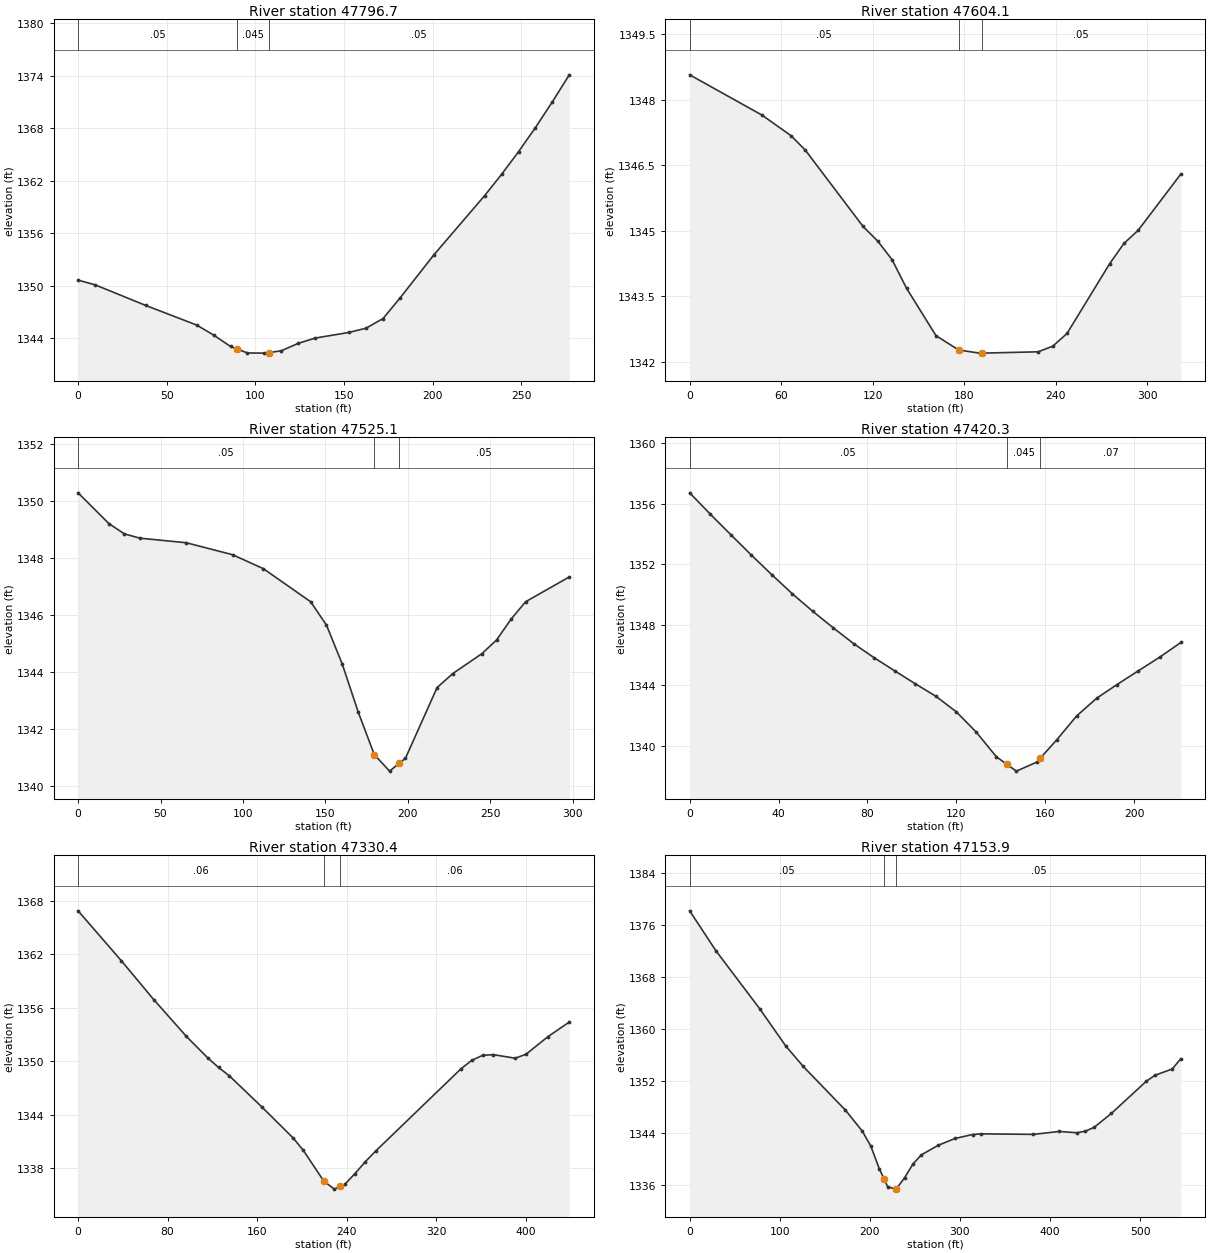
Type RM Length L Ch R = 1 ,47796.7 ,155.4,192.6,230.3
XS GIS Cut Line= 2
     1782633.464      293585.755     1782833.985      293394.609
#Sta/Elev= 24
       0 1350.63     9.6 1350.09    38.2 1347.73    66.9 1345.49    76.4 1344.35
      86 1343.04    89.6 1342.76    95.5  1342.3   104.6 1342.28  107.82 1342.34
   114.6 1342.55   124.2  1343.4   133.7    1344   152.8 1344.65   162.4 1345.13
     172 1346.24   181.5 1348.57   200.6 1353.51   229.3  1360.3   238.8 1362.72
   248.4 1365.32   257.9 1368.07   267.5 1371.03     277 1374.11
#Mann= 3 , 0 , 0
       0     .05       0    89.6    .045       0  107.82     .05       0
Bank Sta=89.6,107.82
XS Rating Curve= 0 ,0
Exp/Cntr=0.3,0.1

Type RM Length L Ch R = 1 ,47604.1 ,88.5,79,69.1
XS GIS Cut Line= 4
     1782665.698      293575.477     1782775.942      293630.152
     1782880.109      293678.763     1782955.628      293715.269
#Sta/Elev= 19
       0 1348.57    47.3 1347.65    66.3 1347.18    75.7 1346.85   113.6  1345.1
   123.1 1344.77   132.6 1344.34   142.2 1343.68   161.4  1342.6   176.4 1342.27
   190.1  1342.2   191.4  1342.2   228.4 1342.23     238 1342.36   247.3 1342.65
   275.3 1344.25   284.6 1344.71   293.9 1345.01   321.9  1346.3
#Mann= 3 , 0 , 0
       0     .05       0   176.4    .045       0   191.4     .05       0
Bank Sta=176.4,191.4
XS Rating Curve= 0 ,0
Exp/Cntr=0.3,0.1

Type RM Length L Ch R = 1 ,47525.1 ,126.5,104.9,82.6
XS GIS Cut Line= 4
     1782649.986      293646.441     1782751.636      293694.388
     1782855.803      293742.999     1782920.038       293772.56
#Sta/Elev= 22
       0 1350.28    18.7  1349.2    28.1 1348.84    37.5 1348.69    65.6 1348.53
    93.7 1348.11   112.4 1347.62   141.1 1346.46   150.7 1345.64   160.3 1344.27
   169.9  1342.6   179.7  1341.1     189 1340.52   194.7 1340.79   198.6 1340.97
   217.8 1343.45   227.3 1343.94     245 1344.64   253.9 1345.12   262.7 1345.85
   271.5 1346.46     298 1347.33
#Mann= 3 , 0 , 0
       0     .05       0   179.7    .045       0   194.7     .05       0
Bank Sta=179.7,194.7
XS Rating Curve= 0 ,0
Exp/Cntr=0.3,0.1

Type RM Length L Ch R = 1 ,47420.3 ,93.7,89.9,87.2
XS GIS Cut Line= 4
     1782725.376      293886.319     1782831.106      293829.548
     1782894.647      293795.434     1782920.038      293781.762
#Sta/Elev= 27
       0 1356.72     9.2 1355.32    18.5 1353.95    27.7 1352.61    36.9 1351.31
    46.2 1350.04    55.4 1348.88    64.6 1347.79    73.8 1346.74    83.1  1345.8
    92.3 1344.94   101.5 1344.09   110.8 1343.26     120 1342.23     129 1340.88
     138 1339.26   142.7 1338.76     147 1338.31   156.1  1338.9   157.7 1339.16
   165.1 1340.37   174.1 1341.96   183.1 1343.13   192.1 1344.02   201.7 1344.93
   211.4 1345.84     221 1346.82
#Mann= 3 , 0 , 0
       0     .05       0   142.7    .045       0   157.7     .07       0
Bank Sta=142.7,157.7
XS Rating Curve= 0 ,0
Exp/Cntr=0.3,0.1

Type RM Length L Ch R = 1 ,47330.4 ,162.9,176.5,188.9
XS GIS Cut Line= 4
     1782704.598      294022.167      1782841.49      293931.281
     1782949.563      293860.101     1783072.512       293782.63
#Sta/Elev= 25
       0 1366.89    38.7 1361.28    67.7 1356.91    96.7  1352.8     116 1350.36
   125.6  1349.3   135.3 1348.35   164.3 1344.86     192 1341.41   201.3    1340
   219.5 1336.56     229 1335.64   234.5 1335.95   238.3 1336.17   247.5 1337.39
   256.8 1338.73     266 1339.92   342.2 1349.15   351.8  1350.1   361.5 1350.66
   371.2 1350.74   390.6 1350.34   400.3 1350.78   419.7 1352.74     439  1354.4
#Mann= 3 , 0 , 0
       0     .06       0   219.5    .045       0   234.5     .06       0
Bank Sta=219.5,234.5
XS Rating Curve= 0 ,0
Exp/Cntr=0.3,0.1

Type RM Length L Ch R = 1 ,47153.9 ,438.5,426.2,413.9
XS GIS Cut Line= 4
     1782648.429      294084.085     1782774.206      294076.332
     1782942.609      294065.915     1783192.354      294047.272
#Sta/Elev= 30
       0 1378.19    29.1 1372.06    77.6 1363.17   106.6 1357.44     126 1354.29
   172.9 1347.57   191.6 1344.35     201 1342.06   210.4 1338.59  216.09 1336.92
   219.8 1335.79   229.1 1335.44   229.2 1335.46   238.5 1337.18   247.9 1339.31
   257.2 1340.71     276 1342.18   294.7 1343.23     314 1343.83   323.6 1343.93
   381.4 1343.85   410.3  1344.3   429.6  1344.1   439.2 1344.34   448.9 1344.93
   468.1 1347.07   506.6 1351.98   516.3 1352.92   535.6 1353.89   545.2 1355.48
#Mann= 3 , 0 , 0
       0     .05       0  216.09    .045       0   229.2     .05       0
Bank Sta=216.09,229.2
XS Rating Curve= 0 ,0
Exp/Cntr=0.3,0.1

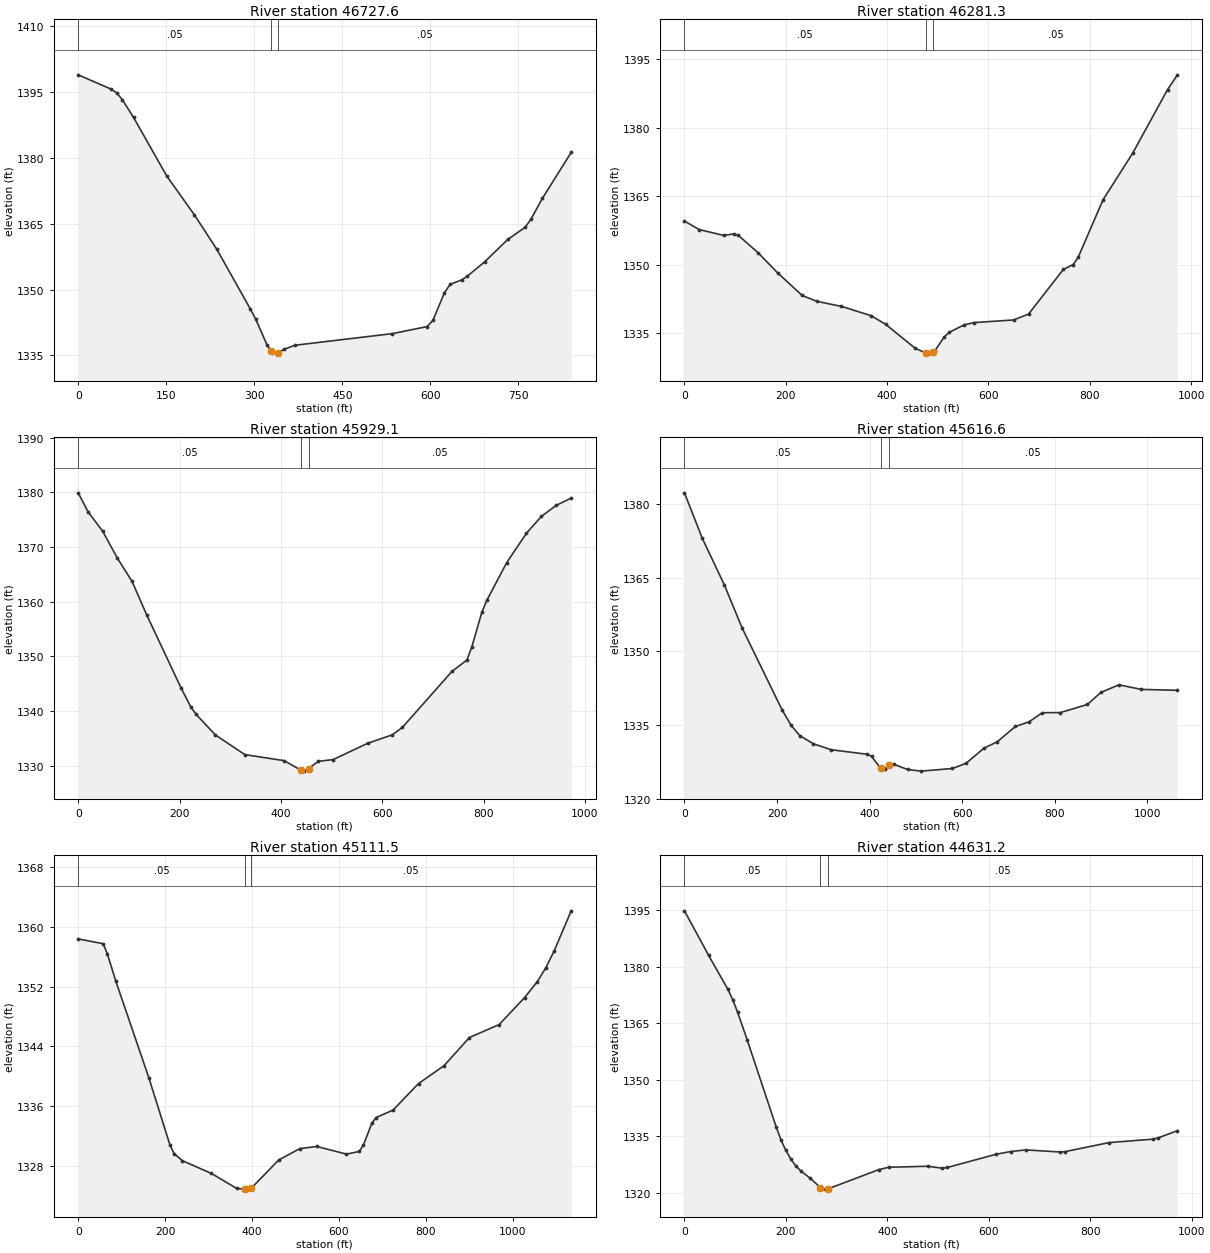
Type RM Length L Ch R = 1 ,46727.6 ,446.2,446.3,445.2
XS GIS Cut Line= 4
     1782783.608      294630.599     1782961.706      294506.888
     1783104.067      294411.402     1783485.648      294169.444
#Sta/Elev= 30
       0 1398.97    56.6 1395.68      66  1394.8    75.4 1393.27    94.3 1389.26
   150.8 1375.93     198 1367.05   235.9 1359.27     293 1345.68   302.6 1343.25
   321.6 1337.45  328.52 1336.08   331.1  1335.6   340.6 1335.53   340.9 1335.56
   350.2 1336.37   369.2 1337.32   535.6 1339.98   594.5 1341.58   604.4 1342.97
     624 1349.25   633.8 1351.22   653.5 1352.22   663.3 1353.08   692.8 1356.36
     732 1361.44   761.5  1364.2   771.3    1366     791  1370.8   840.1 1381.29
#Mann= 3 , 0 , 0
       0     .05       0  328.52    .045       0   340.9     .05       0
Bank Sta=328.52,340.9
XS Rating Curve= 0 ,0
Exp/Cntr=0.3,0.1

Type RM Length L Ch R = 1 ,46281.3 ,352.3,352.2,352.3
XS GIS Cut Line= 4
     1782931.192      295085.885     1783200.855      294880.586
     1783374.466      294757.322     1783723.425      294521.211
#Sta/Elev= 30
       0 1359.53      29 1357.68    77.5 1356.39    96.8 1356.72   106.5  1356.4
   145.2 1352.61     184 1348.19   232.4 1343.25   261.4 1341.97   309.9 1340.87
     368 1338.85     397 1336.96   455.1 1331.72   476.2 1330.68   484.1 1330.64
   491.2 1330.96   493.8 1331.08   513.1 1334.23   522.8  1335.2   551.8 1336.82
   571.4 1337.32   649.8  1337.9   679.2 1339.18   747.8 1348.94   767.4 1350.03
   777.2 1351.62   826.2 1364.18     885 1374.43   953.6 1388.29   973.2 1391.53
#Mann= 3 , 0 , 0
       0     .05       0   476.2    .045       0   491.2     .05       0
Bank Sta=476.2,491.2
XS Rating Curve= 0 ,0
Exp/Cntr=0.3,0.1

Type RM Length L Ch R = 1 ,45929.1 ,297.6,312.5,326.4
XS GIS Cut Line= 4
     1783119.258      295331.974     1783410.925      295160.099
     1783584.536      295036.836     1783933.494      294800.724
#Sta/Elev= 30
       0 1379.92    19.4 1376.46    48.4 1372.89    77.4 1367.95   106.4  1363.7
   135.4 1357.54   203.1  1344.2   222.5 1340.69   232.1 1339.45   270.8 1335.61
   328.9 1332.02   406.3 1330.92   439.7 1329.17     445    1329   454.7 1329.48
     474  1330.8   503.1 1331.11   571.1 1334.09     620 1335.65   639.6 1336.99
   737.6 1347.25     767 1349.32   776.8 1351.75   796.4 1358.03   806.2 1360.23
   845.4 1367.12   884.6 1372.54     914 1375.61   943.4 1377.63   972.8 1378.96
#Mann= 3 , 0 , 0
       0     .05       0   439.7    .045       0   454.7     .05       0
Bank Sta=439.7,454.7
XS Rating Curve= 0 ,0
Exp/Cntr=0.3,0.1

Type RM Length L Ch R = 1 ,45616.6 ,501.7,505.1,507.9
XS GIS Cut Line= 4
     1783102.331       295385.36     1783361.011       295394.04
     1783749.103      295404.166     1784144.937      295539.583
#Sta/Elev= 30
       0 1382.24    38.3 1373.03    86.3 1363.48   124.6 1354.74   210.9 1338.09
   230.1 1334.99   249.2 1332.85   278.2  1331.2   317.1 1329.98   394.7 1329.06
   404.4 1328.61   423.8 1326.23   433.5 1326.12   441.9  1326.8   452.9    1327
     482 1325.97   511.2 1325.63   579.1 1326.17   608.2  1327.2     647 1330.28
   676.2 1331.62   715.2 1334.72   744.3 1335.64   773.5 1337.51   812.4 1337.54
   870.8 1339.19     900 1341.65   938.9 1343.18   987.6 1342.25  1065.4 1342.07
#Mann= 3 , 0 , 0
       0     .05       0   423.8    .045       0   441.9     .05       0
Bank Sta=423.8,441.9
XS Rating Curve= 0 ,0
Exp/Cntr=0.3,0.1

Type RM Length L Ch R = 1 ,45111.5 ,475.7,480.3,484.1
XS GIS Cut Line= 4
     1783064.592      295834.428     1783358.454      295877.882
      1783549.45      295908.159     1784186.945      295998.791
#Sta/Elev= 30
       0 1358.41    57.5 1357.77    67.1  1356.4    86.2 1352.81   162.9 1339.72
   210.8 1330.82   220.4 1329.62   239.6 1328.66   306.7 1326.94   364.7 1324.93
   383.3 1324.84   398.3 1324.97   461.4 1328.75     510 1330.28     549 1330.56
   617.3 1329.54   646.5 1329.89   656.3 1330.76   675.8  1333.7   685.6 1334.45
   724.6 1335.45   783.1 1339.01   841.7  1341.4   900.2 1345.18   968.5 1346.92
    1027 1350.53  1056.3 1352.67  1075.8 1354.53  1095.3 1356.82  1134.3 1362.18
#Mann= 3 , 0 , 0
       0     .05       0   383.3    .045       0   398.3     .05       0
Bank Sta=383.3,398.3
XS Rating Curve= 0 ,0
Exp/Cntr=0.3,0.1

Type RM Length L Ch R = 1 ,44631.2 ,340.3,346,350.7
XS GIS Cut Line= 4
     1783080.874      296251.866     1783264.902      296329.991
     1783537.471      296427.213     1784018.634      296466.232
#Sta/Elev= 30
       0 1394.86    47.6 1383.03    85.7    1374    95.2 1371.24   104.7 1367.96
   123.8 1360.54   180.9 1337.46   190.4    1334   199.9 1331.23   209.6 1328.99
   219.2 1327.18   228.9 1325.88   248.2 1323.82   268.2 1321.38   277.1 1320.97
   283.2 1321.05   383.2 1326.15   402.5 1326.77   479.7 1327.05   508.6 1326.52
   518.3 1326.72   614.8 1330.24   643.8 1330.96   672.8 1331.39   740.3 1330.83
     750 1330.91   836.9 1333.32   923.8 1334.24   933.4 1334.54   972.1  1336.5
#Mann= 3 , 0 , 0
       0     .05       0   268.2    .045       0   283.2     .05       0
Bank Sta=268.2,283.2
XS Rating Curve= 0 ,0
Exp/Cntr=0.3,0.1

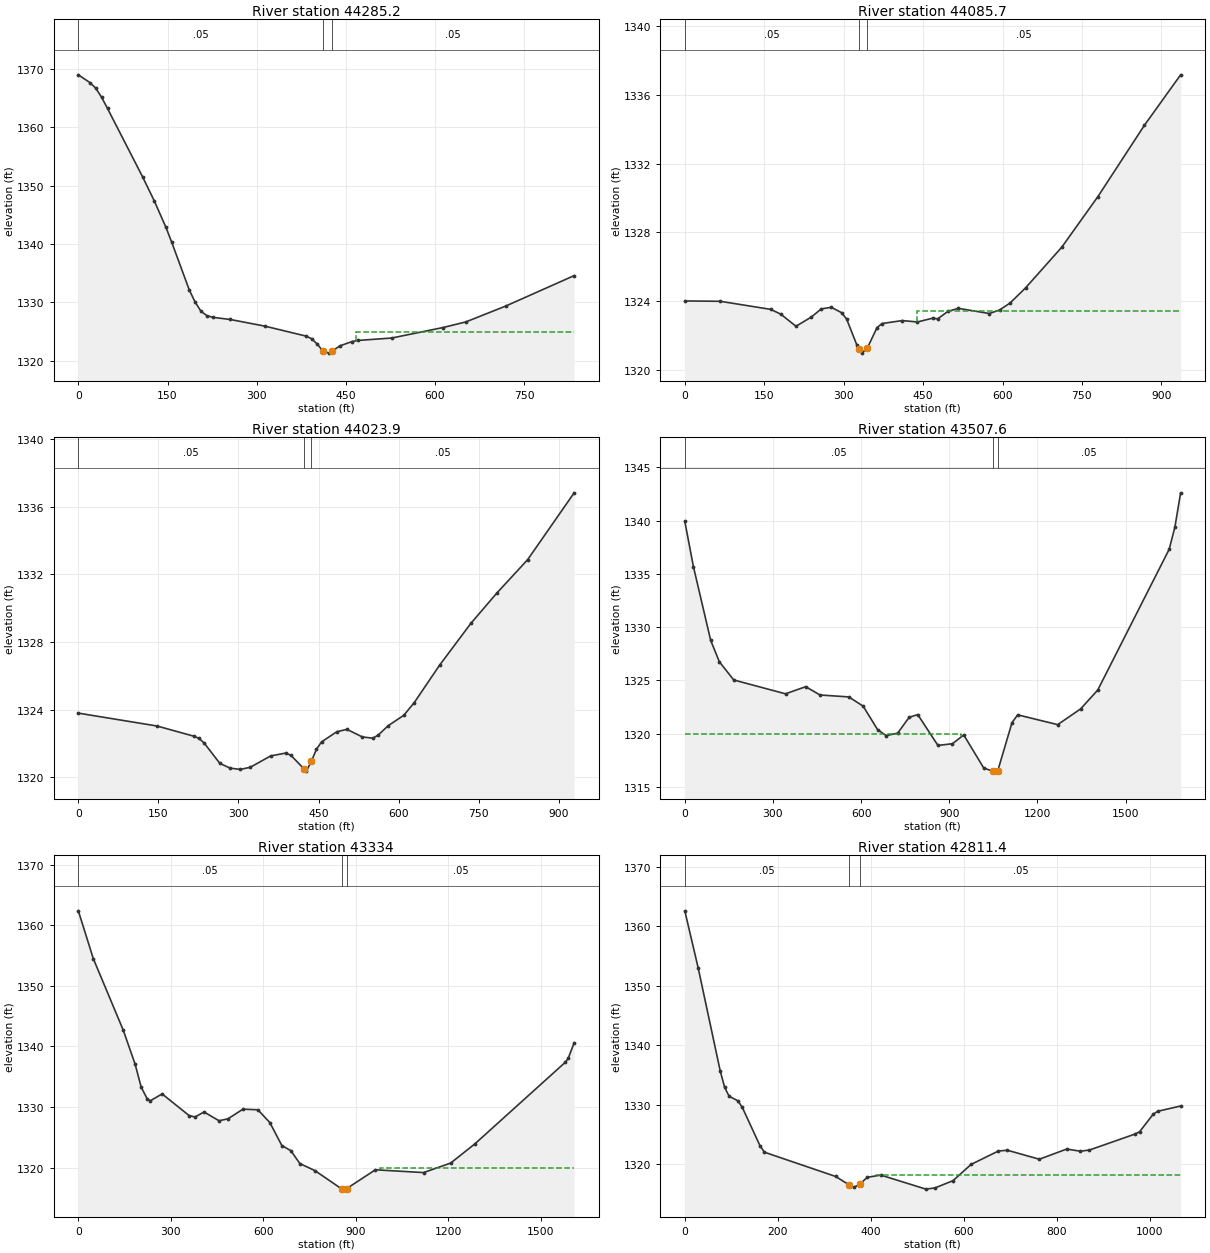
Type RM Length L Ch R = 1 ,44285.2 ,237.6,199.5,150.7
XS GIS Cut Line= 4
     1782864.077      296448.698     1783155.744      296630.989
     1783261.647      296698.698     1783624.494      296731.684
#Sta/Elev= 30
       0 1368.99    19.6 1367.65    29.5 1366.68    39.3 1365.11    49.1 1363.22
   108.1  1351.5   127.8 1347.37   147.4 1342.83   157.2 1340.26   186.7 1332.09
   196.5 1330.02   206.4 1328.44   216.2 1327.71     226 1327.42   255.5 1327.05
   314.5 1325.89   382.6 1324.21   392.3 1323.76     402 1322.82   411.1 1321.66
   421.3 1321.28   426.1  1321.6   440.6 1322.55     460 1323.25   469.6 1323.45
   527.2 1323.87   613.5 1325.67   651.8 1326.63   718.9 1329.35     834 1334.57
#Mann= 3 , 0 , 0
       0     .05       0   411.1    .045       0   426.1     .05       0
#XS Ineff= 2 , 0
                          466.25         1324.88
Permanent Ineff=
       F       F
Bank Sta=411.1,426.1
XS Rating Curve= 0 ,0
Exp/Cntr=0.3,0.1

Type RM Length L Ch R = 1 ,44085.7 ,61.4,61.8,69.3
XS GIS Cut Line= 4
     1782885.397      296852.374     1783073.728      296945.299
     1783215.873       296718.52     1783672.046      296766.545
#Sta/Elev= 30
       0 1324.02    66.8    1324   162.3 1323.53   181.4 1323.25     210 1322.55
   238.7 1323.08   257.8 1323.56   276.9 1323.65     296 1323.34   305.6 1322.97
   324.7 1321.48   329.8 1321.22   334.3 1320.99   344.8 1321.29     363 1322.47
   372.5 1322.71   410.7 1322.88   439.4  1322.8   468.1 1323.02   477.6 1322.98
   497.2 1323.42   516.7 1323.59   575.2 1323.29   594.8  1323.5   614.3  1323.9
   643.6 1324.78   711.9 1327.14   780.2 1330.08     868 1334.22   936.4 1337.15
#Mann= 3 , 0 , 0
       0     .05       0   329.8    .045       0   344.8     .05       0
#XS Ineff= 2 , 0
          276.57 1323.63  439.43         1323.44
Permanent Ineff=
       F       F
Bank Sta=329.8,344.8
XS Rating Curve= 0 ,0
Exp/Cntr=0.3,0.1

Type RM Length L Ch R = 1 ,44023.9 ,485.5,516.2,546.2
XS GIS Cut Line= 4
     1782859.355      296903.415     1783102.364      297009.372
     1783233.147      296810.273     1783656.421      296855.086
#Sta/Elev= 30
       0  1323.8   147.3 1323.04     216 1322.44   225.8 1322.31   235.6 1322.04
   265.1 1320.83   284.2 1320.55   303.2 1320.47   322.3  1320.6   360.4 1321.27
     389 1321.44   398.5  1321.3   422.9  1320.5   427.1 1320.37   436.6 1320.95
   446.1 1321.66   455.7  1322.1   484.3  1322.7   503.3 1322.84   532.3 1322.39
   551.7 1322.32   561.4 1322.49   580.7 1323.06   609.7 1323.67   629.1 1324.41
   677.4 1326.66   735.5 1329.11   783.8 1330.89   841.9 1332.88     929 1336.83
#Mann= 3 , 0 , 0
       0     .05       0   422.9    .045       0   436.6     .05       0
Bank Sta=422.9,436.6
XS Rating Curve= 0 ,0
Exp/Cntr=0.3,0.1

Type RM Length L Ch R = 1 ,43507.6 ,177.9,173.7,169.2
XS GIS Cut Line= 6
     1782567.584      296451.747      1782823.66      296903.136
      1782871.23       297182.65     1782884.251      297289.942
     1783105.865      297357.585     1783650.136      297332.845
#Sta/Elev= 30
       0 1339.92    29.4 1335.67    88.1 1328.76   117.5 1326.76   166.5 1325.05
   342.7 1323.75   411.3 1324.42   460.2 1323.64   558.1 1323.46     607 1322.59
   655.8  1320.4   685.2 1319.83   724.3 1320.06   763.4 1321.55   792.7  1321.8
   861.4 1318.91   910.6 1319.07   949.2 1319.89  1016.8 1316.81  1045.7  1316.5
  1050.1  1316.5  1065.1 1316.55  1113.3 1321.04  1132.6 1321.78  1268.8 1320.86
  1346.6 1322.33    1405  1324.1  1648.2 1337.31  1667.7  1339.4  1687.1  1342.6
#Mann= 3 , 0 , 0
       0     .05       0  1050.1    .045       0  1065.1     .05       0
#XS Ineff= 2 , 0
          939.64 1320.01
Permanent Ineff=
       F       F
Bank Sta=1050.1,1065.1
XS Rating Curve= 0 ,0
Exp/Cntr=0.3,0.1

Type RM Length L Ch R = 1 ,43334   ,523.2,522.6,521.1
XS GIS Cut Line= 4
      1782139.72      297222.168     1782782.167      297471.062
     1783064.199      297503.418     1783698.313      297534.668
#Sta/Elev= 30
       0 1362.38    48.5  1354.5   145.6  1342.7   184.4 1337.04   203.8 1333.29
   223.2 1331.38   232.9 1331.03   271.7 1332.18     359 1328.61   378.4 1328.37
   407.6  1329.2   456.1 1327.75   485.2 1328.07   533.7 1329.66   582.2 1329.56
     621 1327.45   659.9 1323.66     689 1322.82   718.3 1320.69   767.3 1319.52
   854.6 1316.48   855.4 1316.47   869.6 1316.54   963.1 1319.66  1119.4  1319.2
  1207.3 1320.77  1285.4 1323.92  1578.4 1337.37  1588.2 1338.02  1607.7 1340.61
#Mann= 3 , 0 , 0
       0     .05       0   854.6    .045       0   869.6     .05       0
#XS Ineff= 2 , 0
                          979.18         1319.99
Permanent Ineff=
       F       F
Bank Sta=854.6,869.6
XS Rating Curve= 0 ,0
Exp/Cntr=0.3,0.1

Type RM Length L Ch R = 1 ,42811.4 ,486.2,530.9,532.9
XS GIS Cut Line= 4
       1782665.2      297947.557     1782949.922      297968.825
     1783288.464      297997.471     1783727.266      298040.439
#Sta/Elev= 30
       0 1362.59    28.6 1353.06    76.1 1335.73    85.6 1332.95    95.2 1331.46
   114.2 1330.68   123.7 1329.57   161.8 1323.12   171.3 1322.05   324.3 1317.98
   353.5 1316.56   363.2 1316.13   376.8 1316.72   392.3 1317.83   421.4 1318.21
   518.5 1315.85   537.9 1316.05   576.7 1317.27   615.6    1320   674.3 1322.25
   693.8 1322.38   762.4 1320.87   821.2 1322.58   850.6 1322.22   870.2 1322.42
   968.2  1325.1     978 1325.49  1007.4 1328.45  1017.2 1328.93  1066.2 1329.81
#Mann= 3 , 0 , 0
       0     .05       0   353.5    .045       0   376.8     .05       0
#XS Ineff= 2 , 0
                          411.71         1318.21
Permanent Ineff=
       F       F
Bank Sta=353.5,376.8
XS Rating Curve= 0 ,0
Exp/Cntr=0.3,0.1

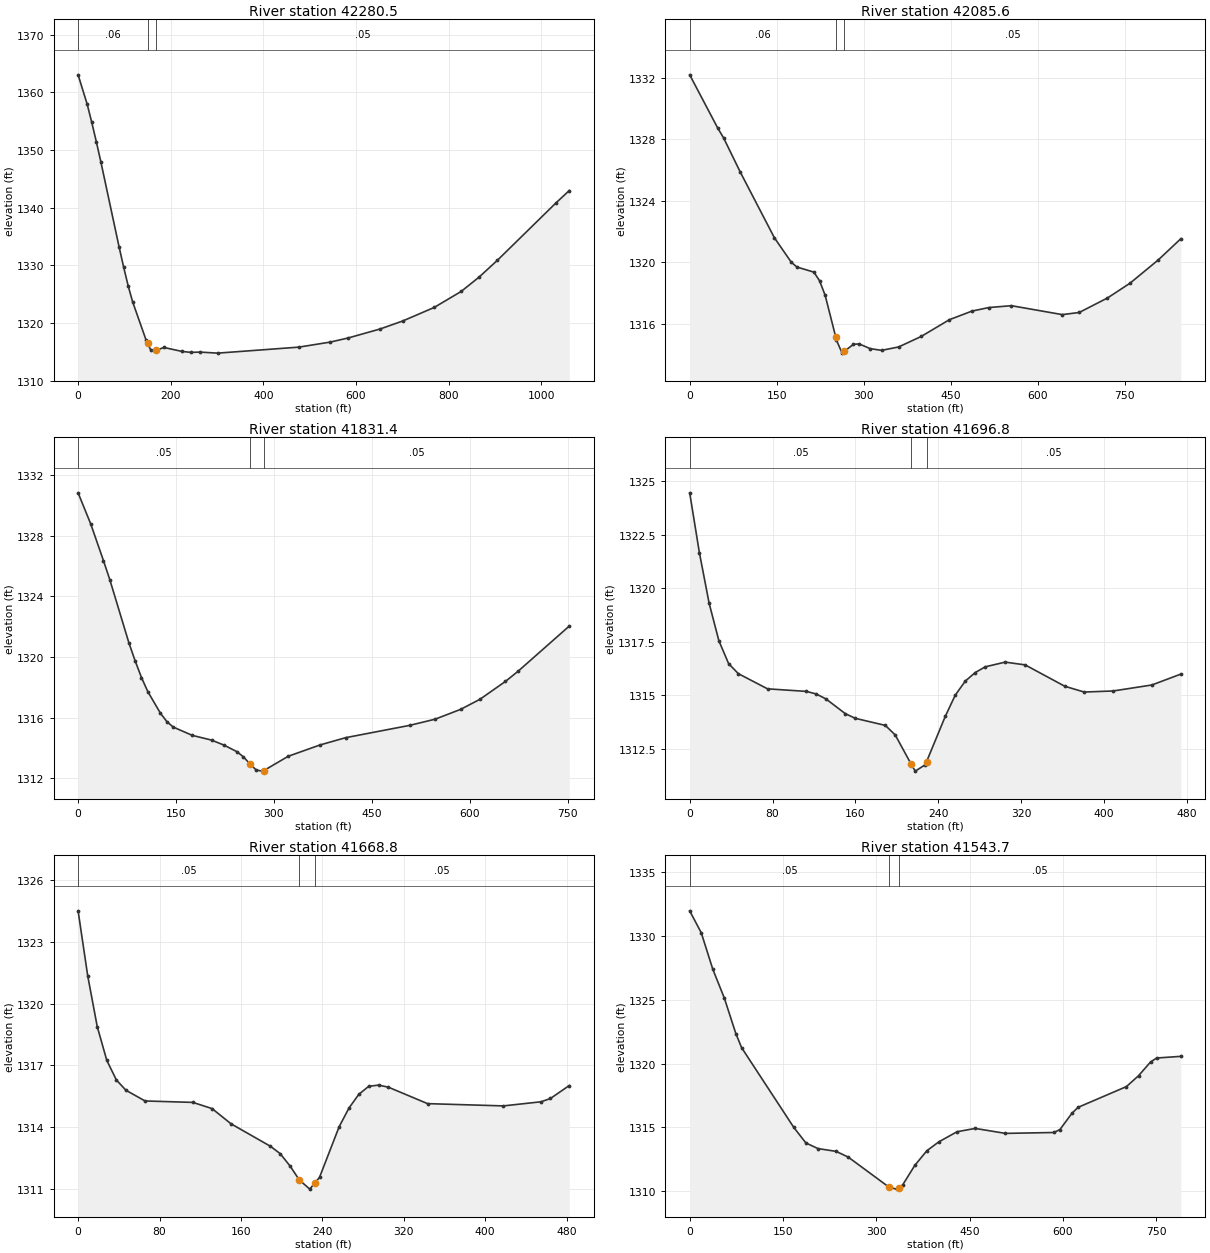
Type RM Length L Ch R = 1 ,42280.5 ,196.5,194.9,193.3
XS GIS Cut Line= 4
     1782604.436      298033.148     1782684.753      298090.004
     1782806.281       298185.49     1783441.697      298683.754
#Sta/Elev= 30
       0 1363.04    19.7 1357.92    29.5 1354.79    39.4 1351.43    49.2 1347.93
    88.6 1333.17    98.4 1329.69   108.1 1326.46   117.7  1323.7   146.7 1317.08
   150.2 1316.48   156.4 1315.41     166 1315.18  168.51 1315.29   185.3 1315.78
     224  1315.1   243.3 1314.93   262.7 1314.98   301.6  1314.8   476.7 1315.84
   544.8 1316.72   583.7 1317.44   651.8 1318.98   700.5 1320.36   768.6 1322.71
     827 1325.49   865.9 1327.99   904.8 1330.86  1031.2  1340.8  1060.4 1342.98
#Mann= 3 , 0 , 0
       0     .06       0   150.2    .045       0  168.51     .05       0
Bank Sta=150.2,168.51
XS Rating Curve= 0 ,0
Exp/Cntr=0.3,0.1

Type RM Length L Ch R = 1 ,42085.6 ,258.6,254.2,249.5
XS GIS Cut Line= 2
      1782429.74      298154.589      1783138.29      298618.998
#Sta/Elev= 30
       0 1332.18    48.7  1328.7    58.4 1328.09    87.6 1325.84   146.1  1321.6
   175.3 1320.01     185  1319.7   214.2 1319.37     224 1318.81   233.7 1317.86
   251.8 1315.17   253.2 1314.95   262.9 1314.11   266.8 1314.23   282.4 1314.68
   292.1 1314.71   311.6  1314.4   331.1 1314.29   360.3 1314.51   399.2 1315.19
   447.9 1316.28   486.9 1316.84   516.1 1317.07     555 1317.19   642.7 1316.61
   671.9 1316.75   720.6 1317.69   759.5 1318.65   808.2 1320.16   847.2 1321.54
#Mann= 3 , 0 , 0
       0     .06       0   251.8    .045       0   266.8     .05       0
Bank Sta=251.8,266.8
XS Rating Curve= 0 ,0
Exp/Cntr=0.3,0.1

Type RM Length L Ch R = 1 ,41831.4 ,134.4,134.6,134.7
XS GIS Cut Line= 3
     1782386.337      298436.707     1782518.715      298497.471
     1783081.867      298723.165
#Sta/Elev= 30
       0 1330.84    19.4 1328.78    38.8 1326.37    48.6  1325.1    77.7 1320.95
    87.4 1319.74    97.1 1318.64   106.8 1317.71   126.2 1316.28     136 1315.73
   145.7 1315.37     175 1314.82   204.4 1314.51   223.9 1314.17   243.5 1313.74
   253.3  1313.4   263.4 1312.93   272.9 1312.53   282.6 1312.46  284.69  1312.5
   321.8 1313.44   370.7 1314.19   409.9 1314.67   507.7 1315.48   546.9 1315.89
     586 1316.54   615.4  1317.2   654.5 1318.38   674.1 1319.06   752.4 1322.04
#Mann= 3 , 0 , 0
       0     .05       0   263.4    .045       0  284.69     .05       0
Bank Sta=263.4,284.69
XS Rating Curve= 0 ,0
Exp/Cntr=0.3,0.1

Type RM Length L Ch R = 1 ,41696.8 ,28,28,28
XS GIS Cut Line= 4
     1782406.717      298590.237     1782545.172      298648.831
     1782733.017      298725.073     1782843.947      298774.561
#Sta/Elev= 30
       0 1324.47     9.4 1321.66    18.8  1319.3    28.2 1317.55    37.6 1316.48
      47 1316.01    75.2  1315.3   112.8 1315.18   122.2 1315.06   131.6 1314.83
   150.3 1314.14     160 1313.92     189 1313.59   198.6 1313.14   213.8 1311.79
   217.9 1311.45   227.6 1311.75   228.8 1311.89   246.9 1314.01   256.5    1315
   266.2 1315.66   275.8 1316.06   285.5 1316.33   304.8 1316.55   324.1 1316.42
   362.4 1315.42   381.1 1315.15   409.1  1315.2   446.5 1315.48   474.5 1315.99
#Mann= 3 , 0 , 0
       0     .05       0   213.8    .045       0   228.8     .05       0
Bank Sta=213.8,228.8
XS Rating Curve= 0 ,0
Exp/Cntr=0.3,0.1

Type RM Length L Ch R = 1 ,41668.8 ,129,125.1,121.1
XS GIS Cut Line= 4
     1782391.874      298614.456     1782530.329       298673.05
     1782718.173      298749.292     1782837.871      298798.867
#Sta/Elev= 28
       0  1324.5     9.4 1321.36    18.8 1318.88    28.2 1317.24    37.6 1316.29
      47 1315.79    65.8 1315.27   112.8  1315.2   131.6  1314.9   150.3 1314.16
     189 1313.07   198.6 1312.71   208.3 1312.11   217.3 1311.44   227.6 1310.99
   232.3 1311.27   237.2 1311.56   256.5 1314.02   266.2 1314.93   275.8 1315.59
   285.5 1315.98   295.2 1316.04   304.8 1315.94   343.4 1315.14   417.8 1315.03
   454.9 1315.23   464.1 1315.39   482.6 1316.02
#Mann= 3 , 0 , 0
       0     .05       0   217.3    .045       0   232.3     .05       0
Bank Sta=217.3,232.3
XS Rating Curve= 0 ,0
Exp/Cntr=0.3,0.1

Type RM Length L Ch R = 1 ,41543.7 ,427.5,424.6,421.7
XS GIS Cut Line= 3
     1782239.964      298747.095      1782393.61      298782.685
     1783011.665      298915.498
#Sta/Elev= 30
       0 1331.98    18.6 1330.26    37.1 1327.41    55.7 1325.14    74.2 1322.36
    83.5 1321.25   167.4    1315   186.9 1313.78   206.3 1313.34   235.5 1313.12
     255 1312.67     321  1310.3   332.8 1310.16     336 1310.27   342.5 1310.49
     362 1312.02   381.4 1313.17   400.8 1313.87     430 1314.66   459.2 1314.92
   507.8 1314.53   585.6  1314.6   595.4 1314.83   614.8 1316.11   624.5 1316.57
   702.4  1318.2   721.8 1319.05   741.2 1320.13     751 1320.44   789.9 1320.57
#Mann= 3 , 0 , 0
       0     .05       0     321    .045       0     336     .05       0
Bank Sta=321,336
XS Rating Curve= 0 ,0
Exp/Cntr=0.3,0.1