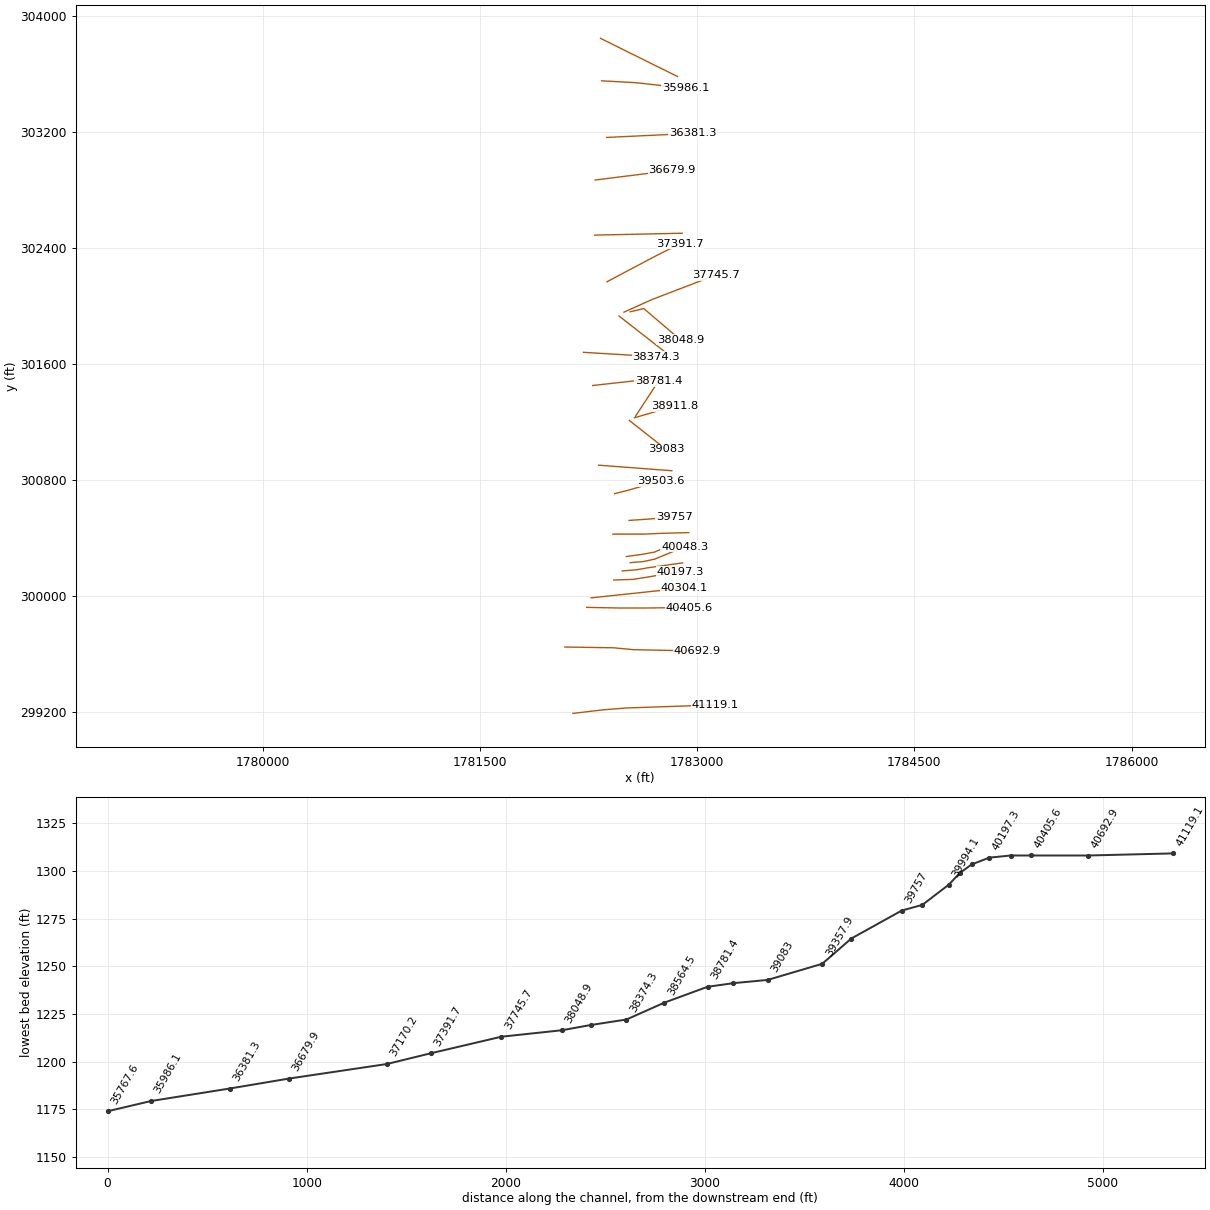
HEC-RAS study HusteadFrk.prj: HusteadFrk

--- HusteadFrk.g01 (geometry) --- (continued)

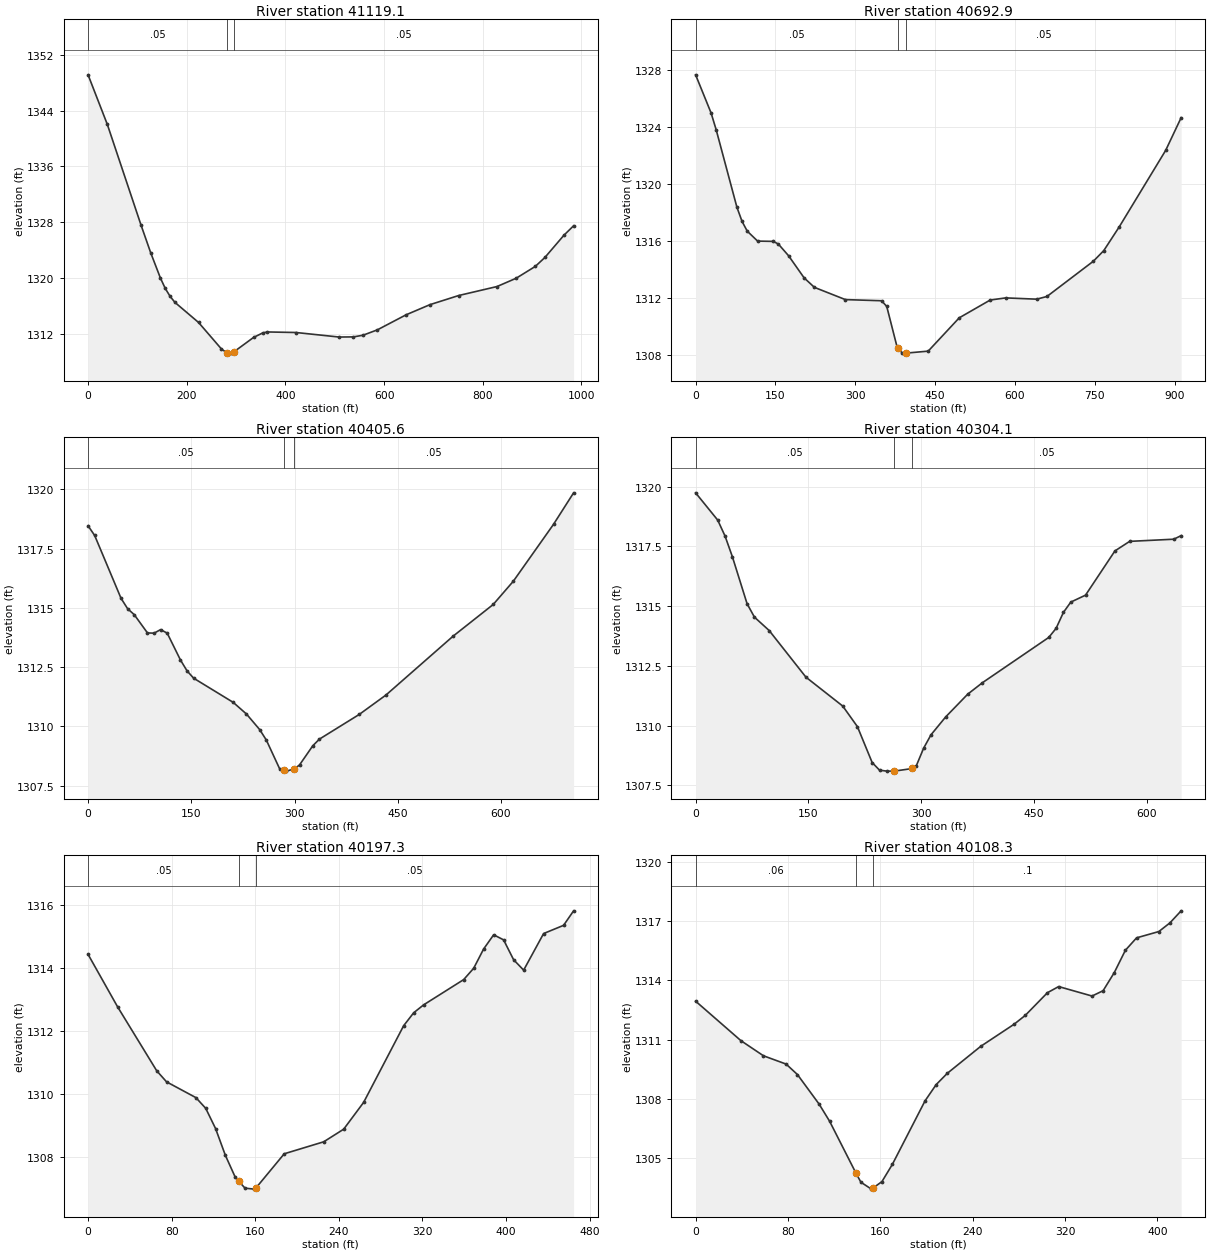
Type RM Length L Ch R = 1 ,41119.1 ,429.8,426.2,421.7
XS GIS Cut Line= 4
     1782142.091      299187.931     1782346.085      299211.803
      1782503.42      299224.824     1783123.989      299246.254
#Sta/Elev= 30
       0 1349.15    39.1 1342.02   107.6 1327.53   127.1 1323.58   146.7 1319.97
   156.5 1318.48   166.3 1317.35     176 1316.49     224  1313.6   270.4 1309.79
   280.9 1309.27     289  1309.2   295.9  1309.4   335.4 1311.45     354  1312.1
   363.3 1312.24   421.5 1312.16   508.8 1311.51   537.9 1311.53   557.3 1311.77
   586.4 1312.54   644.6  1314.7   693.1 1316.16   751.3 1317.47     829 1318.76
   867.8 1319.95   906.6 1321.65     926 1322.93   964.8 1326.14   984.2 1327.48
#Mann= 3 , 0 , 0
       0     .05       0   280.9    .045       0   295.9     .05       0
Bank Sta=280.9,295.9
XS Rating Curve= 0 ,0
Exp/Cntr=0.3,0.1

Type RM Length L Ch R = 1 ,40692.9 ,284.9,287.2,289.3
XS GIS Cut Line= 4
     1782085.668      299645.831     1782425.295      299640.405
     1782560.928      299627.385     1782997.126      299618.704
#Sta/Elev= 30
       0 1327.65    29.1 1324.97    38.8 1323.77    77.6 1318.35    87.3 1317.35
      97 1316.67   116.5 1315.97   145.6 1315.95   155.3 1315.77   174.7 1314.94
   203.8 1313.39   223.2 1312.72   281.4 1311.86   349.4 1311.78   359.1 1311.38
   378.6 1308.52   380.1 1308.46   388.3  1308.1   395.1  1308.1     437 1308.24
   495.3 1310.58   553.5 1311.83   582.6 1311.98   640.8 1311.89   660.1 1312.08
   747.4 1314.56   766.8  1315.3   795.9 1316.97   883.1 1322.34   912.2 1324.64
#Mann= 3 , 0 , 0
       0     .05       0   380.1    .045       0   395.1     .05       0
Bank Sta=380.1,395.1
XS Rating Curve= 0 ,0
Exp/Cntr=0.3,0.1

Type RM Length L Ch R = 1 ,40405.6 ,99,101.5,104.1
XS GIS Cut Line= 4
     1782237.578      299919.268     1782467.612      299914.928
     1782631.458      299914.928     1782942.873      299918.183
#Sta/Elev= 30
       0 1318.46     9.6 1318.05    47.9  1315.4    57.5 1314.96    67.1 1314.71
    86.3 1313.94    95.9 1313.93   105.4 1314.08     115 1313.93   134.2  1312.8
   143.8 1312.34   153.4 1312.03   210.9 1311.01   230.1 1310.52   249.4 1309.86
     259 1309.42   278.3 1308.21   284.5 1308.15   287.9 1308.11   299.5  1308.2
   307.2 1308.37   326.5 1309.18   336.1 1309.46   393.9  1310.5   432.8 1311.32
   530.2  1313.8   588.6 1315.14   617.8 1316.12   676.2 1318.52   705.4 1319.85
#Mann= 3 , 0 , 0
       0     .05       0   284.5    .045       0   299.5     .05       0
Bank Sta=284.5,299.5
XS Rating Curve= 0 ,0
Exp/Cntr=0.3,0.1

Type RM Length L Ch R = 1 ,40304.1 ,104.4,106.8,111.3
XS GIS Cut Line= 2
     1782267.308      299984.942     1782909.669      300053.301
#Sta/Elev= 30
       0 1319.74    29.4  1318.6    39.2 1317.93    48.9 1317.07    68.5  1315.1
    78.3 1314.54    97.9 1313.98   146.8 1312.03   195.8 1310.82   215.3 1309.96
   234.9 1308.46   244.7 1308.14   254.5  1308.1   264.3  1308.1   288.5 1308.21
   293.6 1308.32   303.4 1309.06   313.2 1309.62   332.8 1310.37   362.1 1311.32
   381.7  1311.8   469.8 1313.69   479.6 1314.07   489.4 1314.74   499.2 1315.17
   518.8 1315.46   557.9 1317.31   577.5 1317.71   636.2  1317.8     646 1317.95
#Mann= 3 , 0 , 0
       0     .05       0   264.3    .045       0   288.5     .05       0
Bank Sta=264.3,288.5
XS Rating Curve= 0 ,0
Exp/Cntr=0.3,0.1

Type RM Length L Ch R = 1 ,40197.3 ,83.7,89,87.9
XS GIS Cut Line= 4
      1782424.21       300108.07     1782555.503      300112.411
     1782639.053      300125.431     1782884.279      300166.664
#Sta/Elev= 30
       0 1314.42    28.2 1312.76    65.7 1310.73    75.1 1310.38   103.2 1309.88
   112.6 1309.54     122  1308.9   131.4 1308.05   140.8 1307.36   144.2 1307.23
   150.2 1307.01   159.2 1306.98  160.47 1307.01   187.7  1308.1   225.5 1308.48
   244.6 1308.88   263.7 1309.73     302 1312.16   311.6 1312.57   321.1 1312.82
   359.4 1313.62     369 1313.98   378.5 1314.59   388.1 1315.04   397.6 1314.88
   407.2 1314.25   416.8 1313.92   435.9 1315.08     455 1315.34   464.6  1315.8
#Mann= 3 , 0 , 0
       0     .05       0   144.2    .045       0  160.47     .05       0
Bank Sta=144.2,160.47
XS Rating Curve= 0 ,0
Exp/Cntr=0.3,0.1

Type RM Length L Ch R = 1 ,40108.3 ,63.6,60,59.3
XS GIS Cut Line= 4
     1782482.803      300171.004      1782580.46        300178.6
     1782660.755      300192.706      1782899.47      300226.343
#Sta/Elev= 29
       0 1312.95    39.2 1310.95    58.8 1310.18    78.4 1309.76    88.2 1309.23
     107 1307.73   116.1 1306.86     139 1304.22   143.2 1303.77   152.3 1303.42
     154 1303.49   161.4  1303.8   170.4 1304.67   198.8  1307.9   208.4 1308.72
     218 1309.29     247 1310.66   275.9 1311.78   285.6 1312.23   304.8 1313.38
   314.5 1313.69   343.4 1313.21     353 1313.48   362.7  1314.4   372.3 1315.53
     382 1316.16   401.3 1316.48   410.9 1316.92   420.6 1317.53
#Mann= 3 , 0 , 0
       0     .06       0     139    .045       0     154      .1       0
Bank Sta=139,154
XS Rating Curve= 0 ,0
Exp/Cntr=0.3,0.1

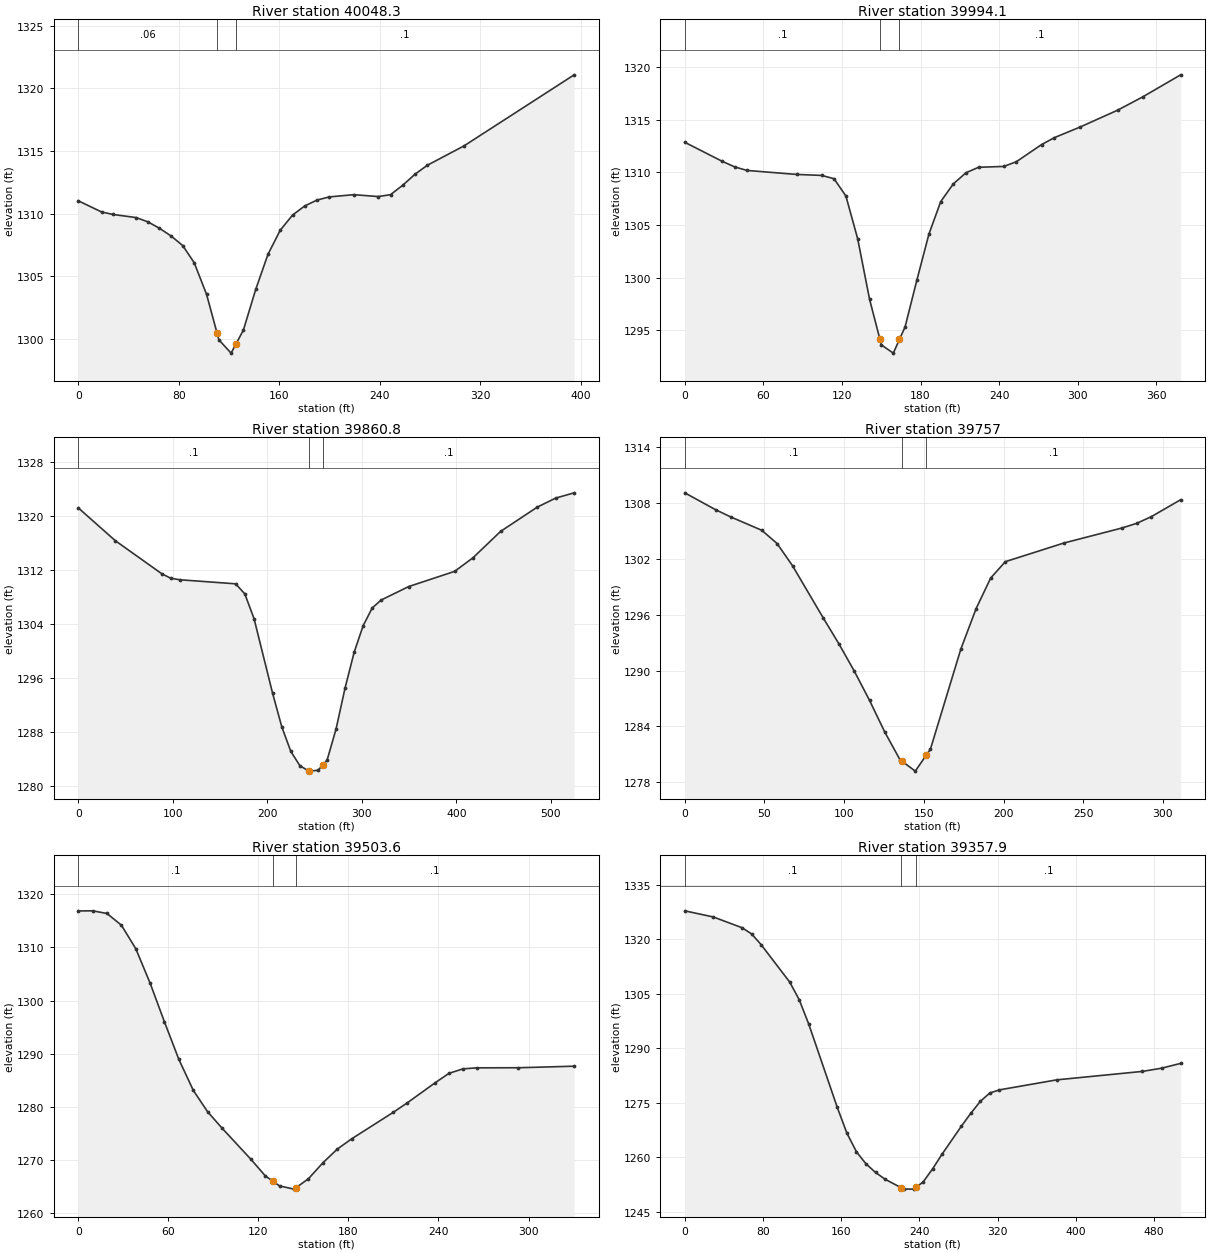
Type RM Length L Ch R = 1 ,40048.3 ,55.8,54.2,52.8
XS GIS Cut Line= 4
     1782537.144      300227.753     1782629.157      300235.566
     1782705.546      300252.059     1782913.012      300337.128
#Sta/Elev= 30
       0 1311.03    18.5 1310.14    27.7 1309.94    46.2 1309.69    55.4 1309.35
    64.6 1308.84    73.9 1308.22    83.1 1307.46    92.3 1306.08   102.1 1303.56
   110.4 1300.49   111.9 1299.94   121.6 1298.88   125.4 1299.59   131.4 1300.72
   141.2 1303.96     151 1306.77   160.7 1308.68   170.5 1309.89   180.2 1310.62
     190 1311.09   199.7 1311.34   219.2 1311.52   238.7 1311.37   248.5 1311.52
   258.2 1312.27     268 1313.15   277.7 1313.86     307 1315.41   394.7 1321.08
#Mann= 3 , 0 , 0
       0     .06       0   110.4    .045       0   125.4      .1       0
Bank Sta=110.4,125.4
XS Rating Curve= 0 ,0
Exp/Cntr=0.3,0.1

Type RM Length L Ch R = 1 ,39994.1 ,136.9,133.3,129.9
XS GIS Cut Line= 4
     1782511.681      300270.346     1782624.528      300285.971
     1782704.678       300300.67     1782873.081      300372.719
#Sta/Elev= 29
       0 1312.85    28.5 1311.05      38 1310.52    47.5 1310.18    85.4  1309.8
   104.4 1309.71   113.9  1309.4     123 1307.76     132  1303.7   141.1 1297.95
   148.9 1294.21   150.1 1293.63   159.2 1292.85   163.9 1294.15   168.2 1295.34
   177.3 1299.82   186.4 1304.14   195.4 1307.22     205  1308.9   214.7 1309.96
   224.3 1310.48   243.6 1310.56   253.2 1311.01   272.5 1312.64   282.2 1313.29
   301.5 1314.28   330.4 1315.89   349.7 1317.16   378.6 1319.25
#Mann= 3 , 0 , 0
       0      .1       0   148.9    .045       0   163.9      .1       0
Bank Sta=148.9,163.9
XS Rating Curve= 0 ,0
Exp/Cntr=0.3,0.1

Type RM Length L Ch R = 1 ,39860.8 ,102.8,103.8,104.3
XS GIS Cut Line= 4
     1782417.931       300424.86     1782633.208       300424.86
     1782747.792      300430.068     1782942.236      300435.277
#Sta/Elev= 30
       0 1321.26    39.1  1316.4    88.1 1311.51    97.8 1310.82   107.6  1310.6
   166.4    1310   176.1 1308.51   185.9 1304.82   205.5 1293.76   215.3 1288.74
   224.8 1285.13   234.4 1283.01   243.6 1282.24     244 1282.21   253.5 1282.33
   258.6 1283.12   263.1 1283.82   272.6 1288.44   282.2 1294.57   291.8 1299.86
   301.3 1303.79   310.9 1306.42   320.4  1307.6   349.4 1309.59   398.1 1311.85
   417.5 1313.87   446.7 1317.78   485.6 1321.39     505 1322.72   524.5  1323.5
#Mann= 3 , 0 , 0
       0      .1       0   243.6    .045       0   258.6      .1       0
Bank Sta=243.6,258.6
XS Rating Curve= 0 ,0
Exp/Cntr=0.3,0.1

Type RM Length L Ch R = 1 ,39757   ,247.4,253.4,257.1
XS GIS Cut Line= 4
     1782529.851      300519.404     1782645.476      300527.216
     1782712.143      300532.425     1782840.268      300540.237
#Sta/Elev= 25
       0 1309.08    19.3 1307.27      29 1306.48    48.3 1305.06    57.9 1303.64
    67.6 1301.25    86.9 1295.64    96.6  1292.9   106.2 1289.99   115.9 1286.81
   125.4 1283.43     135 1280.44   136.5 1280.25   144.6 1279.21   151.5 1280.92
   154.1 1281.56   173.2 1292.31   182.8 1296.66   191.9 1299.93   201.1 1301.69
   237.8 1303.69   274.4 1305.31   283.6 1305.81   292.8 1306.53   311.1 1308.34
#Mann= 3 , 0 , 0
       0      .1       0   136.5    .045       0   151.5      .1       0
Bank Sta=136.5,151.5
XS Rating Curve= 0 ,0
Exp/Cntr=0.3,0.1

Type RM Length L Ch R = 1 ,39503.6 ,153.6,145.7,137.3
XS GIS Cut Line= 4
     1782430.589      300703.931     1782532.586      300729.972
      1782606.37      300751.674     1782749.599      300789.651
#Sta/Elev= 29
       0 1316.86     9.6 1316.88    19.1 1316.38    28.7 1314.18    38.3 1309.75
    47.8  1303.3    57.4 1295.98      67 1288.93    76.6 1283.12    86.1 1279.11
    95.7 1276.03   114.9 1270.18   124.5 1267.06   129.9 1265.98   134.1 1265.14
   143.7 1264.54   144.9 1264.78   153.3 1266.48     163  1269.5   172.6 1272.08
   182.2 1274.01     210 1279.01   219.2 1280.77   237.8 1284.55     247 1286.32
   256.3 1287.16   265.5 1287.35   293.3 1287.37   330.4 1287.66
#Mann= 3 , 0 , 0
       0      .1       0   129.9    .045       0   144.9      .1       0
Bank Sta=129.9,144.9
XS Rating Curve= 0 ,0
Exp/Cntr=0.3,0.1

Type RM Length L Ch R = 1 ,39357.9 ,288.2,274.8,261.4
XS GIS Cut Line= 2
     1782319.279      300900.605        1782825.      300862.196
#Sta/Elev= 30
       0 1327.84    29.3 1326.14    58.5  1323.2    68.3  1321.5      78 1318.57
   107.3 1308.25     117 1303.42   126.8 1296.68     156 1273.76   165.8 1266.71
   175.6 1261.56   185.3 1258.27   195.1 1255.89   204.8 1254.04   221.4 1251.67
   224.3 1251.32   234.1  1251.3   236.4 1251.77   243.8 1253.27   253.6 1256.92
   263.3 1260.97   282.8 1268.56   292.6 1272.17   302.4 1275.48   312.1 1277.75
   321.9  1278.6   380.4 1281.35   468.2 1283.68   487.7 1284.56   507.2 1285.88
#Mann= 3 , 0 , 0
       0      .1       0   221.4    .045       0   236.4      .1       0
Bank Sta=221.4,236.4
XS Rating Curve= 0 ,0
Exp/Cntr=0.3,0.1

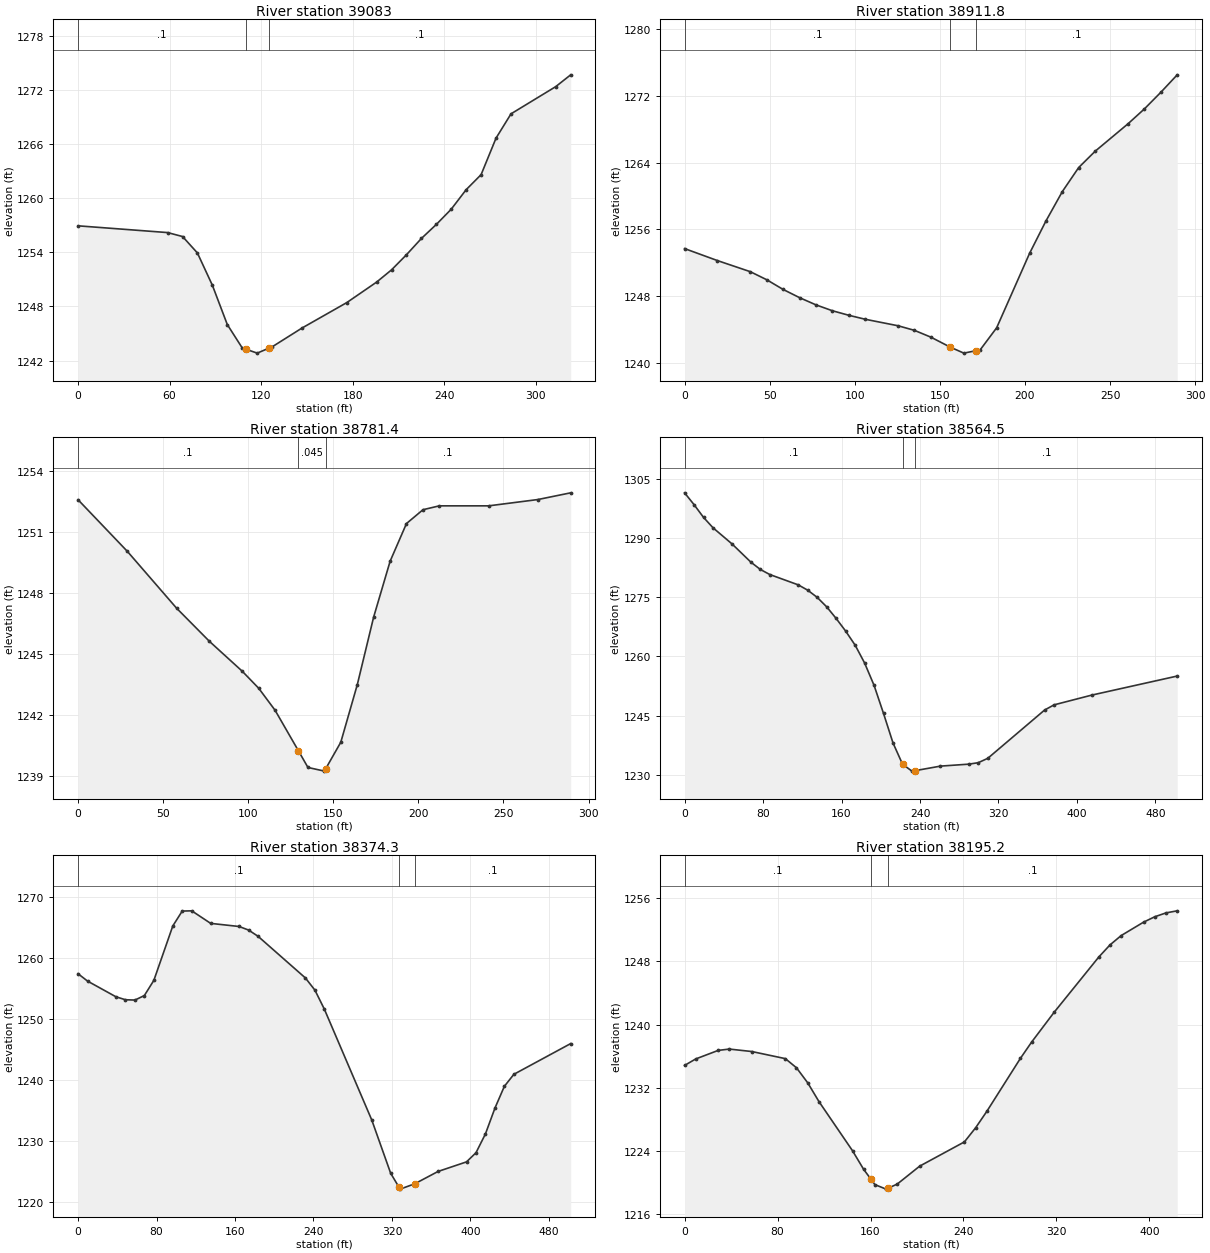
Type RM Length L Ch R = 1 ,39083   ,147.9,171.2,193.6
XS GIS Cut Line= 2
     1782531.498      301209.186      1782785.12      301009.501
#Sta/Elev= 25
       0 1256.95    58.7  1256.2    68.5 1255.76    78.2 1253.94      88 1250.36
    97.8 1245.99   107.6 1243.39   109.9 1243.26   117.4 1242.82   124.9 1243.36
   127.2 1243.52   146.7  1245.6   176.1 1248.43   195.6  1250.7   205.4 1252.06
   215.2 1253.74     225 1255.55   234.8 1257.11   244.5 1258.79   254.3 1260.96
   264.1 1262.63   273.9 1266.69   283.7 1269.38     313  1272.4   322.8 1273.71
#Mann= 3 , 0 , 0
       0      .1       0   109.9    .045       0   124.9      .1       0
Bank Sta=109.9,124.9
XS Rating Curve= 0 ,0
Exp/Cntr=0.3,0.1

Type RM Length L Ch R = 1 ,38911.8 ,115.7,130.4,146
XS GIS Cut Line= 2
      1782566.81      301227.679     1782844.802      301308.648
#Sta/Elev= 27
       0 1253.68    19.3 1252.24    38.6 1250.91    48.3 1249.94    57.9 1248.78
    67.6 1247.79    77.2 1246.93    86.9 1246.22    96.5 1245.68   106.2  1245.2
   125.5 1244.42   135.1 1243.87   144.8 1243.05     156 1241.87   164.1 1241.14
     171 1241.42   173.7 1241.53   183.4 1244.18   202.7 1253.09   212.3 1256.97
     222 1260.52   231.6  1263.4   241.3 1265.36   260.6 1268.65   270.2 1270.43
   279.9 1272.43   289.5 1274.52
#Mann= 3 , 0 , 0
       0      .1       0     156    .045       0     171      .1       0
Bank Sta=156,171
XS Rating Curve= 0 ,0
Exp/Cntr=0.3,0.1

Type RM Length L Ch R = 1 ,38781.4 ,235.8,216.9,196.3
XS GIS Cut Line= 2
     1782574.408      301238.197     1782733.037      301480.421
#Sta/Elev= 21
       0 1252.57      29 1250.03    57.9 1247.24    77.2 1245.61    96.5 1244.14
   106.2  1243.3   115.8 1242.22   129.5 1240.23   135.1 1239.41   144.8 1239.23
  145.48 1239.34   154.4 1240.65   164.1 1243.48   173.7  1246.8   183.4 1249.55
     193  1251.4   202.7 1252.08   212.3 1252.27   241.3 1252.27   270.2 1252.58
   289.5 1252.91
#Mann= 3 , 0 , 0
       0      .1       0   129.5    .045       0  145.48      .1       0
Bank Sta=129.5,145.48
XS Rating Curve= 0 ,0
Exp/Cntr=0.3,0.1

Type RM Length L Ch R = 1 ,38564.5 ,194.3,190.3,186.1
XS GIS Cut Line= 2
     1782278.565      301450.144     1782777.722      301505.779
#Sta/Elev= 30
       0 1301.48     9.7 1298.47    19.3 1295.26      29 1292.61    48.3 1288.54
    67.6  1283.9    77.3 1282.04    86.9 1280.76   115.9 1278.14   125.6 1276.78
   135.2 1274.97   144.9 1272.56   154.5 1269.63   164.2 1266.42   173.9 1262.84
   183.5 1258.34   193.2 1252.64   202.8 1245.54   212.5 1238.04   222.2 1232.66
   231.8 1230.91   235.3 1231.04   260.8 1232.18   289.8 1232.68   299.4 1233.05
   309.1 1234.16     367  1246.4   376.7 1247.72   415.3  1250.2   502.2 1255.02
#Mann= 3 , 0 , 0
       0      .1       0   222.2    .045       0   235.3      .1       0
Bank Sta=222.2,235.3
XS Rating Curve= 0 ,0
Exp/Cntr=0.3,0.1

Type RM Length L Ch R = 1 ,38374.3 ,192,179.1,164.5
XS GIS Cut Line= 2
     1782214.969      301679.177     1782716.318      301649.142
#Sta/Elev= 30
       0  1257.4     9.7 1256.19    38.6 1253.62    48.3 1253.13      58 1253.08
    67.6 1253.82    77.3 1256.32    96.6 1265.24   106.2 1267.68   115.9 1267.72
   135.2 1265.66   164.2 1265.15   173.9 1264.56   183.5 1263.54   231.8  1256.7
   241.5  1254.7   251.1 1251.58   299.4 1233.41   318.7 1224.66  327.33 1222.33
   328.3 1222.06   343.3 1222.94     367 1224.96     396 1226.53   405.7 1228.04
   415.3 1231.12     425 1235.36   434.6 1238.93   444.3  1240.9   502.2 1245.94
#Mann= 3 , 0 , 0
       0      .1       0  327.33    .045       0   343.3      .1       0
Bank Sta=327.33,343.3
XS Rating Curve= 0 ,0
Exp/Cntr=0.3,0.1

Type RM Length L Ch R = 1 ,38195.2 ,147.5,146.2,145.2
XS GIS Cut Line= 2
     1782460.539       301929.92     1782794.472      301668.826
#Sta/Elev= 30
       0 1234.84     9.6 1235.66    28.9 1236.74    38.5 1236.91    57.8  1236.6
    86.7  1235.7    96.3 1234.54     106 1232.63   115.6 1230.27   144.5 1224.04
   154.1 1221.68     160 1220.51   163.8 1219.75   173.4 1219.18     175 1219.29
     183 1219.82   202.3 1222.09   240.8 1225.16   250.5 1226.96   260.1 1229.03
     289 1235.74   298.6 1237.79   317.9 1241.55   356.4 1248.56   366.1  1250.1
   375.7 1251.28     395 1252.98   404.6 1253.66   414.3 1254.15   423.9 1254.41
#Mann= 3 , 0 , 0
       0      .1       0     160    .045       0     175      .1       0
Bank Sta=160,175
XS Rating Curve= 0 ,0
Exp/Cntr=0.3,0.1

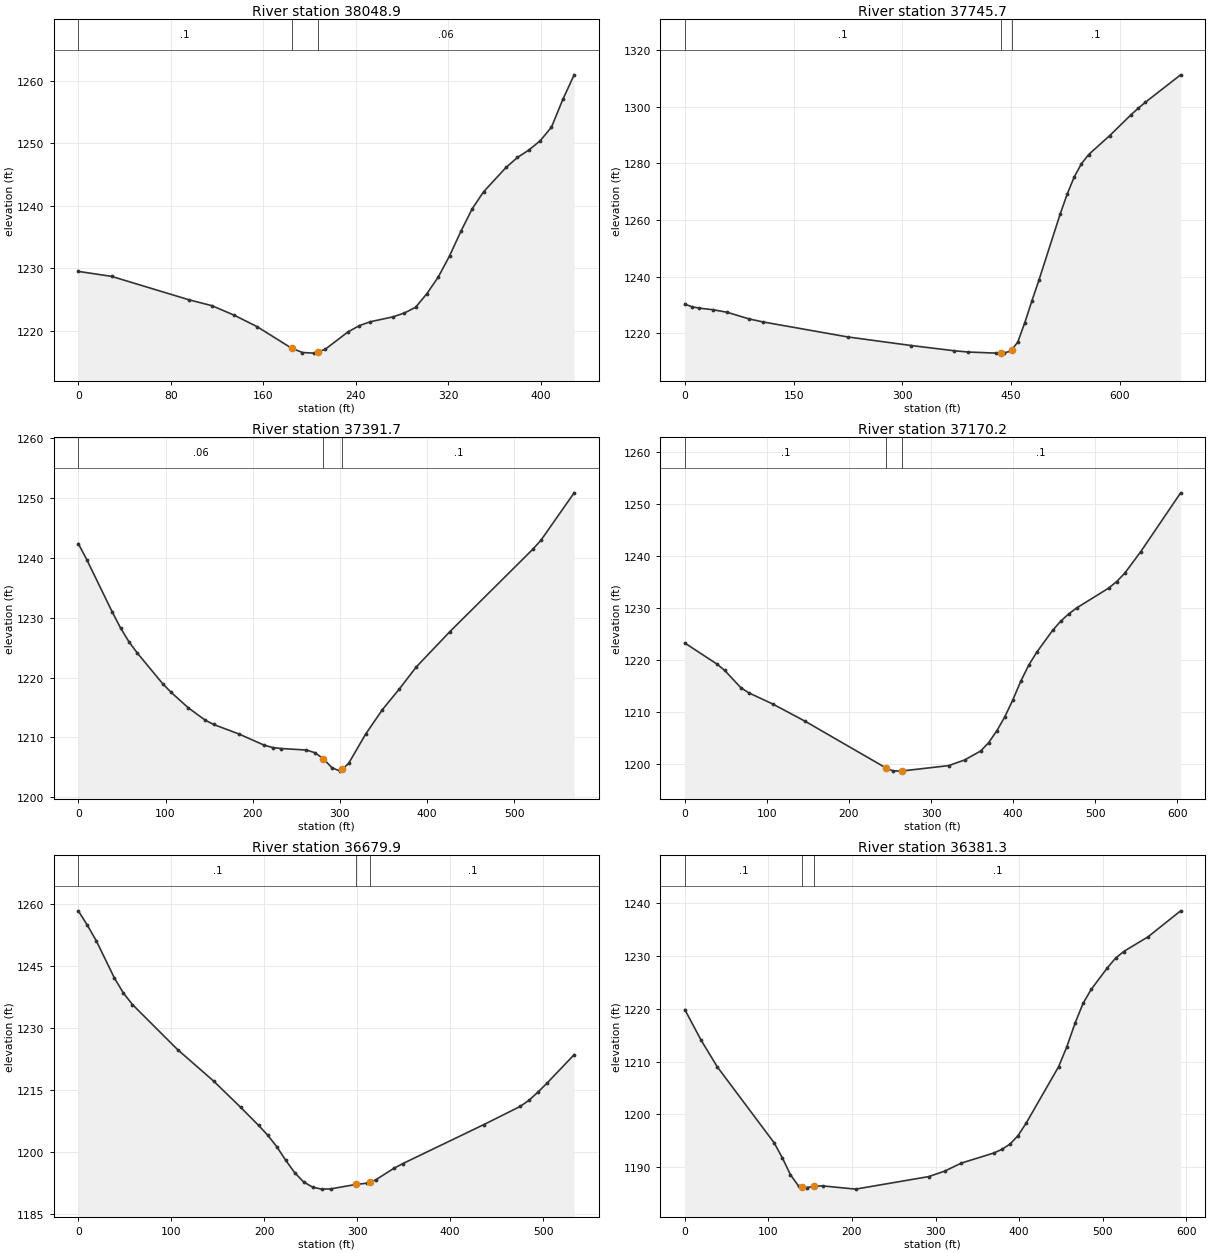
Type RM Length L Ch R = 1 ,38048.9 ,269,303.3,328.4
XS GIS Cut Line= 3
     1782537.901      301958.823      1782631.13      301981.219
     1782884.776      301765.594
#Sta/Elev= 30
       0 1229.51    28.8 1228.71    95.9 1224.95   115.5 1224.02     135 1222.48
   154.6 1220.66   184.4 1217.21   193.8 1216.52   203.6 1216.42   207.61216.665
   213.4 1217.02     233 1219.79   242.8 1220.81   252.6 1221.45   272.1 1222.23
   281.9 1222.84   291.7 1223.77   301.5 1225.96   311.3 1228.61   321.1 1232.02
   330.9 1235.95   340.7 1239.56   350.5 1242.27     370 1246.18   379.8 1247.76
   389.6 1248.94   399.4 1250.43   409.2 1252.61     419 1257.06   428.8 1260.99
#Mann= 3 , 0 , 0
       0      .1       0   184.4    .045       0   207.6     .06       0
Bank Sta=184.4,207.6
XS Rating Curve= 0 ,0
Exp/Cntr=0.3,0.1

Type RM Length L Ch R = 1 ,37745.7 ,360.1,353.9,356
XS GIS Cut Line= 3
     1782494.368      301956.176     1782690.288      302044.414
     1783128.005      302211.948
#Sta/Elev= 30
       0  1230.3     9.8 1229.39    19.5 1228.91    39.1 1228.32    58.6 1227.43
    87.9 1225.14   107.4 1224.05   224.6 1218.74   312.5  1215.7   371.1 1213.88
   390.6 1213.42   429.7 1213.03   435.9 1213.05   439.4 1213.06   449.2 1213.73
   450.9 1214.27     459 1216.87   468.7 1223.72   478.5  1231.4   488.3 1238.82
   517.6 1262.12   527.3 1269.19   537.1 1275.27   546.9 1279.84   556.6    1283
   585.9 1289.76   615.2 1297.08     625 1299.35   634.7 1301.43   683.6 1311.17
#Mann= 3 , 0 , 0
       0      .1       0   435.9    .045       0   450.9      .1       0
Bank Sta=435.9,450.9
XS Rating Curve= 0 ,0
Exp/Cntr=0.3,0.1

Type RM Length L Ch R = 1 ,37391.7 ,231.8,221.6,210.9
XS GIS Cut Line= 3
        1782377.      302165.957     1782719.652      302347.269
     1782881.728      302428.267
#Sta/Elev= 30
       0 1242.41     9.7 1239.73    38.8 1231.01    48.5 1228.29    58.2 1225.97
    67.8 1224.09    96.9 1218.96   106.6 1217.52     126 1214.97   145.4  1212.9
   155.1 1212.17   184.1 1210.58   213.2  1208.7   222.9 1208.31   232.6 1208.14
   261.7 1207.89   271.4 1207.44   281.1 1206.43   290.8 1204.94   300.4 1204.36
  302.92 1204.69   310.1 1205.66   329.5 1210.53   348.9 1214.66   368.3 1218.11
   387.7 1221.79   425.8 1227.63   521.2 1241.45   530.7 1242.98   568.8 1250.91
#Mann= 3 , 0 , 0
       0     .06       0   281.1    .045       0  302.92      .1       0
Bank Sta=281.1,302.92
XS Rating Curve= 0 ,0
Exp/Cntr=0.3,0.1

Type RM Length L Ch R = 1 ,37170.2 ,493.3,490.3,490.5
XS GIS Cut Line= 2
     1782292.788      302487.984     1782896.867         302501.
#Sta/Elev= 30
       0 1223.28      39 1219.27    48.7 1218.02    68.2 1214.72      78 1213.72
   107.2 1211.58   146.2 1208.31   245.7 1199.26   253.4 1198.76   263.1  1198.7
  264.09 1198.72   321.6 1199.76   341.1 1200.85   360.6 1202.57   370.3 1204.18
   380.1 1206.41   389.8 1209.08   399.6 1212.32   409.3 1215.92   419.1 1219.04
   428.8  1221.5   448.3 1225.73     458 1227.46   467.8 1228.87   477.5 1230.01
   516.5 1233.82   526.3 1235.08     536 1236.66   555.5 1240.79   604.2  1252.1
#Mann= 3 , 0 , 0
       0      .1       0   245.7    .045       0  264.09      .1       0
Bank Sta=245.7,264.09
XS Rating Curve= 0 ,0
Exp/Cntr=0.3,0.1

Type RM Length L Ch R = 1 ,36679.9 ,293.9,298.6,296.9
XS GIS Cut Line= 2
     1782295.674      302868.173     1782824.949      302934.289
#Sta/Elev= 30
       0 1258.42     9.7 1254.94    19.4 1251.14    38.8 1242.17    48.5 1238.53
    58.2 1235.76   106.7 1224.87   145.5 1217.25   174.6  1210.9     194  1206.5
   203.7 1204.16   213.4 1201.39     223 1198.12   232.8 1195.06   242.4 1192.84
   252.2 1191.56   261.8  1191.1   271.5 1191.16   299.2 1192.26   310.3 1192.53
   314.2 1192.86     320 1193.35   339.4 1196.13   349.1 1197.28   436.4 1206.73
   475.2 1211.09   484.9 1212.61   494.6  1214.6   504.3 1216.76   533.4 1223.63
#Mann= 3 , 0 , 0
       0      .1       0   299.2    .045       0   314.2      .1       0
Bank Sta=299.2,314.2
XS Rating Curve= 0 ,0
Exp/Cntr=0.3,0.1

Type RM Length L Ch R = 1 ,36381.3 ,397.1,395.2,393.3
XS GIS Cut Line= 2
     1782374.637      303161.922     1782967.064      303190.053
#Sta/Elev= 30
       0 1219.86    19.4 1214.08    38.9    1209     107  1194.6   116.7 1191.78
   126.4 1188.58   136.1 1186.44   140.1 1186.32   145.8 1186.15   155.1 1186.43
   165.3 1186.47   204.2 1185.86   291.7 1188.23   311.1 1189.28   330.6 1190.78
   369.5 1192.69   379.2 1193.38   388.9 1194.37   398.6 1195.99   408.4 1198.37
   447.2 1209.05     457 1212.82   466.7 1217.23   476.4 1221.02   486.1 1223.66
   505.6 1227.78   515.3 1229.58     525 1230.84   554.2 1233.63   593.1 1238.54
#Mann= 3 , 0 , 0
       0      .1       0   140.1    .045       0   155.1      .1       0
Bank Sta=140.1,155.1
XS Rating Curve= 0 ,0
Exp/Cntr=0.3,0.1

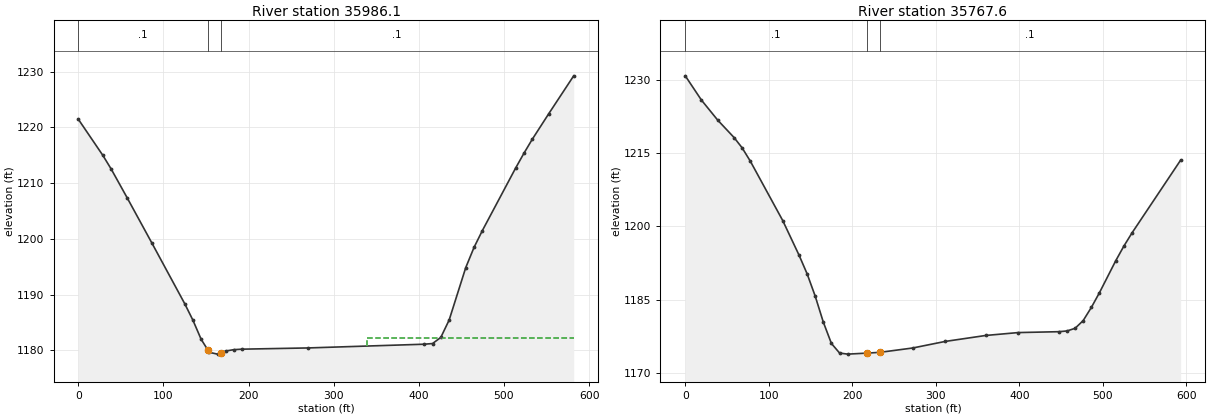
Type RM Length L Ch R = 1 ,35986.1 ,227.3,218.4,208.4
XS GIS Cut Line= 3
     1782339.915      303552.547     1782570.415      303540.246
     1782919.373      303502.052
#Sta/Elev= 28
       0 1221.46    28.8 1214.98    38.5 1212.55    57.7 1207.27    86.6 1199.19
     125 1188.35   134.6  1185.4   144.3 1181.96   152.3 1180.01   153.9 1179.62
   163.5  1179.3   167.3 1179.52   173.1 1179.86   182.7  1180.1   192.4 1180.19
   269.8 1180.41   406.4 1181.08   416.1  1181.2   425.8  1182.3   435.6 1185.42
   455.1 1194.83   464.9 1198.48   474.6 1201.47   513.6 1212.67   523.4 1215.34
   533.1 1217.83   552.6 1222.45   581.9 1229.25
#Mann= 3 , 0 , 0
       0      .1       0   152.3    .045       0   167.3      .1       0
#XS Ineff= 2 , 0
                           338.7         1182.16
Permanent Ineff=
       F       F
Bank Sta=152.3,167.3
XS Rating Curve= 0 ,0
Exp/Cntr=0.3,0.1

Type RM Length L Ch R = 1 ,35767.6 ,221.7,232.4,243.1
XS GIS Cut Line= 2
     1782332.592      303845.791     1782864.096      303582.279
#Sta/Elev= 30
       0 1230.75    19.4 1225.79    38.9  1221.7    58.4 1218.16    68.1 1216.05
    77.8 1213.36   116.7 1201.21   136.2 1194.16   145.9 1190.34   155.6 1185.78
   165.3 1180.48     175 1176.12   184.8 1174.16   194.5 1173.94   217.9 1174.15
   232.9  1174.3   272.3 1175.19   311.2 1176.53   359.8 1177.75   398.7 1178.34
   447.4 1178.52   457.1 1178.67   466.8 1179.21   476.5 1180.79   486.3 1183.48
     496 1186.49   515.4 1192.98   525.2 1195.99   534.9 1198.67   593.2 1213.54
#Mann= 3 , 0 , 0
       0      .1       0   217.9    .045       0   232.9      .1       0
Bank Sta=217.9,232.9
XS Rating Curve= 0 ,0
Exp/Cntr=0.3,0.1