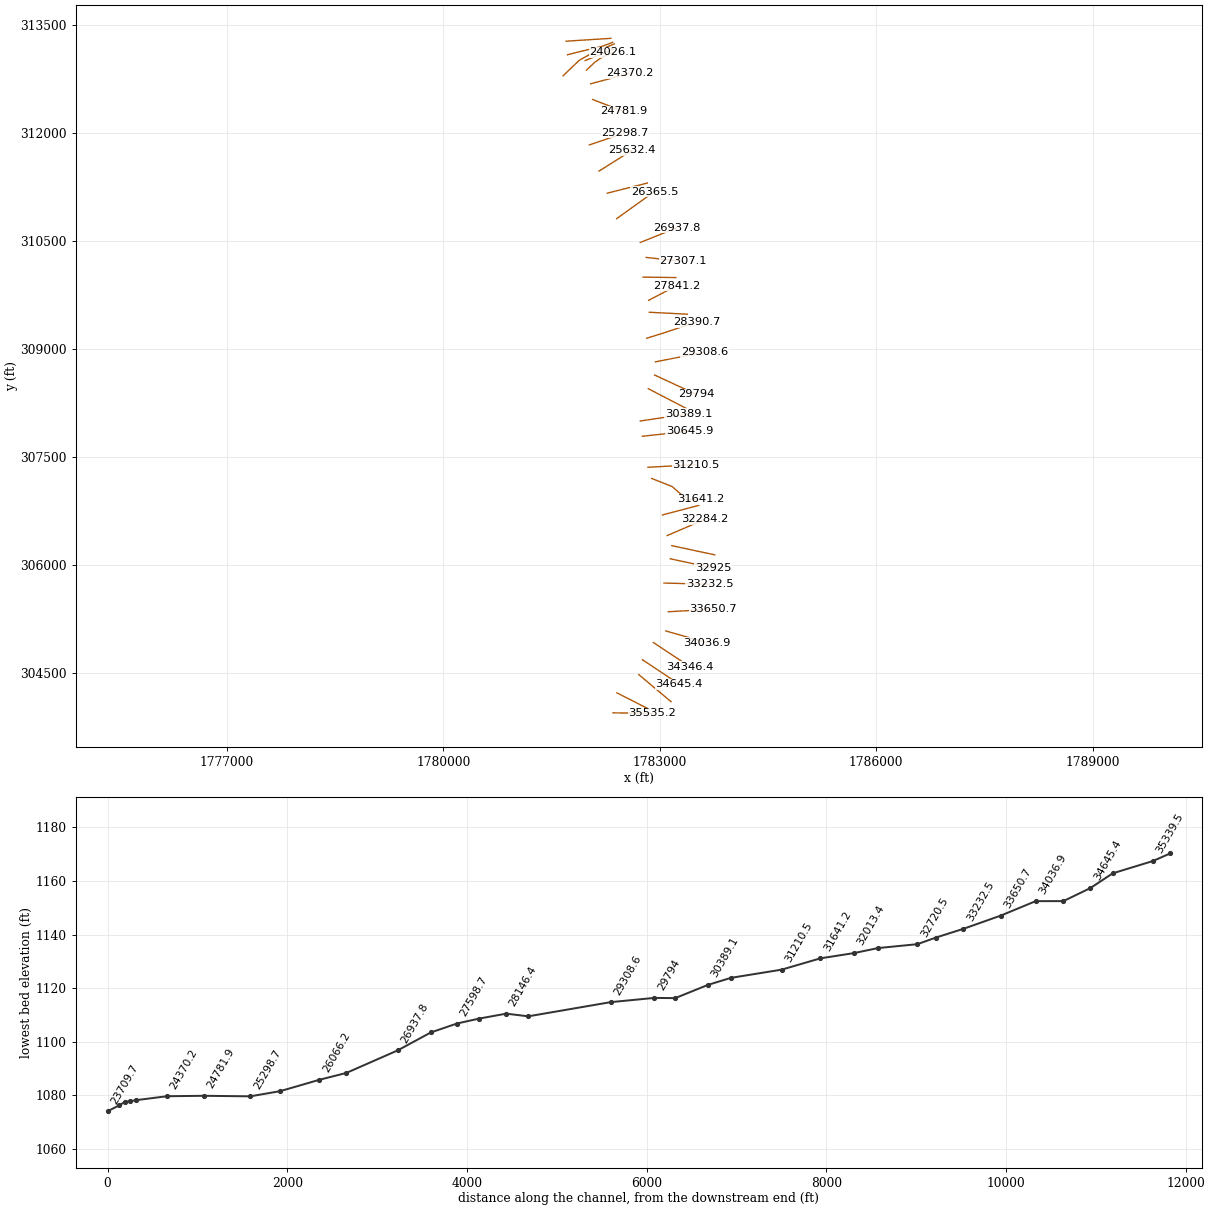
HEC-RAS study HusteadFrk.prj: HusteadFrk

--- HusteadFrk.g01 (geometry) --- (continued)

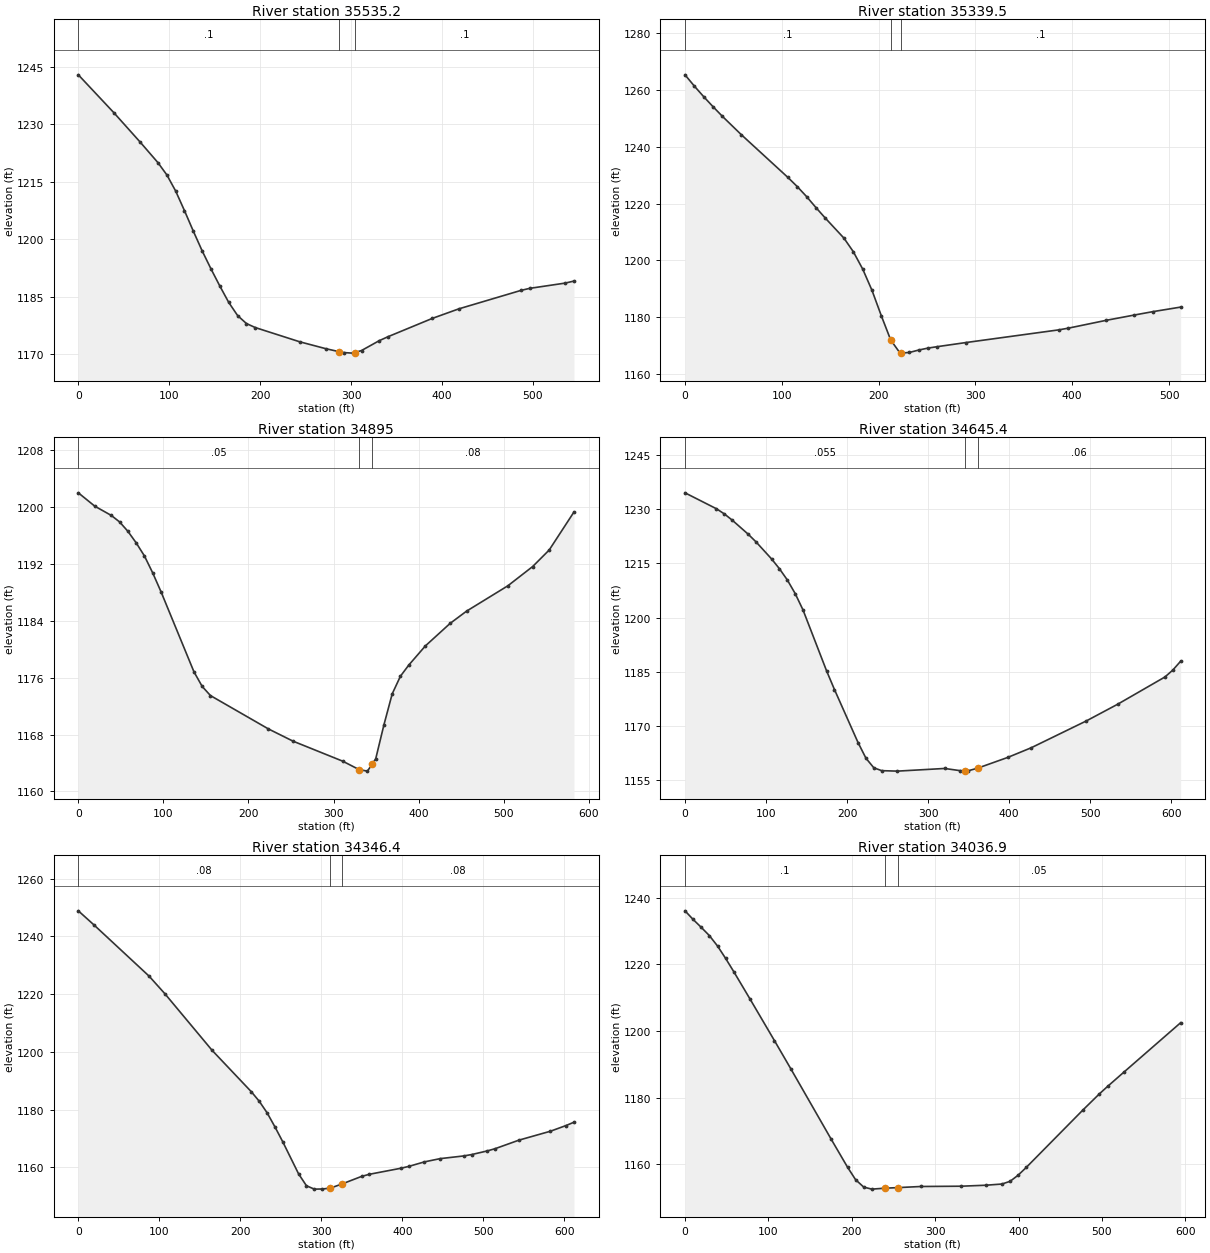
Type RM Length L Ch R = 1 ,35535.2 ,206.2,195.7,185.2
XS GIS Cut Line= 2
     1782351.152      303941.581     1782896.408      303934.262
#Sta/Elev= 30
       0 1242.86      39 1233.01    68.2 1225.28    87.6 1219.96    97.4 1216.76
   107.1 1212.56   116.8 1207.44   126.6 1202.06   136.3 1196.93   146.1 1192.19
   155.8 1187.74   165.5 1183.51   175.3 1180.07     185    1178   194.8 1176.95
   243.4 1173.26   272.6 1171.43   287.3 1170.65   292.1 1170.43   301.9 1170.29
  304.25 1170.43   311.6 1170.97   331.1 1173.54   340.8 1174.58   389.5 1179.35
   418.7 1181.84   486.9 1186.64   496.6 1187.18   535.6 1188.55   545.3 1189.08
#Mann= 3 , 0 , 0
       0      .1       0   287.3    .045       0  304.25      .1       0
Bank Sta=287.3,304.25
XS Rating Curve= 0 ,0
Exp/Cntr=0.3,0.1

Type RM Length L Ch R = 1 ,35339.5 ,448.6,444.5,439.6
XS GIS Cut Line= 2
     1782404.556      304219.532     1782860.519      303986.552
#Sta/Elev= 30
       0 1265.23     9.7 1261.25    19.3 1257.55      29 1254.01    38.6 1250.65
      58 1244.25   106.3 1229.17   115.9 1225.97   125.6 1222.44   135.3 1218.56
   144.9 1214.89   164.2 1207.83   173.9 1203.05   183.6 1196.94   193.2 1189.45
   202.9 1180.46   212.5 1172.03   222.2 1167.42     223 1167.44   231.9 1167.66
   241.5 1168.51   251.2  1169.2   260.8  1169.7   289.8 1171.12   386.4 1175.61
   396.1  1176.2   434.8 1178.93   463.7 1180.78     483 1181.98     512  1183.6
#Mann= 3 , 0 , 0
       0      .1       0   212.5    .045       0     223      .1       0
Bank Sta=212.5,223
XS Rating Curve= 0 ,0
Exp/Cntr=0.3,0.1

Type RM Length L Ch R = 1 ,34895   ,247.1,249.6,251.9
XS GIS Cut Line= 2
     1782708.508      304472.119     1783154.276      304097.121
#Sta/Elev= 30
       0 1201.98    19.4  1200.1    38.8  1198.8    48.5 1197.89    58.2 1196.58
      68 1194.95    77.7 1193.11    87.4 1190.73    97.1  1188.1   135.9 1176.82
   145.6 1174.76   155.3 1173.48   223.3  1168.8   252.4 1167.07   310.7 1164.26
   330.1 1163.07   339.8 1162.86   345.1  1163.8   349.5 1164.58   359.2 1169.38
   368.9 1173.72   378.6 1176.21   388.4 1177.77   407.8 1180.45   436.9 1183.62
   456.3 1185.35   504.8 1188.91     534 1191.62   553.4 1193.94   582.5 1199.28
#Mann= 3 , 0 , 0
       0     .05       0   330.1    .045       0   345.1     .08       0
Bank Sta=330.1,345.1
XS Rating Curve= 0 ,0
Exp/Cntr=0.3,0.1

Type RM Length L Ch R = 1 ,34645.4 ,298.1,299,298.8
XS GIS Cut Line= 2
     1782758.358      304678.799     1783268.091      304340.472
#Sta/Elev= 30
       0 1234.62    38.8  1230.2    48.6 1228.76    58.3 1227.03    77.7 1223.19
    87.4 1221.06   106.8 1216.28   116.5 1213.56   126.2 1210.46     136 1206.65
   145.7 1202.08   174.8 1185.16   184.5 1179.99   213.6 1165.27   223.4 1160.91
   233.1 1158.26   242.8 1157.47   262.2 1157.34   320.5 1158.08   339.9 1157.46
   346.2 1157.45   349.6 1157.44   361.2 1158.16   398.2 1161.13   427.3 1163.82
   495.3 1171.27   534.1 1175.92   592.4 1183.48   602.1 1185.39   611.8 1187.86
#Mann= 3 , 0 , 0
       0    .055       0   346.2    .045       0   361.2     .06       0
Bank Sta=346.2,361.2
XS Rating Curve= 0 ,0
Exp/Cntr=0.3,0.1

Type RM Length L Ch R = 1 ,34346.4 ,302.1,309.5,316.3
XS GIS Cut Line= 2
     1782910.244      304918.328     1783419.978         304580.
#Sta/Elev= 30
       0 1248.84    19.4 1243.94    87.4 1226.22   106.8 1220.16   165.1 1200.56
   213.6  1186.2   223.4  1182.9   233.1 1178.89   242.8    1174   252.5 1168.81
   271.9 1157.78   281.6 1153.67   291.3  1152.5     301 1152.55   310.9 1152.83
   325.9 1154.33   349.6  1156.9   359.3 1157.64   398.2 1159.73   407.9 1160.37
   427.3 1161.94   446.7 1163.06   475.8 1163.99   485.6 1164.47     505 1165.74
   514.7 1166.52   543.8 1169.45   582.7 1172.54   602.1 1174.52   611.8 1175.66
#Mann= 3 , 0 , 0
       0     .08       0   310.9    .045       0   325.9     .08       0
Bank Sta=310.9,325.9
XS Rating Curve= 0 ,0
Exp/Cntr=0.3,0.1

Type RM Length L Ch R = 1 ,34036.9 ,372.7,386.2,409.5
XS GIS Cut Line= 2
      1783082.36       305079.11     1783654.064      304916.278
#Sta/Elev= 29
       0 1236.09     9.7 1233.51    19.5 1231.12    29.2 1228.65      39 1225.52
    48.7  1221.8    58.5  1217.8      78 1209.58   107.2 1197.12   126.7 1188.71
   175.4 1167.43   194.9 1159.07   204.6  1155.3   214.4 1153.07   224.1 1152.47
   240.1 1152.76   255.1 1152.92   282.6 1153.26   331.3 1153.35   360.6 1153.64
     380    1154   389.8 1154.81   399.5 1156.65   409.3    1159   477.5 1176.32
     497  1181.1   506.7 1183.31   526.2 1187.59   594.4 1202.47
#Mann= 3 , 0 , 0
       0      .1       0   240.1    .045       0   255.1     .05       0
Bank Sta=240.1,255.1
XS Rating Curve= 0 ,0
Exp/Cntr=0.3,0.1

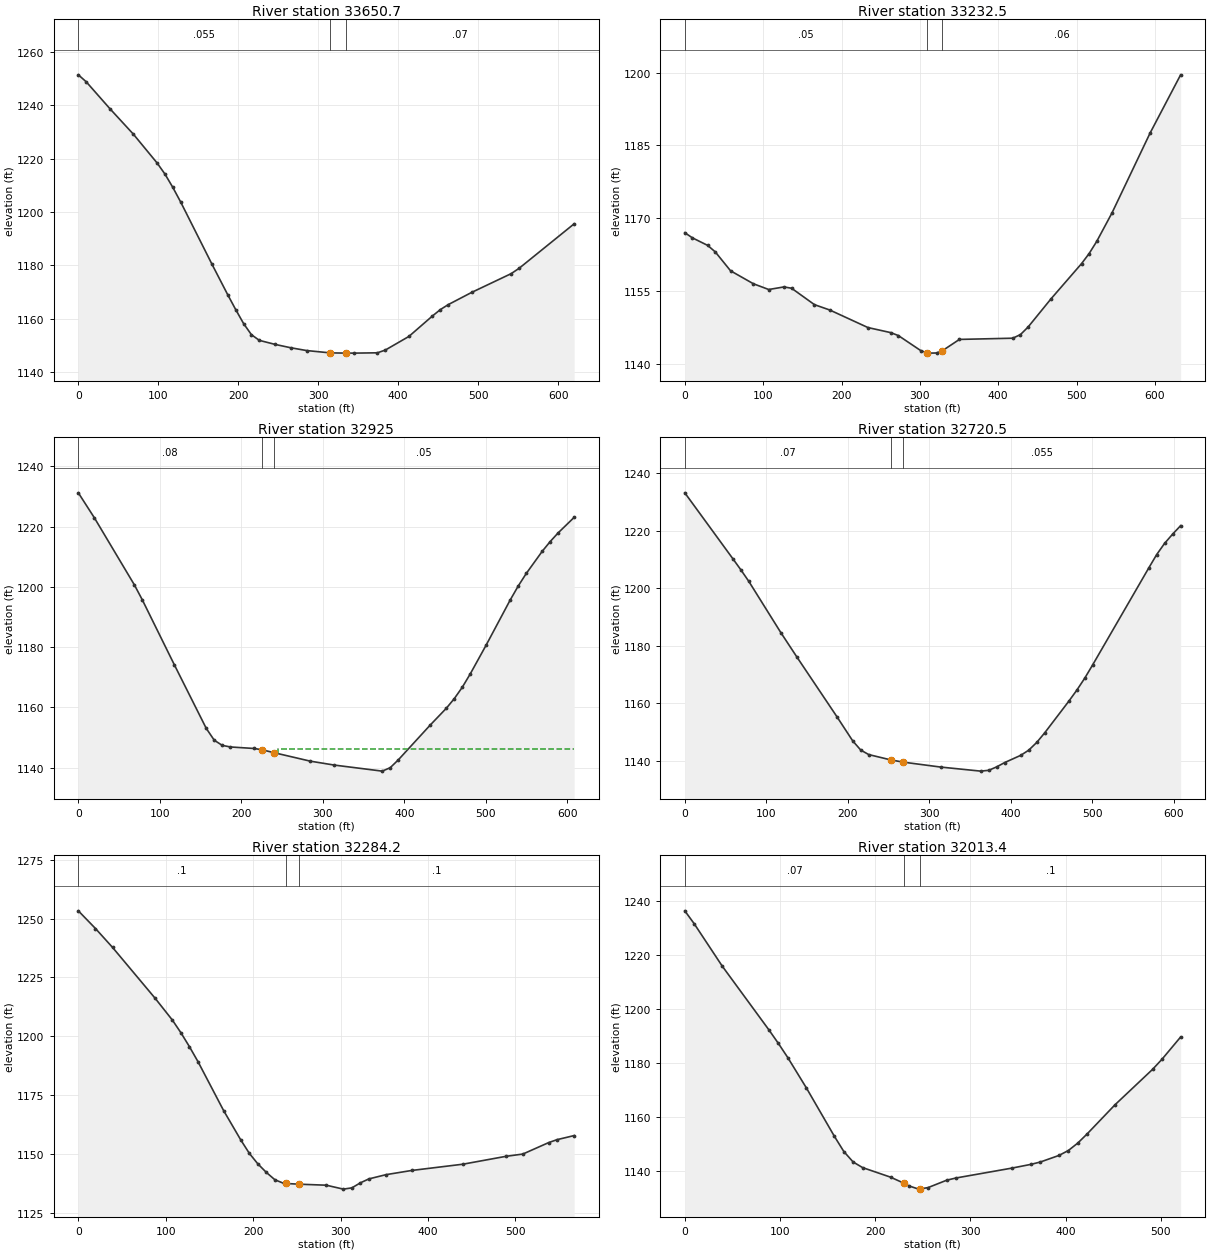
Type RM Length L Ch R = 1 ,33650.7 ,424.9,418.2,399.8
XS GIS Cut Line= 2
     1783116.335      305345.777     1783735.359      305381.673
#Sta/Elev= 30
       0 1251.39     9.8  1248.8    39.4 1238.73    68.9 1229.13    98.4  1218.4
   108.3 1214.22   118.1 1209.25     128 1203.73   167.3 1180.33     187  1168.9
   196.8 1163.43   206.7 1158.18   216.5 1154.01   226.4 1151.89   246.1 1150.38
   265.7 1149.12   285.4 1148.08     315  1147.2   334.6 1147.12   344.5 1147.11
     374 1147.23   383.8 1148.24   413.4 1153.36   442.9 1161.04   452.8 1163.43
   462.6 1165.28   492.1 1169.89   541.3 1176.89   551.2 1178.88   620.1 1195.57
#Mann= 3 , 0 , 0
       0    .055       0     315    .045       0   334.6     .07       0
Bank Sta=315,334.6
XS Rating Curve= 0 ,0
Exp/Cntr=0.3,0.1

Type RM Length L Ch R = 1 ,33232.5 ,311.4,307.5,303.3
XS GIS Cut Line= 2
     1783058.394      305744.499     1783691.016      305727.923
#Sta/Elev= 30
       0    1167     9.7 1165.94    29.2 1164.38    38.9 1163.04    58.4 1159.14
    87.6 1156.46   107.1 1155.28   126.6 1155.81   136.3 1155.54   165.5 1152.15
     185 1151.05   233.7 1147.43   262.9 1146.38   272.6 1145.77   301.8  1142.6
  308.93 1142.27   311.6 1142.15   321.3 1142.18   328.3  1142.6   350.5 1144.98
   418.6 1145.23   428.4 1145.98   438.1 1147.53   467.3 1153.34   506.3 1160.61
     516 1162.69   525.7  1165.2   545.2 1171.08   593.9 1187.59   632.8 1199.58
#Mann= 3 , 0 , 0
       0     .05       0  308.93    .045       0   328.3     .06       0
Bank Sta=308.93,328.3
XS Rating Curve= 0 ,0
Exp/Cntr=0.3,0.1

Type RM Length L Ch R = 1 ,32925   ,204.2,204.4,204.6
XS GIS Cut Line= 2
     1783144.686       306081.34     1783739.653      305953.967
#Sta/Elev= 30
       0 1231.22    19.6 1222.97    68.7 1200.71    78.5 1195.71   117.8 1174.16
     157 1153.04   166.8 1149.12   176.6 1147.42   186.5 1146.89   215.9 1146.38
   225.6 1145.94   240.6 1144.96   284.6 1142.18     314 1140.88   372.9 1138.87
   382.7 1140.01   392.6  1142.6   431.8 1154.16   451.4 1159.69   461.2 1162.88
   471.1 1166.69   480.9 1171.13   500.5 1180.73   529.9 1195.65   539.8 1200.31
   549.6 1204.45   569.2 1211.81     579 1215.05   588.8 1217.94   608.4 1223.08
#Mann= 3 , 0 , 0
       0     .08       0   225.6    .045       0   240.6     .05       0
#XS Ineff= 2 , 0
                          244.79         1146.06
Permanent Ineff=
       F       F
Bank Sta=225.6,240.6
XS Rating Curve= 0 ,0
Exp/Cntr=0.3,0.1

Type RM Length L Ch R = 1 ,32720.5 ,421.6,436.4,449.8
XS GIS Cut Line= 2
      1783165.78      306263.979     1783760.747      306136.606
#Sta/Elev= 30
       0 1233.14    58.9 1210.26    68.7 1206.42    78.5 1202.39   117.8 1184.58
   137.4 1176.14   186.5  1155.4   206.1 1146.91   215.9 1143.74   225.7 1142.17
   252.6 1140.33   267.6 1139.56     314 1137.83   363.1 1136.42   372.9  1136.7
   382.7  1137.9   392.6 1139.41   412.2 1141.91     422  1143.7   431.8 1146.38
   441.6 1149.72   471.1 1160.68   480.9 1164.51   490.7  1168.7   500.5 1173.36
   569.2 1206.98     579 1211.67   588.8 1215.61   598.6 1218.79   608.4 1221.73
#Mann= 3 , 0 , 0
       0     .07       0   252.6    .045       0   267.6    .055       0
Bank Sta=252.6,267.6
XS Rating Curve= 0 ,0
Exp/Cntr=0.3,0.1

Type RM Length L Ch R = 1 ,32284.2 ,274.1,270.8,266.3
XS GIS Cut Line= 2
     1783101.059       306404.32     1783622.092       306628.25
#Sta/Elev= 30
       0 1253.36    19.6 1245.84    39.1 1237.81      88 1216.09   107.6 1206.87
   117.3 1201.52   127.1 1195.56   136.9 1189.18   166.2 1168.37   185.8  1155.9
   195.6 1150.19   205.3 1145.73   215.1 1142.07   224.9 1138.94   234.7 1137.48
   237.5 1137.38   252.5 1137.08   283.6 1136.65   303.1 1134.98   312.9 1135.52
   322.7 1137.68   332.4 1139.34     352 1141.14   381.3 1142.92     440 1145.59
   488.9 1148.92   508.4  1149.9   537.8 1154.75   547.6 1156.03   567.1 1157.76
#Mann= 3 , 0 , 0
       0      .1       0   237.5    .045       0   252.5      .1       0
Bank Sta=237.5,252.5
XS Rating Curve= 0 ,0
Exp/Cntr=0.3,0.1

Type RM Length L Ch R = 1 ,32013.4 ,393.6,372.2,349.9
XS GIS Cut Line= 2
     1783036.206      306690.873     1783539.717      306823.517
#Sta/Elev= 30
       0 1236.36     9.8 1231.61    39.3 1215.85    88.4 1192.15    98.2  1187.2
   108.1 1181.93   127.7 1170.64   157.2 1152.63     167 1147.05   176.8 1143.16
   186.7 1141.08   216.1 1137.53   230.2 1135.27   235.8 1134.24   245.6 1133.09
  247.48 1133.19   255.4 1133.65   275.1 1136.41   284.9 1137.23   343.8 1140.91
   363.5 1142.28   373.3 1143.14     393  1145.6   402.8 1147.42   412.6 1150.15
   422.4 1153.53   451.9 1164.43   491.2 1177.52     501 1181.23   520.7 1189.54
#Mann= 3 , 0 , 0
       0     .07       0   230.2    .045       0  247.48      .1       0
Bank Sta=230.2,247.48
XS Rating Curve= 0 ,0
Exp/Cntr=0.3,0.1

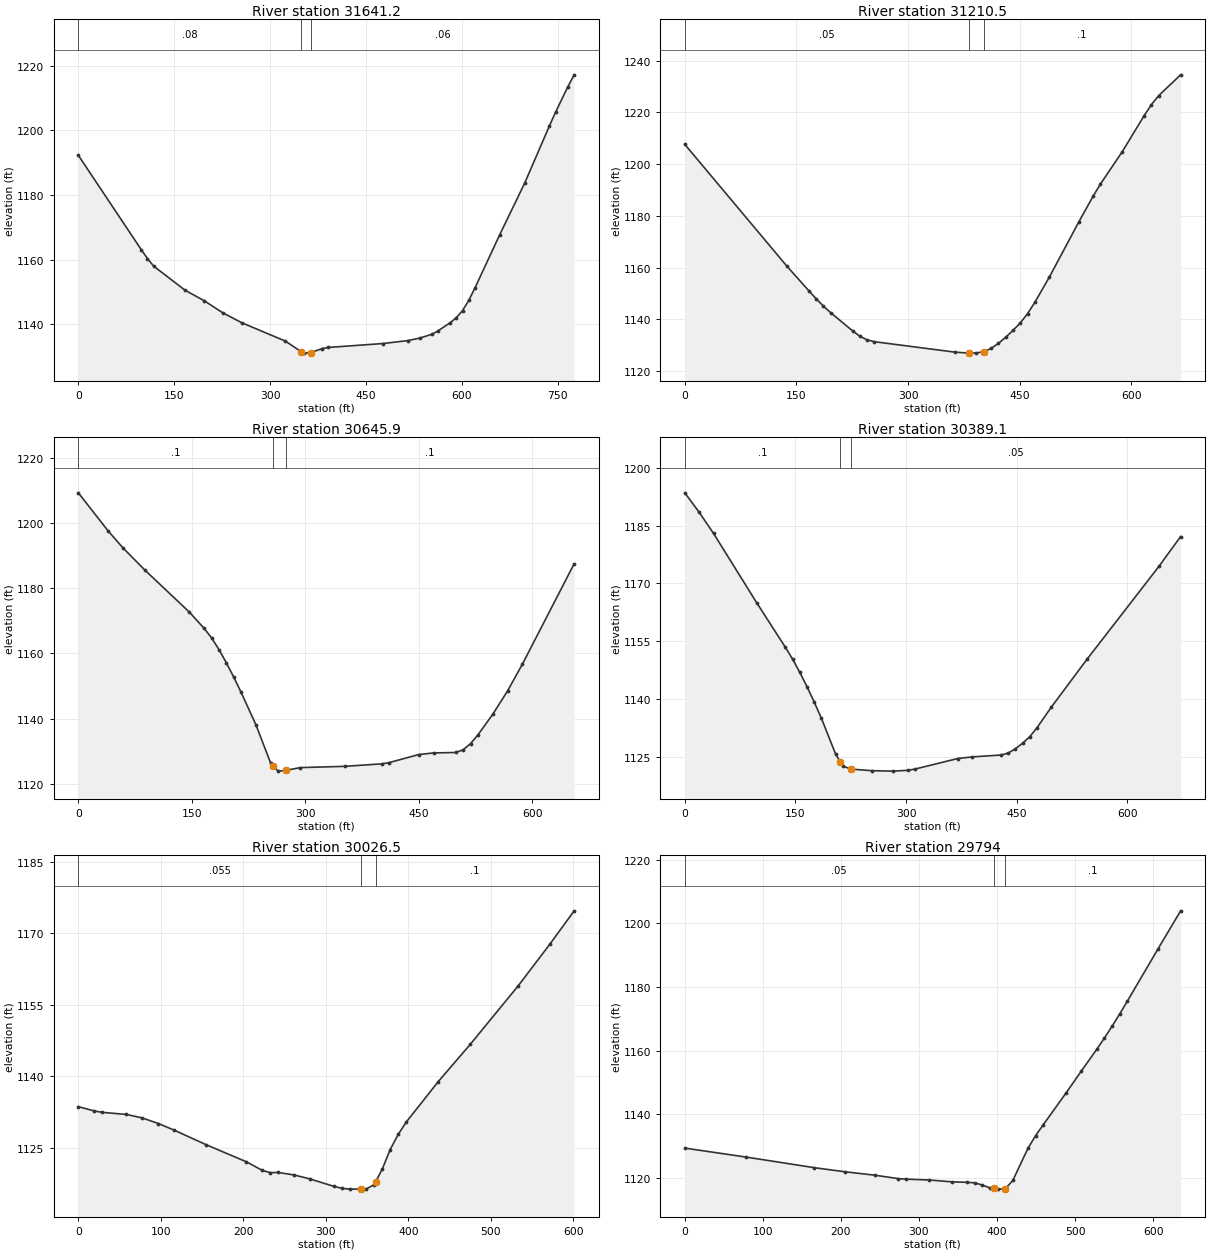
Type RM Length L Ch R = 1 ,31641.2 ,413,430.7,448
XS GIS Cut Line= 4
     1782886.691       307198.07     1783169.677      307085.223
     1783386.691      306897.723     1783570.718      306906.404
#Sta/Elev= 30
       0 1192.28    98.3 1163.16   108.1 1160.38   117.9 1158.02   167.1 1150.56
   196.6 1147.38     226  1143.6   255.5 1140.55   323.8 1134.86   348.9 1131.56
   352.5 1131.14   363.9 1131.32   381.1 1132.52   390.7 1132.89   476.7 1134.11
     515    1135   534.1 1135.78   553.2 1136.98   562.8 1138.02   581.9 1140.56
   591.4  1142.1   601.2 1144.31   610.8 1147.43   620.5 1151.28   659.3 1167.76
   698.1 1183.61   736.9 1201.33   746.6  1205.6     766 1213.54   775.7 1217.16
#Mann= 3 , 0 , 0
       0     .08       0   348.9    .045       0   363.9     .06       0
Bank Sta=348.9,363.9
XS Rating Curve= 0 ,0
Exp/Cntr=0.3,0.1

Type RM Length L Ch R = 1 ,31210.5 ,561.5,564.6,565.2
XS GIS Cut Line= 2
     1782835.198       307352.85     1783500.405      307389.946
#Sta/Elev= 30
       0 1207.61   137.2 1160.52   166.6 1151.04   176.4 1147.96   186.2 1145.12
     196 1142.56   225.4 1135.54   235.1 1133.47   244.9 1132.06   254.7 1131.34
   362.5 1127.32   382.1 1126.92   391.9 1126.99   401.7 1127.48   411.5 1128.72
   421.3 1130.66   431.1 1133.06   440.9 1135.68   450.7 1138.58   460.5 1142.16
   470.3 1146.54   489.9 1156.36   529.1 1177.47   548.7 1187.63   558.5 1192.29
   587.9 1204.83   617.2 1218.72     627    1223   636.8 1226.47   666.2 1234.49
#Mann= 3 , 0 , 0
       0     .05       0   382.1    .045       0   401.7      .1       0
Bank Sta=382.1,401.7
XS Rating Curve= 0 ,0
Exp/Cntr=0.3,0.1

Type RM Length L Ch R = 1 ,30645.9 ,254.9,256.8,258.5
XS GIS Cut Line= 2
     1782757.877      307783.945     1783409.178      307854.879
#Sta/Elev= 30
       0 1209.26    39.1 1197.66    58.7 1192.43      88 1185.54   146.7 1172.66
   166.2 1167.69     176 1164.76   185.8 1161.18   195.6  1157.1   205.4  1152.7
   215.1 1148.04   234.7 1138.07   254.2 1126.29   257.3 1125.52     264 1123.86
   273.8 1124.08   293.4 1124.94     352 1125.33   400.9 1126.09   410.7 1126.47
   449.8 1128.95   469.4 1129.44   498.7 1129.58   508.5 1130.41   518.3  1132.3
     528 1134.97   547.6 1141.29   567.2 1148.47   586.7 1156.64   655.2 1187.49
#Mann= 3 , 0 , 0
       0      .1       0   257.3    .045       0   273.8      .1       0
Bank Sta=257.3,273.8
XS Rating Curve= 0 ,0
Exp/Cntr=0.3,0.1

Type RM Length L Ch R = 1 ,30389.1 ,376.5,362.6,348
XS GIS Cut Line= 2
     1782728.797      307995.761     1783393.785      308095.392
#Sta/Elev= 30
       0 1193.53    19.5 1188.48      39 1182.98    97.4    1165   136.4  1153.4
   146.2 1150.31   155.9 1146.89   165.7 1143.18   175.4 1139.22   185.2 1134.98
   204.6  1125.6  211.06 1123.59   214.4 1122.55   225.1 1121.75   253.4 1121.34
   282.6 1121.22   302.1 1121.43   311.8 1121.74   370.3  1124.5   389.8 1124.92
   428.8  1125.4   438.5 1125.91   448.3 1127.02     458 1128.46   467.8 1130.17
   477.5 1132.46     497 1137.84   545.7 1150.35   643.2 1174.48   672.4 1182.17
#Mann= 3 , 0 , 0
       0      .1       0  211.06    .045       0   225.1     .05       0
Bank Sta=211.06,225.1
XS Rating Curve= 0 ,0
Exp/Cntr=0.3,0.1

Type RM Length L Ch R = 1 ,30026.5 ,231.7,232.6,233.8
XS GIS Cut Line= 2
     1782839.046      308444.749     1783371.999       308167.41
#Sta/Elev= 30
       0 1133.62    19.4 1132.71    29.1 1132.42    58.1 1131.99    77.5 1131.25
    96.9 1130.08   116.3 1128.67     155 1125.62   203.5 1122.05   222.9 1120.24
   232.6 1119.76   242.3  1119.8   261.6 1119.27     281 1118.42   310.1 1116.86
   319.8 1116.46   329.5  1116.3  342.53 1116.31   348.8 1116.32   358.5 1117.26
   360.4 1117.89   368.2 1120.48   377.9 1124.62   387.6 1127.79   397.3 1130.37
   436.1 1138.88   474.8 1146.68     533 1158.99   571.7 1167.81   600.8 1174.74
#Mann= 3 , 0 , 0
       0    .055       0  342.53    .045       0   360.4      .1       0
Bank Sta=342.53,360.4
XS Rating Curve= 0 ,0
Exp/Cntr=0.3,0.1

Type RM Length L Ch R = 1 ,29794   ,470.9,485.4,499.1
XS GIS Cut Line= 2
     1782926.174      308634.655     1783502.162      308366.972
#Sta/Elev= 30
       0 1129.29    78.2 1126.48   166.1 1123.12   205.2 1121.84   244.3 1120.74
   273.6 1119.68   283.4 1119.52   312.7 1119.26     342 1118.68   361.6 1118.53
   371.3 1118.37   381.1 1117.67   390.9 1116.78   395.8 1116.58   400.6 1116.38
   410.4 1116.44   410.8 1116.55   420.2  1119.1   439.7 1129.27   449.5 1133.24
   459.3 1136.67   488.6 1146.69   508.1 1153.57   527.7 1160.36   537.4 1163.86
   547.2 1167.56     557 1171.45   566.8 1175.47   605.8 1191.79   635.2 1203.95
#Mann= 3 , 0 , 0
       0     .05       0   395.8    .045       0   410.8      .1       0
Bank Sta=395.8,410.8
XS Rating Curve= 0 ,0
Exp/Cntr=0.3,0.1

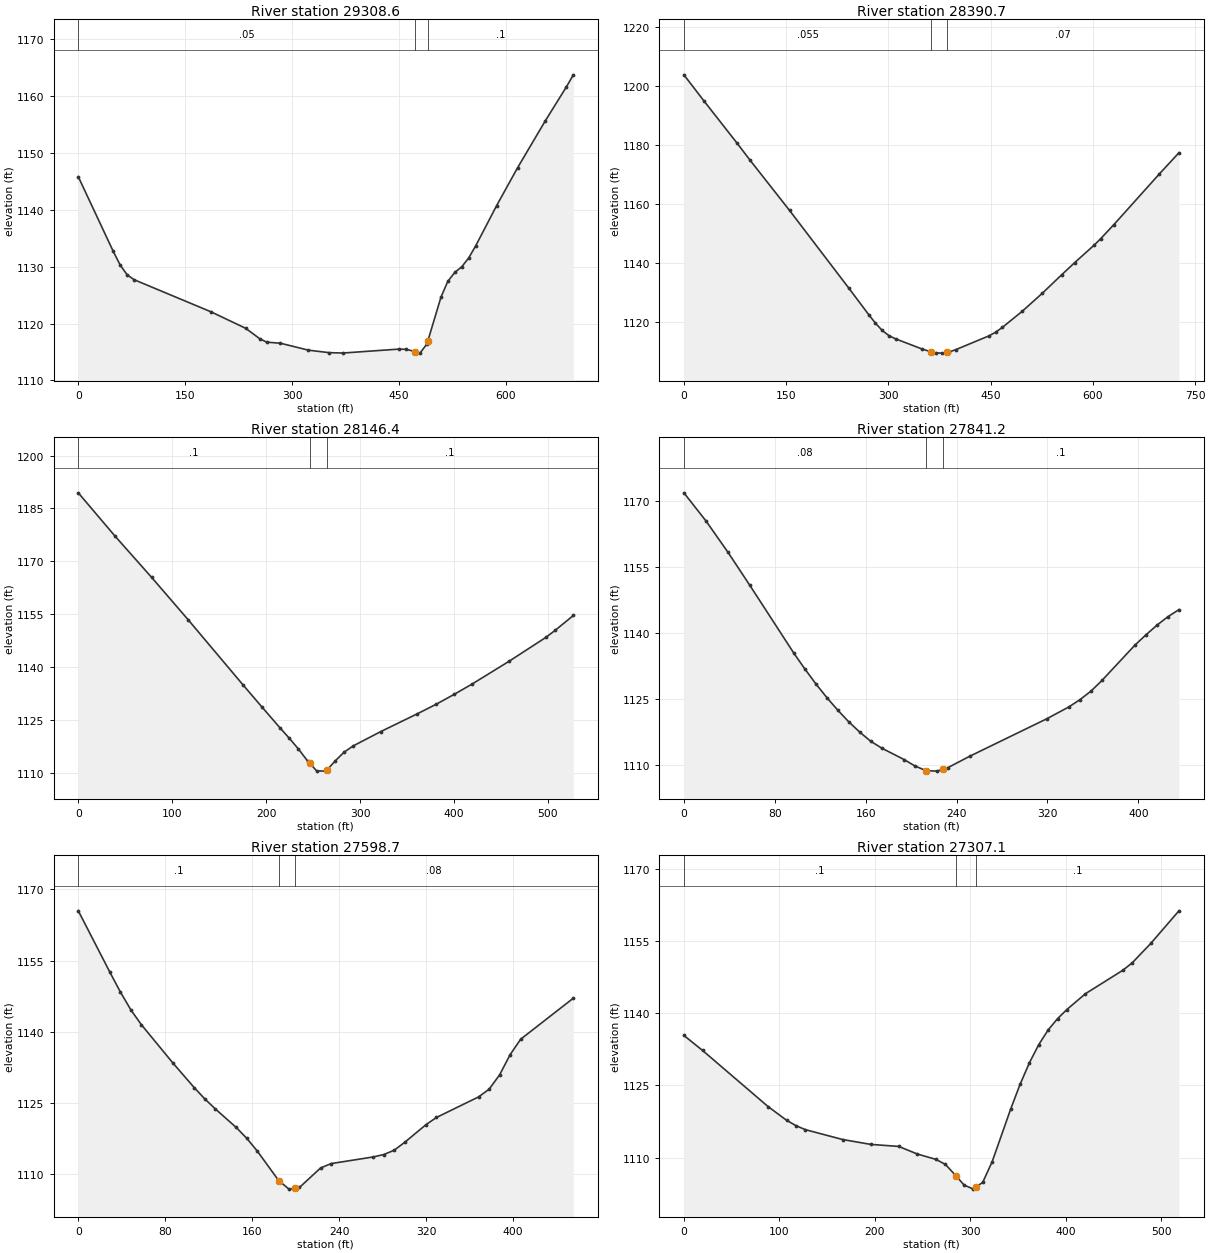
Type RM Length L Ch R = 1 ,29308.6 ,907.6,917.9,921
XS GIS Cut Line= 2
     1782937.568      308817.209     1783619.138      308951.383
#Sta/Elev= 30
       0 1145.81    48.9 1132.73    58.7  1130.3    68.5 1128.58    78.3 1127.71
   185.9 1122.08   234.8 1119.17   254.4 1117.35   264.2 1116.73   283.7 1116.54
   322.9 1115.32   352.2 1114.88   371.8 1114.82   450.1 1115.51   459.8 1115.47
  472.66 1115.08   479.4  1114.8   489.2 1116.42   490.6    1117   508.8 1124.61
   518.5 1127.43   528.3 1128.99   538.1 1129.99   547.9 1131.55   557.7 1133.69
     587 1140.74   616.4  1147.4   655.5 1155.69   684.9 1161.62   694.6 1163.73
#Mann= 3 , 0 , 0
       0     .05       0  472.66    .045       0   490.6      .1       0
Bank Sta=472.66,490.6
XS Rating Curve= 0 ,0
Exp/Cntr=0.3,0.1

Type RM Length L Ch R = 1 ,28390.7 ,258.6,244.2,235.3
XS GIS Cut Line= 4
     1782818.089      309145.235     1783067.655       309223.36
      1783308.54      309305.825     1783510.363      309364.419
#Sta/Elev= 30
       0  1203.8    29.1 1195.06    77.5  1180.8    96.8 1174.96     155 1157.86
   242.1 1131.49   271.3 1122.51   281.1 1119.66   290.9 1117.21   300.7 1115.44
   310.5 1114.36   349.6 1110.89  363.23 1109.91   369.2  1109.6     379 1109.51
  385.42 1109.74   388.8 1109.86   398.6 1110.66   447.6 1115.36   457.4  1116.6
   467.2 1118.22   496.5 1123.71   525.7 1129.76   554.3 1136.07   573.4 1140.18
   602.1 1146.14   611.6 1148.31   630.8 1153.04   697.6 1170.23   726.3  1177.4
#Mann= 3 , 0 , 0
       0    .055       0  363.23    .045       0  385.42     .07       0
Bank Sta=363.23,385.42
XS Rating Curve= 0 ,0
Exp/Cntr=0.3,0.1

Type RM Length L Ch R = 1 ,28146.4 ,293.1,305.3,317.4
XS GIS Cut Line= 2
     1782853.246      309506.186     1783379.756      309479.491
#Sta/Elev= 26
       0 1189.44      39  1177.2    78.1 1165.46   117.2 1153.38   175.7 1134.88
   195.2 1128.82   214.8 1122.79   224.5  1119.9   234.3 1116.84   244.1 1113.42
   246.3 1112.78   253.8  1110.6   263.6 1110.51  264.37 1110.69   273.4 1113.35
   283.1  1115.9   292.9 1117.68   322.2 1121.74   361.2 1126.79   380.8 1129.43
   400.3 1132.28   419.8 1135.28   458.8 1141.67   497.9 1148.43   507.7 1150.41
   527.2 1154.65
#Mann= 3 , 0 , 0
       0      .1       0   246.3    .045       0  264.37      .1       0
Bank Sta=246.3,264.37
XS Rating Curve= 0 ,0
Exp/Cntr=0.3,0.1

Type RM Length L Ch R = 1 ,27841.2 ,253.7,242.5,231.3
XS GIS Cut Line= 2
     1782844.627      309672.301     1783230.704      309874.327
#Sta/Elev= 30
       0 1171.83    19.4 1165.46    38.7 1158.37    58.1  1150.8    96.8 1135.41
   106.5 1131.83   116.2 1128.44   125.9 1125.31   135.6 1122.44   145.2 1119.81
   154.9 1117.47   164.6 1115.39   174.3 1113.84   193.7 1111.28   203.4  1109.8
   213.2 1108.75   222.7 1108.64   228.2 1109.09   232.4 1109.44   251.8 1112.05
   319.5 1120.54   338.9 1123.23   348.6 1124.87   358.3 1126.81     368 1129.24
     397 1137.26   406.7 1139.59   416.4 1141.79   426.1 1143.72   435.7 1145.31
#Mann= 3 , 0 , 0
       0     .08       0   213.2    .045       0   228.2      .1       0
Bank Sta=213.2,228.2
XS Rating Curve= 0 ,0
Exp/Cntr=0.3,0.1

Type RM Length L Ch R = 1 ,27598.7 ,293.7,291.6,289.5
XS GIS Cut Line= 2
     1782765.281       309994.48     1783220.543      309988.204
#Sta/Elev= 30
       0 1165.48    29.1 1152.53    38.8 1148.34    48.4 1144.59    58.1 1141.46
    87.2 1133.36   106.6 1128.23   116.2 1125.88   125.9 1123.76   145.3 1119.82
     155 1117.53   164.7 1114.83   184.3 1108.64   193.8 1106.83   199.3 1107.03
   203.4 1107.18   222.8 1111.28   232.5 1112.21   271.2 1113.61   280.9 1114.11
   290.6 1115.04   300.3 1116.71   319.7  1120.4   329.4 1121.93   368.1 1126.26
   377.8 1127.88   387.5 1130.91   397.2 1135.18   406.9 1138.43   455.3 1147.07
#Mann= 3 , 0 , 0
       0      .1       0   184.3    .045       0   199.3     .08       0
Bank Sta=184.3,199.3
XS Rating Curve= 0 ,0
Exp/Cntr=0.3,0.1

Type RM Length L Ch R = 1 ,27307.1 ,357.7,369.3,380
XS GIS Cut Line= 2
     1782809.621       310267.86     1783325.175      310211.895
#Sta/Elev= 30
       0 1135.37    19.6 1132.25    88.1 1120.63   107.6 1117.77   117.4 1116.66
   127.2 1115.83   166.3 1113.78   195.7 1112.77     225 1112.35   244.6 1110.77
   264.2 1109.65     274 1108.61   284.9 1106.28   293.5 1104.34   303.3 1103.49
  305.71 1103.85   313.1 1104.92   322.9 1109.16   342.5 1120.19   352.2 1125.24
     362 1129.72   371.8 1133.48   381.6 1136.51   391.4 1138.84   401.2 1140.75
   420.7 1144.03   459.9  1148.9   469.7 1150.44   489.2 1154.48   518.6 1161.22
#Mann= 3 , 0 , 0
       0      .1       0   284.9    .045       0  305.71      .1       0
Bank Sta=284.9,305.71
XS Rating Curve= 0 ,0
Exp/Cntr=0.3,0.1

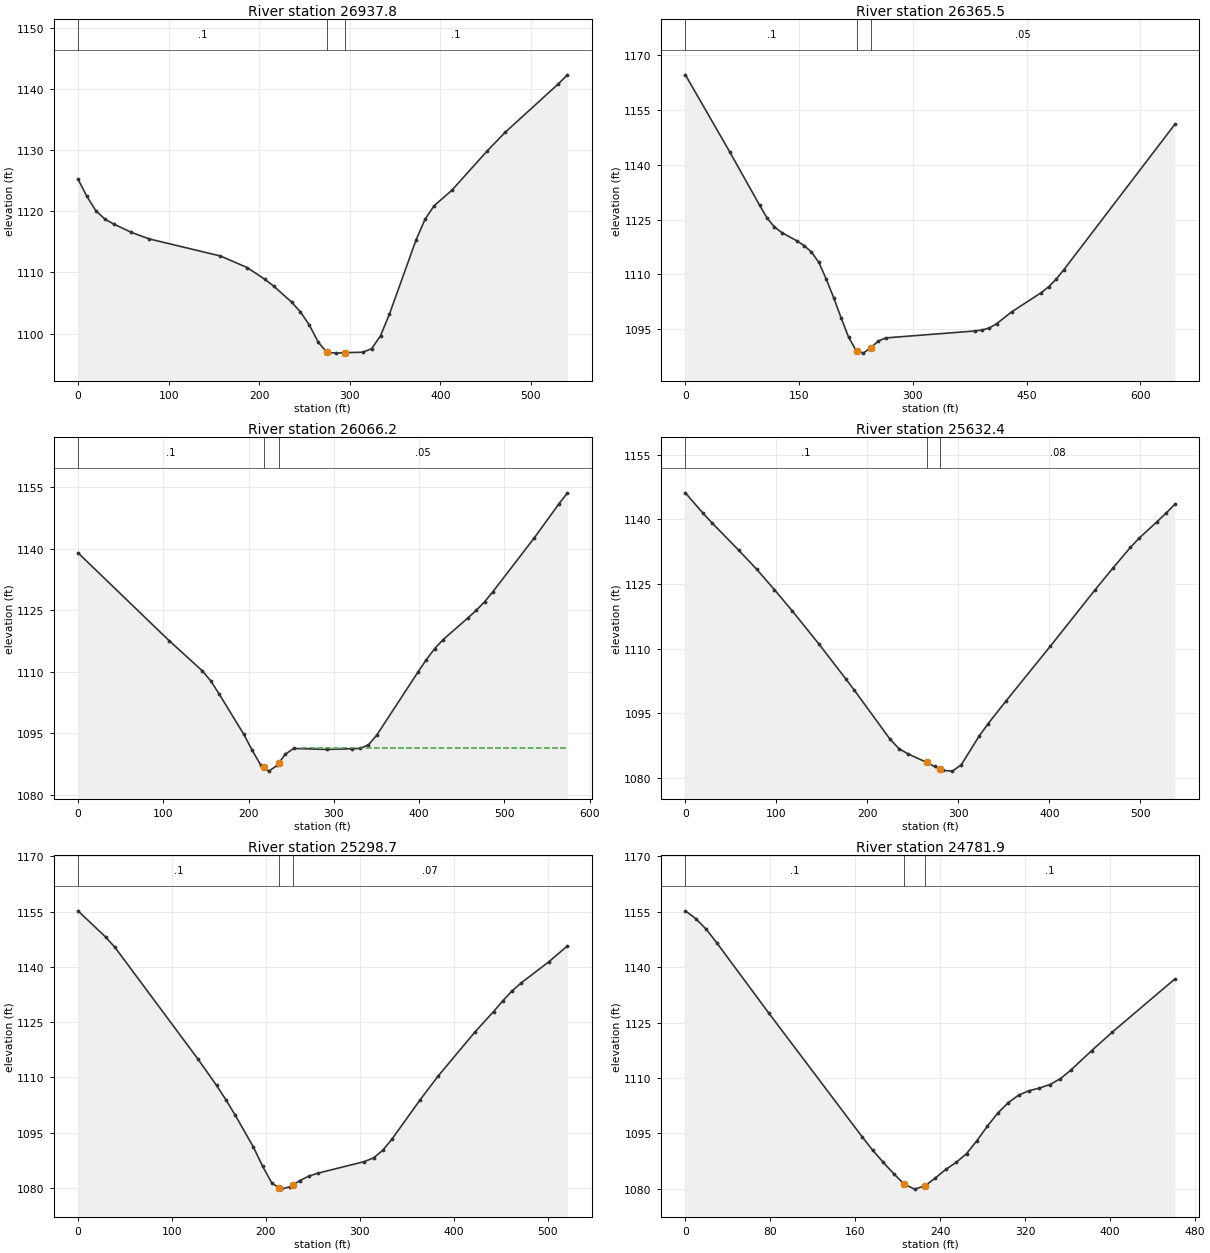
Type RM Length L Ch R = 1 ,26937.8 ,566.8,572.3,577.4
XS GIS Cut Line= 2
     1782729.037       310476.21     1783230.173      310678.315
#Sta/Elev= 30
       0 1125.28     9.8 1122.46    19.6 1120.13    29.5 1118.76    39.3 1117.94
      59 1116.56    78.6 1115.49   157.2  1112.7   186.7 1110.81   206.3 1108.88
   216.1 1107.76   235.8 1105.15   245.6 1103.53   255.4  1101.4   265.3 1098.57
   274.8 1096.93   284.9 1096.79   294.7 1096.86   314.4 1096.94   324.2 1097.51
     334 1099.63   343.9  1103.2   373.3 1115.35   383.2 1118.72     393  1120.9
   412.6 1123.43   451.9 1129.92   471.6 1132.94   530.5  1140.9   540.4 1142.36
#Mann= 3 , 0 , 0
       0      .1       0   274.8    .045       0   294.7      .1       0
Bank Sta=274.8,294.7
XS Rating Curve= 0 ,0
Exp/Cntr=0.3,0.1

Type RM Length L Ch R = 1 ,26365.5 ,307.7,299.3,291
XS GIS Cut Line= 2
     1782401.051      310806.566     1782925.187      311183.469
#Sta/Elev= 30
       0 1164.67    58.7 1143.48    97.8 1128.97   107.6 1125.48   117.4 1122.96
   127.2 1121.42   146.7  1119.2   156.5 1117.87   166.3 1116.11   176.1 1113.22
   185.8 1108.68   195.6 1103.59   205.4 1098.06   215.2 1092.79     225 1089.16
     227    1089   234.8 1088.37   244.5 1089.88   254.3 1091.64   264.1 1092.54
   381.5 1094.44   391.3  1094.7     401 1095.27   410.8 1096.48   430.4 1099.68
   469.5 1104.96   479.3 1106.59   489.1 1108.65   498.9 1111.15   645.6 1151.09
#Mann= 3 , 0 , 0
       0      .1       0     227    .045       0   244.5     .05       0
Bank Sta=227,244.5
XS Rating Curve= 0 ,0
Exp/Cntr=0.3,0.1

Type RM Length L Ch R = 1 ,26066.2 ,426.8,433.8,440.8
XS GIS Cut Line= 2
     1782270.008      311160.229     1782826.501      311301.257
#Sta/Elev= 30
       0 1138.99     107 1117.58     146 1110.22   155.7 1107.81   165.4 1104.67
   194.6 1094.75   204.3  1090.9   214.1 1087.39  217.86 1086.77   223.8 1085.83
   233.5 1087.22   235.9  1087.9   243.3 1089.98     253 1091.35   291.9 1091.11
   321.1 1091.27   330.8 1091.37   340.6 1092.22   350.3 1094.56   398.9    1110
   408.7    1113   418.4 1115.68   428.1 1117.83   457.3 1123.13     467 1124.97
   476.8 1127.04   486.5 1129.48   535.2 1142.64   564.4    1151   574.1  1153.6
#Mann= 3 , 0 , 0
       0      .1       0  217.86    .045       0   235.9     .05       0
#XS Ineff= 2 , 0
                          262.88         1091.36
Permanent Ineff=
       F       F
Bank Sta=217.86,235.9
XS Rating Curve= 0 ,0
Exp/Cntr=0.3,0.1

Type RM Length L Ch R = 1 ,25632.4 ,338.8,333.7,328.4
XS GIS Cut Line= 2
     1782156.304      311467.094     1782611.484      311753.973
#Sta/Elev= 30
       0 1146.14    19.6 1141.36    29.4 1139.15    58.7 1132.82    78.3 1128.44
    97.8  1123.7   117.4 1118.79   146.7  1111.1   176.1 1103.07   185.9 1100.33
     225    1089   234.8 1086.82   244.6 1085.62   265.1 1083.65   273.9 1082.69
   280.1 1082.11   283.7 1081.78   293.5 1081.61   303.3 1083.09   322.8  1089.7
   332.6 1092.57   352.2 1097.81   401.1 1110.56     450 1123.56   469.6  1128.6
   489.1 1133.47   498.9 1135.66   518.5 1139.45   528.3 1141.42     538 1143.47
#Mann= 3 , 0 , 0
       0      .1       0   265.1    .045       0   280.1     .08       0
Bank Sta=265.1,280.1
XS Rating Curve= 0 ,0
Exp/Cntr=0.3,0.1

Type RM Length L Ch R = 1 ,25298.7 ,532.7,516.8,501
XS GIS Cut Line= 2
     1782021.787      311830.133     1782514.497      311999.534
#Sta/Elev= 30
       0 1155.23    29.5 1148.09    39.3 1145.32   127.8 1114.94   147.5 1107.81
   157.3 1103.97   167.1 1099.86   186.8 1091.04   196.6 1085.82   206.4 1081.29
   213.7 1080.09   216.3 1079.66   226.1 1080.34   228.7 1080.77   235.9 1081.95
   245.8 1083.21   255.6    1084   304.8 1087.14   314.6 1088.15   324.4  1090.2
   334.2 1093.25   363.7 1103.75   383.4 1110.39   422.7 1122.38   442.4 1127.89
   452.2 1130.82     462 1133.48   471.9 1135.69   501.4 1141.44     521 1145.71
#Mann= 3 , 0 , 0
       0      .1       0   213.7    .045       0   228.7     .07       0
Bank Sta=213.7,228.7
XS Rating Curve= 0 ,0
Exp/Cntr=0.3,0.1

Type RM Length L Ch R = 1 ,24781.9 ,397.4,411.7,425.9
XS GIS Cut Line= 2
     1782067.663       312462.01     1782497.443      312295.477
#Sta/Elev= 29
       0 1155.26     9.8 1153.15    19.6 1150.28    29.4 1146.66    78.4 1127.61
   166.7 1093.95   176.5 1090.36   186.3 1087.14   196.1 1084.07   205.9 1081.24
   215.8 1079.86   225.6 1080.73   235.4 1082.88   245.2  1085.2     255  1087.1
   264.8 1089.49   274.6    1093   284.4 1096.93   294.2 1100.47     304 1103.28
   313.8 1105.33   323.6 1106.52   333.4 1107.24   343.2  1108.2     353 1109.75
   362.8 1112.06   382.5 1117.36   402.1 1122.42   460.9 1136.79
#Mann= 3 , 0 , 0
       0      .1       0   205.9    .045       0   225.6      .1       0
Bank Sta=205.9,225.6
XS Rating Curve= 0 ,0
Exp/Cntr=0.3,0.1

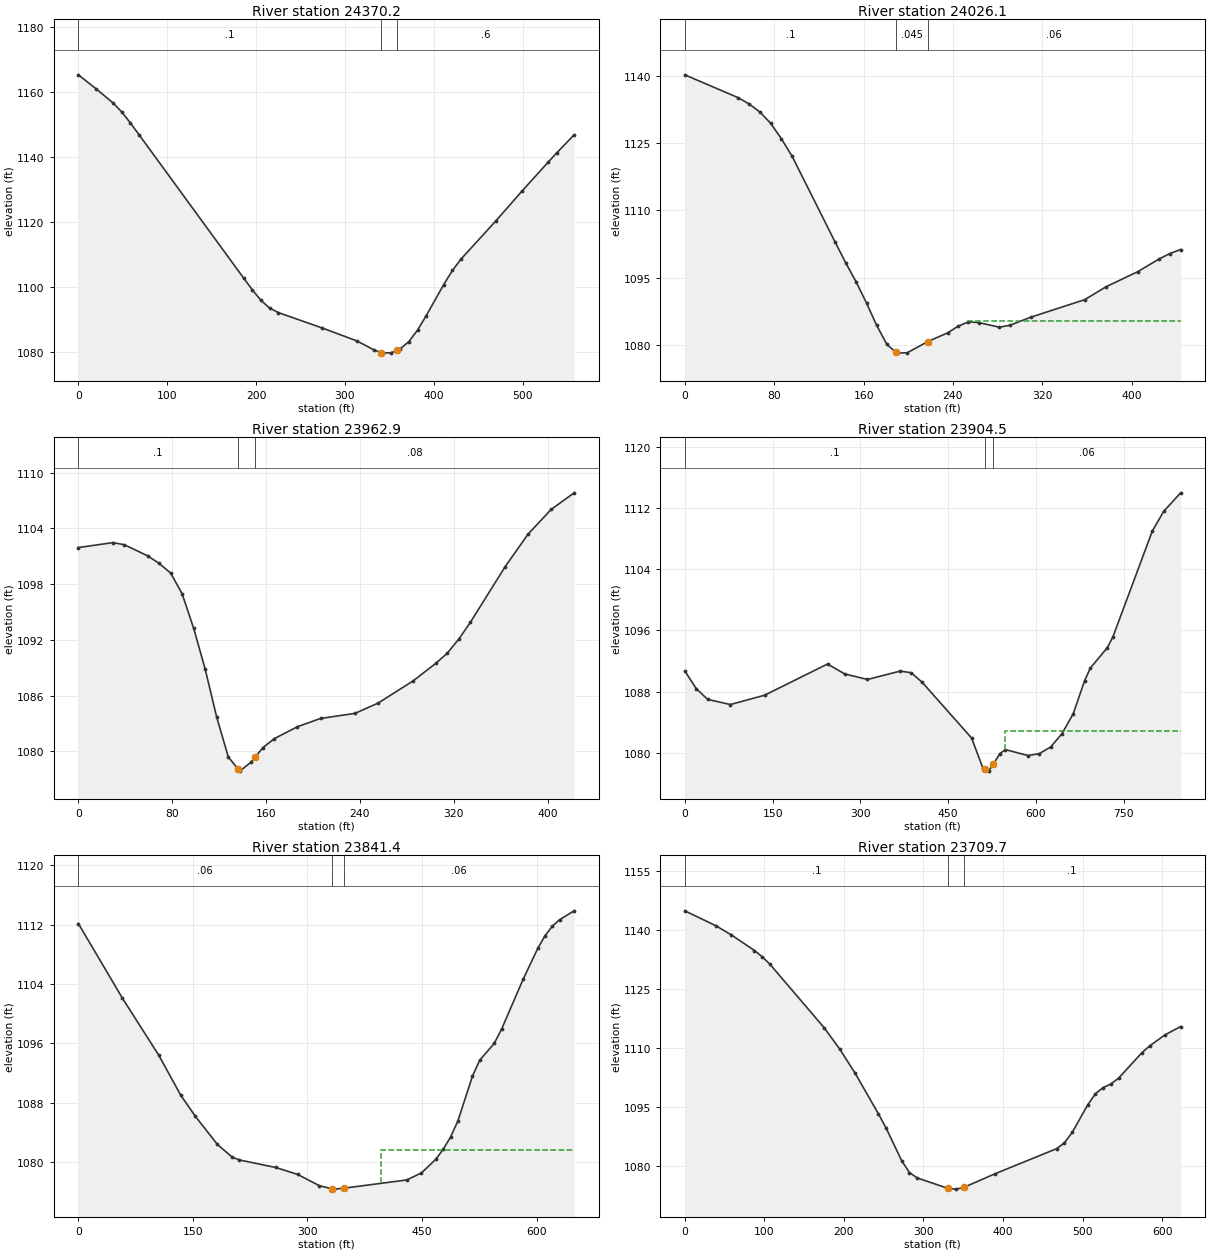
Type RM Length L Ch R = 1 ,24370.2 ,335.9,344.1,352.2
XS GIS Cut Line= 2
     1782039.903      312680.211     1782579.218      312823.486
#Sta/Elev= 30
       0 1165.35    19.6 1161.13    39.2 1156.67      49 1153.89    58.7  1150.5
    68.5 1146.85     186 1102.81   195.8  1099.2   205.6 1095.92   215.4 1093.53
   225.2 1092.17   274.1 1087.47   313.3 1083.48   332.8 1080.69  340.91 1079.84
   342.6  1079.7   352.4 1079.84   358.4 1080.56   362.2 1081.02     372 1083.25
   381.8  1086.8   391.6 1091.26   411.2  1100.8     421 1105.14   430.8 1108.69
   469.9  1120.4   499.3 1129.57   528.6 1138.43   538.4 1141.33     558  1146.9
#Mann= 3 , 0 , 0
       0      .1       0  340.91    .045       0   358.4      .6       0
Bank Sta=340.91,358.4
XS Rating Curve= 0 ,0
Exp/Cntr=0.3,0.1

Type RM Length L Ch R = 1 ,24026.1 ,68.3,63.2,57.7
XS GIS Cut Line= 4
     1781982.614      312870.061     1782093.726      312975.964
     1782190.948      313043.672     1782347.198      313114.853
#Sta/Elev= 30
       0 1140.16      48 1135.05    57.6 1133.66    67.2 1131.89    76.8 1129.38
    86.3 1125.98    95.9  1122.1   134.3 1103.05   143.9 1098.37   153.5 1093.98
   162.6 1089.37   171.7 1084.41   180.8 1080.18  188.85 1078.41     190 1078.22
   199.1 1078.31   217.3 1080.77   235.5 1082.77   244.6 1084.21   253.8 1085.16
   262.9 1085.03   281.5 1083.99     291 1084.43   310.1 1086.26   357.8 1090.11
   376.9 1092.98   405.5 1096.37   424.6  1099.2   434.1 1100.39   443.7 1101.28
#Mann= 3 , 0 , 0
       0      .1       0  188.85    .045       0   217.3     .06       0
#XS Ineff= 2 , 0
                          253.45         1085.31
Permanent Ineff=
       F       F
Bank Sta=188.85,217.3
XS Rating Curve= 0 ,0
Exp/Cntr=0.3,0.1

Type RM Length L Ch R = 1 ,23962.9 ,57.8,58.4,59.3
XS GIS Cut Line= 2
     1781964.468      313002.884     1782357.243      313158.671
#Sta/Elev= 30
       0 1101.94    29.5 1102.47    39.3 1102.24      59 1101.05    68.8 1100.24
    78.6  1099.2    88.4 1096.98    98.3 1093.24   108.1 1088.84   117.9 1083.68
   127.8 1079.39   135.9 1078.13   137.6 1077.87   147.4 1078.86   150.9 1079.41
   157.2 1080.39     167 1081.37   186.7 1082.65   206.4 1083.54   235.8 1084.09
   255.5  1085.2     285 1087.56   304.6 1089.47   314.4 1090.57   324.3  1092.1
   334.1  1093.9   363.6 1099.86   383.2 1103.38   402.9 1106.04   422.5 1107.83
#Mann= 3 , 0 , 0
       0      .1       0   135.9    .045       0   150.9     .08       0
Bank Sta=135.9,150.9
XS Rating Curve= 0 ,0
Exp/Cntr=0.3,0.1

Type RM Length L Ch R = 1 ,23904.5 ,67,63.1,59.2
XS GIS Cut Line= 4
     1781658.146      312790.633     1781883.285      313006.761
     1782029.986      313089.227     1782366.792      313234.192
#Sta/Elev= 30
       0  1090.7    19.5  1088.4      39 1086.98      78 1086.31   136.5 1087.53
   243.8  1091.6   273.1 1090.31   312.1 1089.58   368.2 1090.68   386.9 1090.46
   405.6 1089.21     490 1081.93   509.3 1078.01   512.2 1077.89     519 1077.61
   527.2 1078.52   538.3  1079.9   547.9 1080.42   586.5 1079.64   605.8  1079.9
   625.1 1080.77   644.4  1082.5   663.7 1085.12     683  1089.4   692.7 1091.06
   721.6 1093.71   731.3 1095.12   798.8 1108.98   818.1 1111.53   847.1 1113.96
#Mann= 3 , 0 , 0
       0      .1       0   512.2    .045       0   527.2     .06       0
#XS Ineff= 2 , 0
                          547.15          1082.8
Permanent Ineff=
       F       F
Bank Sta=512.2,527.2
XS Rating Curve= 0 ,0
Exp/Cntr=0.3,0.1

Type RM Length L Ch R = 1 ,23841.4 ,135.8,131.7,127.8
XS GIS Cut Line= 4
     1781720.462      313083.603     1781906.226      313130.478
     1782203.101      313201.658     1782345.462      313255.478
#Sta/Elev= 30
       0 1112.16    57.5 1102.12   105.4 1094.37   134.1 1088.99   153.3 1086.13
     182 1082.36   201.1 1080.66   210.7 1080.26   258.4 1079.24     287 1078.31
   315.6 1076.78   332.3 1076.35   334.7 1076.32   347.3 1076.44   430.1 1077.56
   449.2 1078.51   468.3 1080.38   477.8 1081.72   487.3 1083.34   496.9 1085.52
   515.9 1091.54   525.4 1093.71   544.4 1095.97     554 1097.89   582.5 1104.68
   601.5 1108.81     611 1110.52   620.5 1111.79     630 1112.67   649.1 1113.87
#Mann= 3 , 0 , 0
       0     .06       0   332.3    .045       0   347.3     .06       0
#XS Ineff= 2 , 0
                          396.07         1081.62
Permanent Ineff=
       F       F
Bank Sta=332.3,347.3
XS Rating Curve= 0 ,0
Exp/Cntr=0.3,0.1

Type RM Length L Ch R = 1 ,23709.7 ,412.8,415.9,418.6
XS GIS Cut Line= 2
     1781699.839      313271.629     1782321.742      313311.425
#Sta/Elev= 30
       0 1144.86      39 1141.08    58.4 1138.75    87.6 1134.77    97.4 1133.16
   107.1 1131.26   175.3  1115.1   194.7 1109.72   214.2 1103.53   243.4 1093.23
   253.2 1089.56   272.6 1081.33   282.4  1078.3   292.1 1076.95   331.1 1074.27
   340.8  1074.1   350.5 1074.52   389.5 1077.97   467.4 1084.39   477.1 1085.86
   486.9  1088.5   506.3 1095.48   516.1 1098.36   525.8 1099.91   535.5 1100.82
   545.3 1102.33   574.5 1108.78   584.2 1110.51   603.7 1113.34   623.2 1115.44
#Mann= 3 , 0 , 0
       0      .1       0   331.1    .045       0   350.5      .1       0
Bank Sta=331.1,350.5
XS Rating Curve= 0 ,0
Exp/Cntr=0.3,0.1