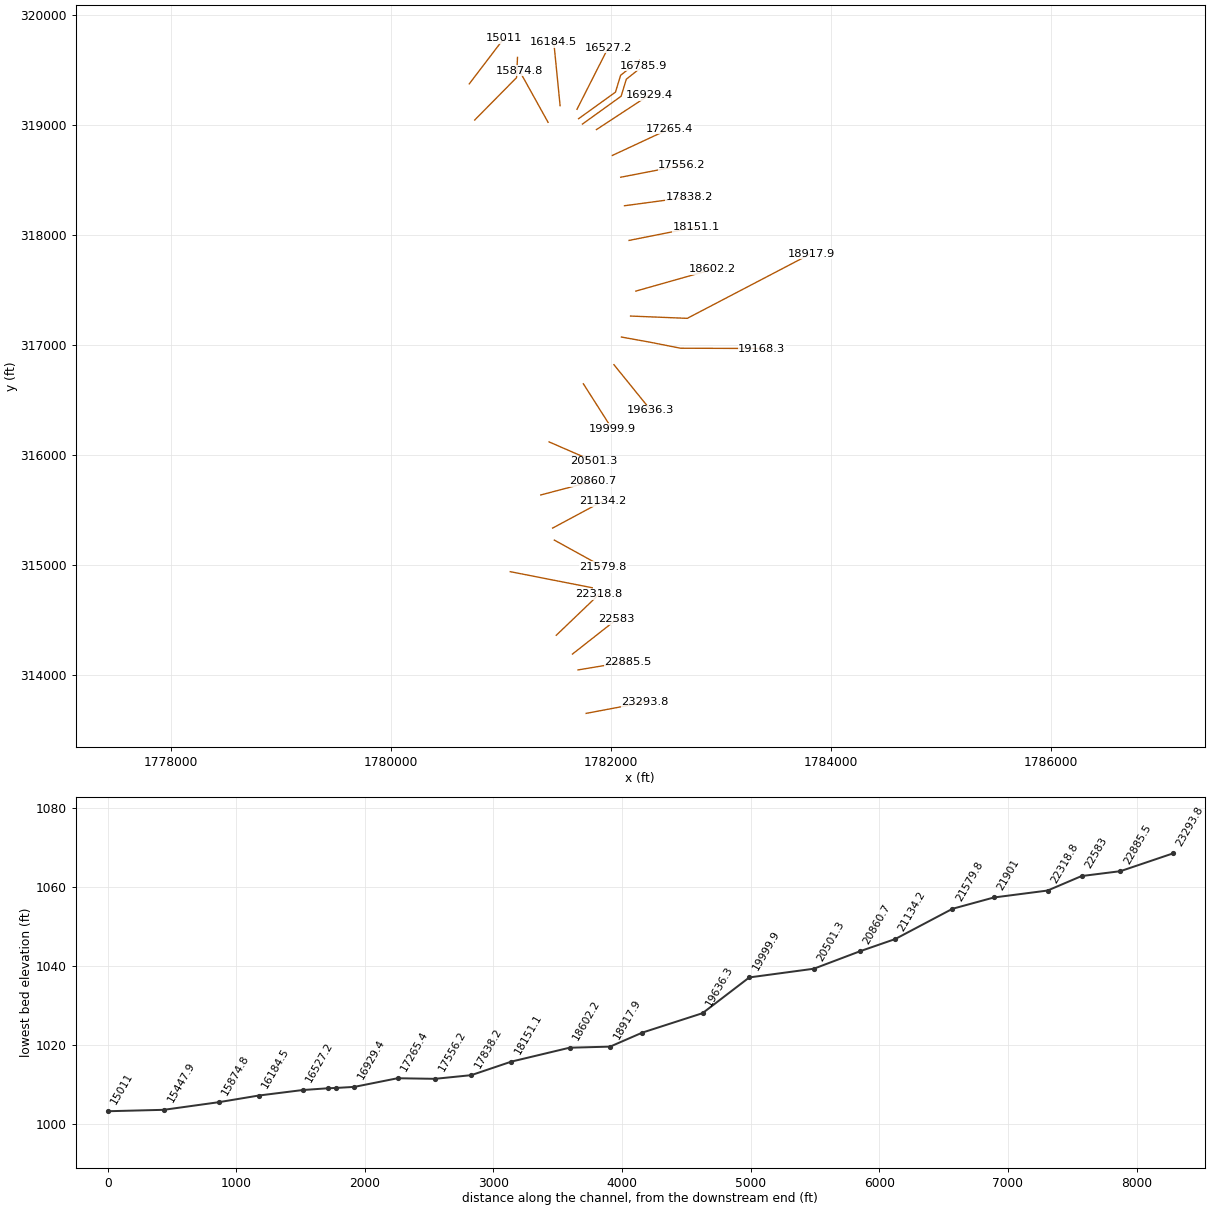
HEC-RAS study HusteadFrk.prj: HusteadFrk

--- HusteadFrk.g01 (geometry) --- (continued)

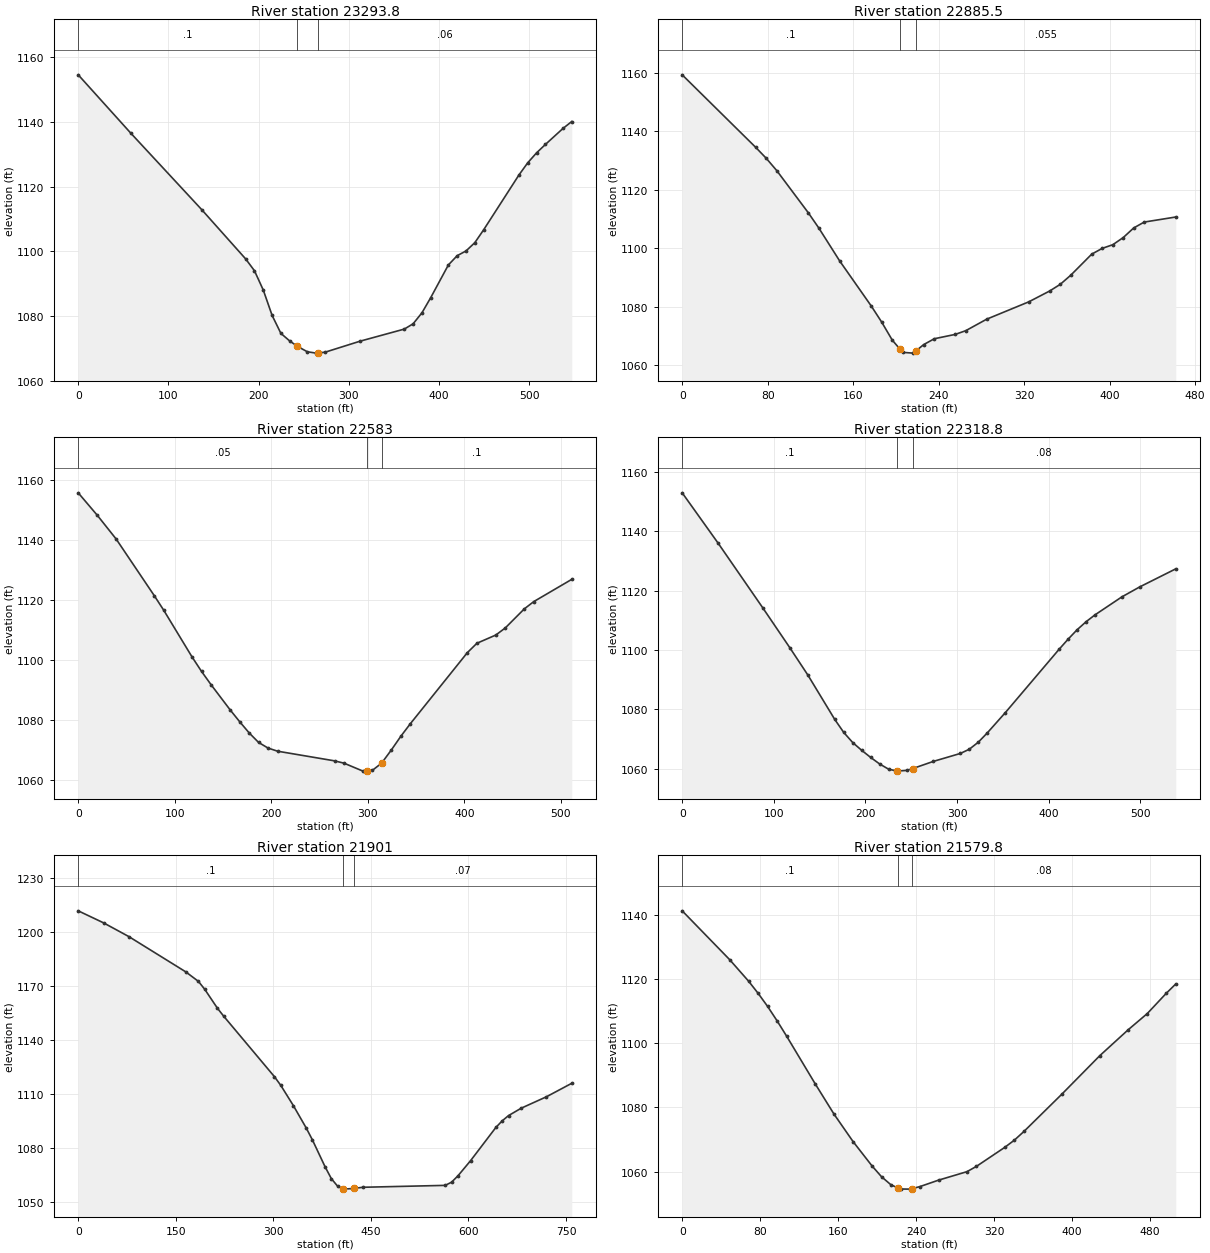
Type RM Length L Ch R = 1 ,23293.8 ,408.8,408.3,407.8
XS GIS Cut Line= 2
     1781771.565      313653.437       1782309.3       313754.66
#Sta/Elev= 30
       0 1154.59    58.6 1136.46   136.8 1112.95   185.6 1097.69   195.4 1094.02
   205.2 1088.03     215 1080.19   224.7 1074.66   234.5  1072.3   243.1 1070.64
     254 1068.97   263.8 1068.55  265.48  1068.6   273.6 1068.83   312.7 1072.26
   361.5 1075.98   371.3 1077.62   381.1 1081.02   390.8  1085.7   410.4 1095.82
   420.2 1098.69   429.9 1100.13   439.7  1102.7   449.5 1106.68   488.6 1123.62
   498.3 1127.37   508.1 1130.45   517.9 1133.05   537.4    1138   547.2 1140.16
#Mann= 3 , 0 , 0
       0      .1       0   243.1    .045       0  265.48     .06       0
Bank Sta=243.1,265.48
XS Rating Curve= 0 ,0
Exp/Cntr=0.3,0.1

Type RM Length L Ch R = 1 ,22885.5 ,291,302.5,313.9
XS GIS Cut Line= 2
     1781697.796      314048.143     1782153.435      314124.159
#Sta/Elev= 30
       0 1159.33    68.8  1134.5    78.6 1130.78    88.5 1126.54   117.9 1112.16
   127.8 1106.91   147.4  1095.6   176.9  1080.2   186.7 1074.67   196.6  1068.5
   203.6 1065.51   206.4 1064.31   216.2 1064.05   218.6 1064.77     226 1066.97
   235.9 1068.97   255.5 1070.46   265.4 1071.74     285 1075.68   324.3  1081.6
     344 1085.34   353.8  1087.6   363.6 1090.71   383.3 1097.95   393.1 1099.92
     403 1101.17   412.8 1103.63   422.6 1106.92   432.4 1108.92   461.9 1110.65
#Mann= 3 , 0 , 0
       0      .1       0   203.6    .045       0   218.6    .055       0
Bank Sta=203.6,218.6
XS Rating Curve= 0 ,0
Exp/Cntr=0.3,0.1

Type RM Length L Ch R = 1 ,22583   ,261.9,264.2,265.8
XS GIS Cut Line= 2
      1781647.56      314192.387     1782049.567      314508.276
#Sta/Elev= 30
       0 1155.65    19.7 1148.18    39.3 1140.24    78.7 1121.39    88.5 1116.53
     118 1100.86   127.8 1096.05   137.6 1091.65   157.3 1083.28   167.2 1079.32
     177 1075.59   186.8  1072.4   196.6 1070.51   206.5 1069.46   265.5 1066.24
   275.3 1065.47     295 1062.81   299.3 1062.93   304.8 1063.09   314.3 1065.47
   324.5 1069.92   334.3 1074.48   344.1 1078.64   403.1 1102.33     413 1105.46
   432.6 1108.21   442.4 1110.57   462.1 1116.93   471.9 1119.36   511.3 1126.79
#Mann= 3 , 0 , 0
       0     .05       0   299.3    .045       0   314.3      .1       0
Bank Sta=299.3,314.3
XS Rating Curve= 0 ,0
Exp/Cntr=0.3,0.1

Type RM Length L Ch R = 1 ,22318.8 ,439.5,417.8,396.7
XS GIS Cut Line= 2
     1781500.567       314363.49     1781889.807      314735.885
#Sta/Elev= 30
       0    1153    39.2 1136.03    88.2  1114.1   117.5 1100.75   137.1 1091.57
   166.5 1076.58   176.3  1072.2   186.1 1068.78   195.9 1066.16   205.7 1063.76
   215.5 1061.56   225.3 1059.79  234.04 1059.21   235.1 1059.14   244.9 1059.38
   251.5 1059.99   274.2 1062.43   303.6  1065.1   313.4 1066.53   323.2  1068.9
     333 1072.03   352.6 1078.84   411.4 1100.24   421.2 1103.64     431 1106.81
   440.8 1109.52   450.5 1111.83   479.9 1117.91   499.5 1121.29   538.7 1127.36
#Mann= 3 , 0 , 0
       0      .1       0  234.04    .045       0   251.5     .08       0
Bank Sta=234.04,251.5
XS Rating Curve= 0 ,0
Exp/Cntr=0.3,0.1

Type RM Length L Ch R = 1 ,21901   ,328,321.3,313.3
XS GIS Cut Line= 2
     1781081.907      314941.087     1781826.699      314795.254
#Sta/Elev= 30
       0  1211.6    38.9 1204.95    77.8 1197.34   165.4 1177.77   184.9 1172.48
   194.6 1168.08   214.1 1157.59   223.8 1153.16   301.6 1119.74   311.4 1114.91
   330.8 1103.67   350.3 1091.44     360 1084.74   379.5 1069.82   389.2  1063.2
   398.9 1058.97  407.04 1057.64   408.6 1057.38   423.6 1057.76   437.8 1058.41
   564.3 1059.46   574.1 1061.24   583.8 1064.72   603.3 1073.15   642.2 1091.57
   651.9 1095.21   661.6 1098.12   681.1 1102.22     720 1108.57   758.9 1116.04
#Mann= 3 , 0 , 0
       0      .1       0  407.04    .045       0   423.6     .07       0
Bank Sta=407.04,423.6
XS Rating Curve= 0 ,0
Exp/Cntr=0.3,0.1

Type RM Length L Ch R = 1 ,21579.8 ,422.9,445.6,468.5
XS GIS Cut Line= 2
     1781482.776      315228.017     1781926.352      314983.654
#Sta/Elev= 30
       0 1141.33    48.7  1126.1    68.2 1119.36    77.9  1115.6    87.6 1111.53
    97.4    1107   107.1 1102.26   136.4  1087.4   155.8  1077.9   175.3 1069.36
   194.8 1061.75   204.5 1058.39   214.3 1055.84     221 1054.96     224 1054.56
   233.7 1054.52     236  1054.7   243.5 1055.27     263 1057.32   292.2 1059.97
   301.9 1061.62   331.1 1067.58   340.9 1069.82   350.6  1072.5   389.6 1084.16
   428.5 1096.16   457.7 1104.26   477.2 1109.29   496.7 1115.62   506.4 1118.51
#Mann= 3 , 0 , 0
       0      .1       0     221    .045       0     236     .08       0
Bank Sta=221,236
XS Rating Curve= 0 ,0
Exp/Cntr=0.3,0.1

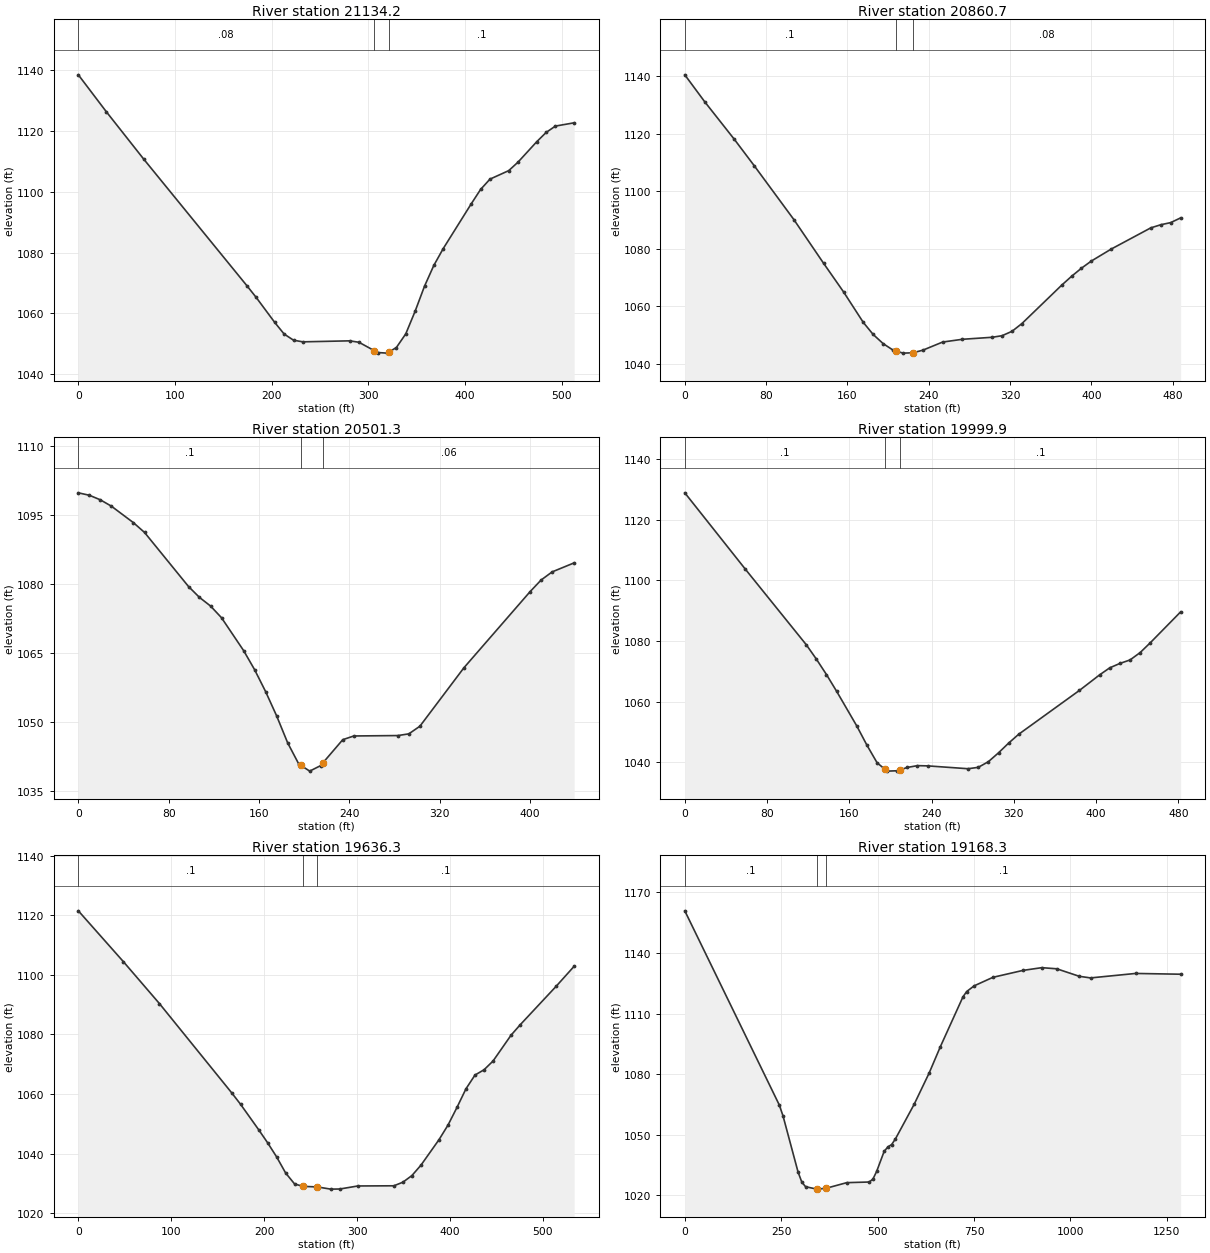
Type RM Length L Ch R = 1 ,21134.2 ,279.5,273.6,267.5
XS GIS Cut Line= 2
     1781466.952      315337.099      1781918.93      315579.533
#Sta/Elev= 30
       0 1138.55      29 1126.37    67.7 1110.75   174.2 1069.13   183.9 1065.24
   203.2 1056.95   212.9 1053.14   222.6 1051.11   232.2 1050.57   280.6  1050.9
   290.3 1050.43   306.1 1047.67   309.7 1047.05   319.4 1046.85   321.1 1047.18
     329  1048.7   338.7 1053.19   348.4 1060.66   358.1  1068.9   367.7 1075.73
   377.4 1081.27   406.4 1096.03   416.1 1100.78   425.8 1104.18   445.2 1106.98
   454.8 1109.77   474.2 1116.51   483.9 1119.56   493.5 1121.66   512.9 1122.74
#Mann= 3 , 0 , 0
       0     .08       0   306.1    .045       0   321.1      .1       0
Bank Sta=306.1,321.1
XS Rating Curve= 0 ,0
Exp/Cntr=0.3,0.1

Type RM Length L Ch R = 1 ,20860.7 ,373.9,359.4,344.8
XS GIS Cut Line= 2
     1781359.385        315638.2     1781830.929      315762.596
#Sta/Elev= 30
       0 1140.48    19.5 1131.16    48.8 1118.03    68.3 1108.89   107.3 1090.16
   136.6 1074.94   156.1 1065.07   175.6 1054.42   185.3 1050.24   195.1 1047.06
   204.8 1044.82   207.3 1044.55   214.6 1043.76   224.3 1043.87   234.1 1044.78
   253.6 1047.61   273.1 1048.57   302.4 1049.27   312.1 1049.82   321.9 1051.35
   331.6 1054.04   370.6 1067.34   380.4 1070.45   390.1 1073.26   399.9 1075.77
   419.4 1079.92   458.4  1087.3   468.2 1088.38   477.9 1089.12   487.7 1090.76
#Mann= 3 , 0 , 0
       0      .1       0   207.3    .045       0   224.3     .08       0
Bank Sta=207.3,224.3
XS Rating Curve= 0 ,0
Exp/Cntr=0.3,0.1

Type RM Length L Ch R = 1 ,20501.3 ,514.8,501.3,487.9
XS GIS Cut Line= 2
     1781434.908      316120.367     1781837.577      315945.234
#Sta/Elev= 30
       0 1099.73     9.8  1099.2    19.5 1098.21    29.3 1096.83    48.8 1093.25
    58.6 1091.14    97.6 1079.39   107.3 1077.03   117.1 1075.16   126.8 1072.62
   146.4 1065.48   156.1 1061.35   165.9 1056.57   175.6 1051.33   185.4 1045.46
   195.2 1040.88   197.21040.561   204.9 1039.33   214.7 1040.54   216.4 1041.07
   234.2 1046.16     244 1046.96     283 1047.05   292.7 1047.42   302.5 1049.08
   341.5 1061.77   400.1 1078.29   409.8  1080.8   419.6 1082.57   439.1 1084.53
#Mann= 3 , 0 , 0
       0      .1       0   197.2    .045       0   216.4     .06       0
Bank Sta=197.2,216.4
XS Rating Curve= 0 ,0
Exp/Cntr=0.3,0.1

Type RM Length L Ch R = 1 ,19999.9 ,361,363.7,366.1
XS GIS Cut Line= 2
     1781746.706      316648.149     1782006.081      316241.667
#Sta/Elev= 30
       0  1128.8      59  1103.6   118.1 1078.78   127.9 1074.06   137.8 1068.93
   147.6 1063.46   167.3 1051.98   177.1 1045.69     187 1039.89   194.6 1037.75
   196.8 1037.13   206.6 1037.25   209.6 1037.58   216.5 1038.35   226.3 1038.94
   236.2 1038.86   275.5 1037.92   285.4 1038.38   295.2 1040.23   305.1 1043.16
   314.9 1046.35   324.7 1049.27   383.8 1063.72   403.5 1068.86   413.3 1071.16
   423.1  1072.6     433 1073.75   442.8 1076.17   452.7 1079.41   482.2 1089.58
#Mann= 3 , 0 , 0
       0      .1       0   194.6    .045       0   209.6      .1       0
Bank Sta=194.6,209.6
XS Rating Curve= 0 ,0
Exp/Cntr=0.3,0.1

Type RM Length L Ch R = 1 ,19636.3 ,452.3,468,483.6
XS GIS Cut Line= 2
     1782024.526      316821.904     1782360.384      316407.263
#Sta/Elev= 30
       0 1121.51    48.5 1104.44    87.3 1090.36   164.9 1060.46   174.6 1056.55
     194 1048.05   203.7 1043.64   213.4 1038.89   223.1 1033.49   232.8 1029.78
   242.2 1028.99   257.2 1028.81   271.6 1028.07   281.4 1028.11   300.8 1029.13
   339.6 1029.19   349.3  1030.4     359 1032.63   368.7  1036.1   388.1 1044.65
   397.8 1049.55   407.5 1055.51   417.2 1061.77   426.9 1066.38   436.6 1068.14
   446.3 1071.08   465.7 1079.76   475.4 1083.21   514.2 1096.16   533.6  1102.9
#Mann= 3 , 0 , 0
       0      .1       0   242.2    .045       0   257.2      .1       0
Bank Sta=242.2,257.2
XS Rating Curve= 0 ,0
Exp/Cntr=0.3,0.1

Type RM Length L Ch R = 1 ,19168.3 ,246.9,250.4,253.9
XS GIS Cut Line= 4
     1782092.857      317073.186     1782353.274      317026.311
     1782629.316      316971.623     1783368.899      316969.019
#Sta/Elev= 30
       0 1160.83     245 1064.78   254.8 1059.28   293.7 1031.59   303.4 1026.62
   313.1 1024.36   342.2 1023.15   366.2 1023.56   419.9 1026.35   478.1 1026.67
   487.8 1028.12   497.5 1031.94   516.9 1041.84   526.6 1044.04   536.3 1045.21
     546 1047.95   594.7 1065.12   633.6  1080.6   662.8 1093.69   721.2 1118.26
   730.9 1120.91   750.4 1123.73     799 1127.94   876.9 1131.36   925.5 1132.71
   964.5 1132.15  1022.8 1128.44    1052 1127.64  1168.8 1129.85  1285.6 1129.47
#Mann= 3 , 0 , 0
       0      .1       0   342.2    .045       0   366.2      .1       0
Bank Sta=342.2,366.2
XS Rating Curve= 0 ,0
Exp/Cntr=0.3,0.1

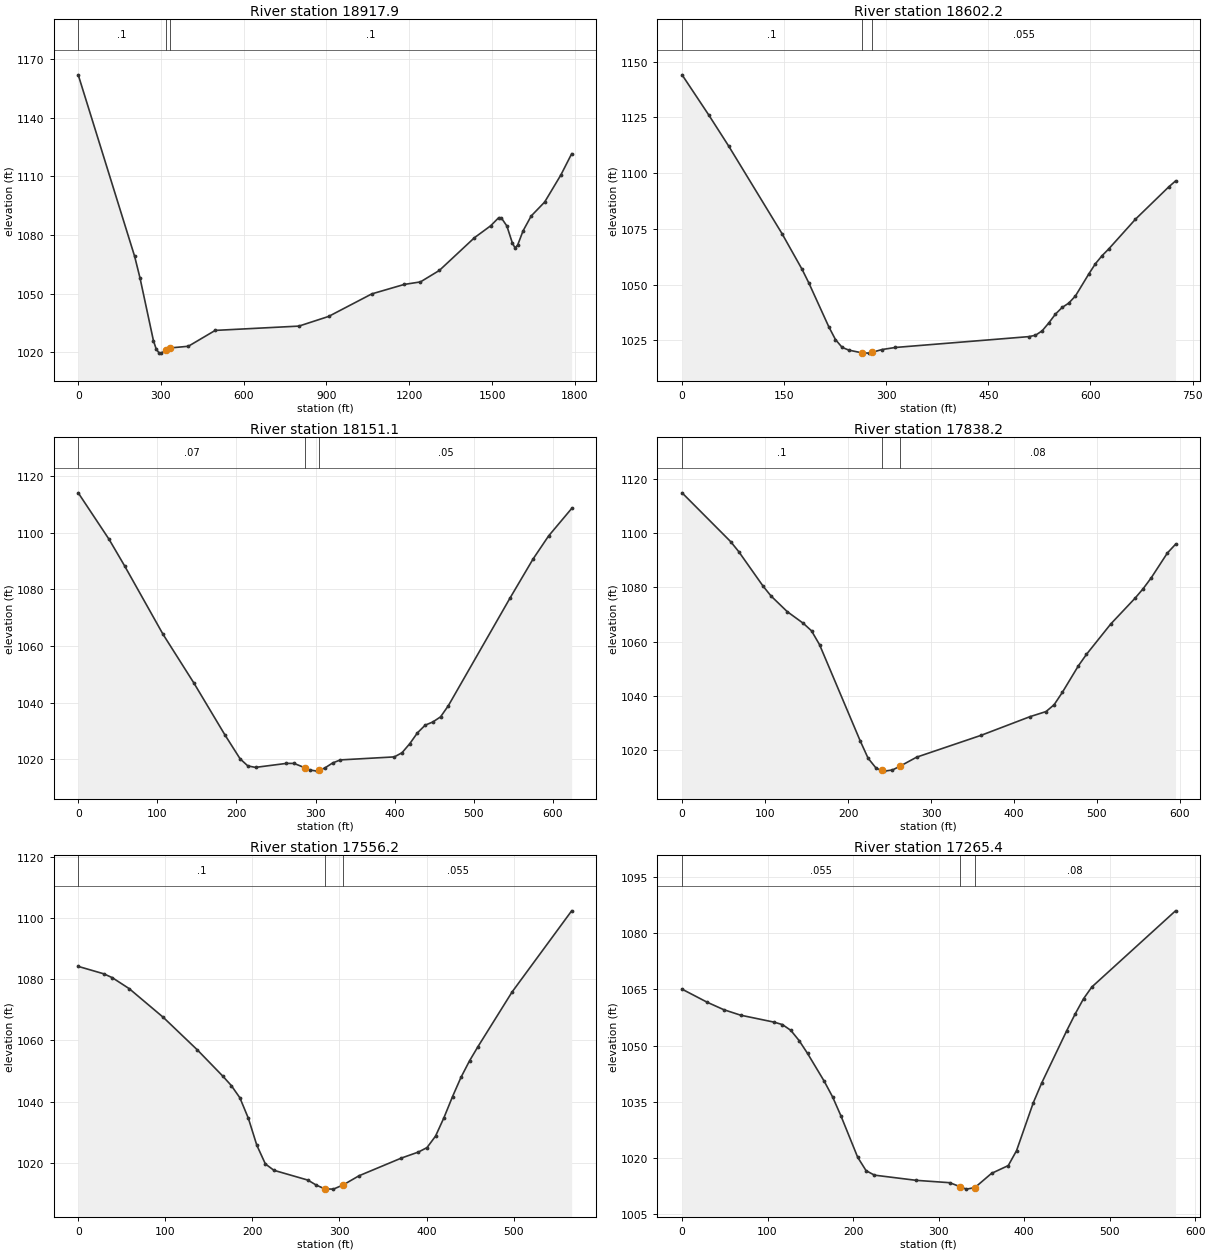
Type RM Length L Ch R = 1 ,18917.9 ,308.5,315.7,322.9
XS GIS Cut Line= 3
     1782175.657      317264.004     1782691.282      317243.171
     1783819.409      317832.307
#Sta/Elev= 30
       0 1161.92   204.5  1069.1   223.9 1058.08   272.6 1026.03   282.4  1021.8
   292.1 1019.87   301.8  1019.6     319  1021.4     334 1022.26   399.2 1023.11
   496.6 1031.22     800 1033.42   907.6 1038.36  1064.3  1049.9  1181.8 1054.73
  1240.5 1056.02    1309 1061.88  1436.3 1078.62    1495 1084.71  1524.4 1088.89
  1534.2 1088.66  1553.8 1084.63  1573.4 1076.07  1583.2 1073.42  1592.9 1074.84
  1612.5 1082.12  1641.9 1089.72  1690.8 1096.86  1749.6 1110.72  1788.7 1121.56
#Mann= 3 , 0 , 0
       0      .1       0     319    .045       0     334      .1       0
Bank Sta=319,334
XS Rating Curve= 0 ,0
Exp/Cntr=0.3,0.1

Type RM Length L Ch R = 1 ,18602.2 ,453,451.1,449.1
XS GIS Cut Line= 2
     1782223.514       317490.66     1782921.013      317687.932
#Sta/Elev= 30
       0  1144.1    39.2  1126.1    68.6  1112.1   146.9 1072.86   176.3 1056.89
   186.1 1050.87   215.5 1031.17   225.3 1025.43   235.1  1021.9   244.9 1020.68
   264.1 1019.45   274.3 1019.32   279.1 1019.68   293.9 1020.94   313.4 1021.86
   509.4 1026.72   519.2 1027.33     529 1029.33   538.8 1032.88   548.5 1036.81
   558.3 1039.78   568.1 1041.75   577.9 1044.96   597.5 1054.81   607.3 1059.44
   617.1 1063.04   626.9 1066.07   666.1 1079.38   715.1  1093.9   724.9  1096.5
#Mann= 3 , 0 , 0
       0      .1       0   264.1    .045       0   279.1    .055       0
Bank Sta=264.1,279.1
XS Rating Curve= 0 ,0
Exp/Cntr=0.3,0.1

Type RM Length L Ch R = 1 ,18151.1 ,314.1,312.9,311.4
XS GIS Cut Line= 2
     1782162.306      317951.346     1782773.965      318072.707
#Sta/Elev= 30
       0    1114      39 1097.59    58.5 1088.29   107.2 1064.08   146.2 1046.89
   185.1 1028.73   204.6 1020.15   214.4 1017.64   224.1 1017.13   263.1 1018.54
   272.8 1018.53  286.74 1016.96   292.3 1016.22     302 1015.81   304.7 1016.12
   311.8 1016.94   321.5 1018.69   331.3 1019.77   399.5 1020.83   409.2  1022.3
     419 1025.49   428.7 1029.32   438.5 1032.03   448.2 1033.16   457.9 1034.96
   467.7 1038.87   545.6 1076.83   574.9 1090.69   594.4 1098.77   623.6 1108.48
#Mann= 3 , 0 , 0
       0     .07       0  286.74    .045       0   304.7     .05       0
Bank Sta=286.74,304.7
XS Rating Curve= 0 ,0
Exp/Cntr=0.3,0.1

Type RM Length L Ch R = 1 ,17838.2 ,280.9,282,283.4
XS GIS Cut Line= 2
     1782120.449      318266.383     1782709.839      318345.555
#Sta/Elev= 30
       0 1114.79    58.5 1096.85    68.2 1093.19    97.5 1080.51   107.2 1076.83
   126.7 1071.08   146.2 1066.75     156 1064.01   165.7  1058.9   214.5 1023.64
   224.2 1017.12     234 1013.41  240.75 1012.63   243.7 1012.37   253.5 1012.79
   262.1 1014.09   282.7 1017.51   360.7 1025.58   419.2  1032.4   438.7  1034.3
   448.4 1036.81   458.2 1041.31   477.7 1051.16   487.4 1055.35   516.7 1066.54
   545.9    1076   555.7 1079.51   565.4  1083.5   584.9 1092.65   594.7 1095.85
#Mann= 3 , 0 , 0
       0      .1       0  240.75    .045       0   262.1     .08       0
Bank Sta=240.75,262.1
XS Rating Curve= 0 ,0
Exp/Cntr=0.3,0.1

Type RM Length L Ch R = 1 ,17556.2 ,285.3,290.8,296.3
XS GIS Cut Line= 2
     1782086.017      318525.545     1782642.302      318632.916
#Sta/Elev= 30
       0  1084.2    29.3 1081.78    39.1 1080.52    58.6 1076.92    97.7 1067.55
   136.8 1056.92   166.1 1048.33   175.8 1045.27   185.6 1041.29   195.4 1034.56
   205.1 1025.77   214.9 1019.67   224.7 1017.59   263.7 1014.39   273.5 1012.73
   283.3 1011.52     293 1011.44   304.4 1012.84   322.4  1015.8   371.2  1021.6
   390.7 1023.56   400.5 1025.01   410.3 1028.76     420 1034.81   429.8 1041.67
   439.6 1048.01   449.3 1053.34   459.1 1058.03   498.2 1075.85   566.6 1102.35
#Mann= 3 , 0 , 0
       0      .1       0   283.3    .045       0   304.4    .055       0
Bank Sta=283.3,304.4
XS Rating Curve= 0 ,0
Exp/Cntr=0.3,0.1

Type RM Length L Ch R = 1 ,17265.4 ,334,336,338.1
XS GIS Cut Line= 2
     1782010.095      318723.458       1782533.3       318966.97
#Sta/Elev= 30
       0 1065.07    29.3 1061.58    48.9 1059.57    68.5 1058.11   107.6 1056.25
   117.4 1055.59   127.2 1054.05   136.9 1051.32   146.7  1047.9   166.3 1040.43
   176.1 1036.23   185.8 1031.18   205.4 1020.11   215.2 1016.53     225 1015.33
   273.9 1013.94     313 1013.31     325 1012.26   332.6 1011.59   342.4 1011.99
   361.9  1015.8   381.5 1017.89   391.2 1021.89   410.8 1034.72   420.6 1039.98
   449.9 1053.98   459.7 1058.42   469.5  1062.5   479.3 1065.67   577.1 1086.02
#Mann= 3 , 0 , 0
       0    .055       0     325    .045       0   342.4     .08       0
Bank Sta=325,342.4
XS Rating Curve= 0 ,0
Exp/Cntr=0.3,0.1

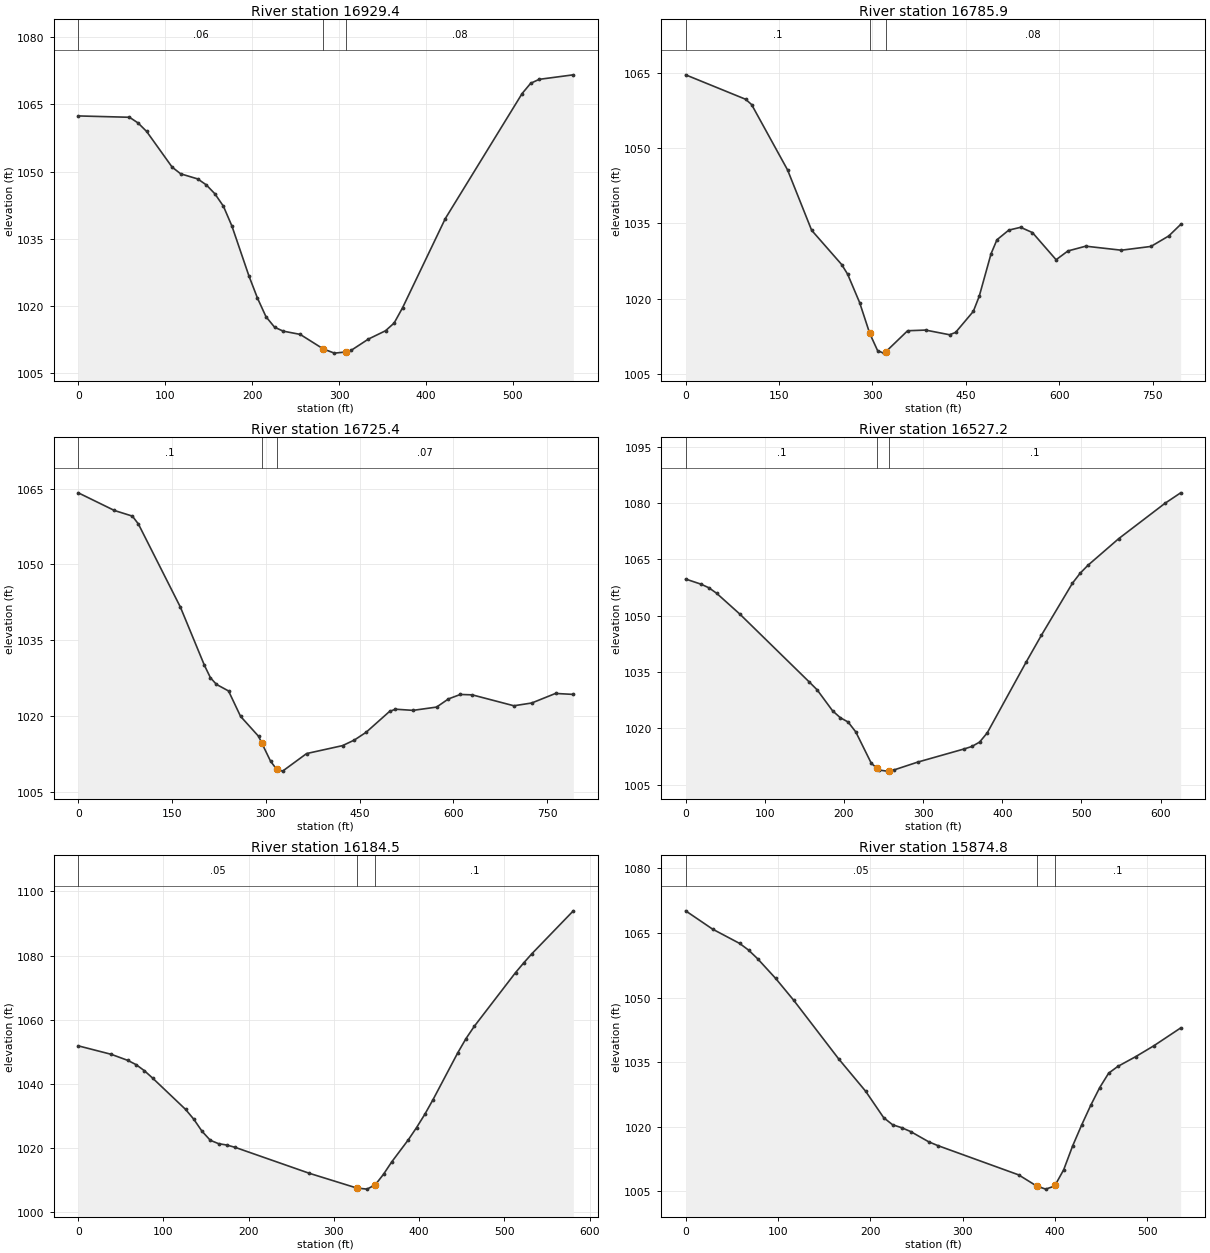
Type RM Length L Ch R = 1 ,16929.4 ,141.5,143.5,145.5
XS GIS Cut Line= 2
     1781865.712      318958.497     1782342.254      319270.478
#Sta/Elev= 30
       0 1062.43    58.9 1062.13    68.7 1060.87    78.6 1058.97     108 1050.98
   117.8 1049.49   137.5 1048.34   147.3 1047.01   157.1 1045.04     167 1042.24
   176.8  1037.8   196.4 1026.63   206.2 1021.69     216 1017.53   225.9 1015.19
   235.7 1014.32   255.3 1013.59   281.8 1010.35   294.6  1009.4  307.59 1009.65
   314.2 1010.05   333.9 1012.55   353.5  1014.4   363.4 1016.12   373.2 1019.57
   422.3 1039.48   510.7 1067.44   520.5 1069.72   530.3 1070.61   569.6 1071.62
#Mann= 3 , 0 , 0
       0     .06       0   281.8    .045       0  307.59     .08       0
Bank Sta=281.8,307.59
XS Rating Curve= 0 ,0
Exp/Cntr=0.3,0.1

Type RM Length L Ch R = 1 ,16785.9 ,60.4,60.5,60.7
XS GIS Cut Line= 4
     1781738.049      319008.454     1782090.015      319261.763
     1782137.118      319416.154     1782293.862      319540.554
#Sta/Elev= 30
       0 1064.56    96.4 1059.69     106 1058.63   163.8  1045.6   202.4  1033.6
   250.6 1026.78   260.2 1024.86   279.5  1019.2   295.7 1013.06   308.4 1009.62
     318 1009.13  321.18 1009.36   356.6 1013.59   385.5 1013.72     424 1012.79
   433.6 1013.25   462.1 1017.44   471.6 1020.45   490.6 1028.92   500.1 1031.71
   519.1 1033.63   538.1 1034.19   557.1 1033.14   595.1 1027.73   614.1 1029.48
   642.7 1030.43   699.9 1029.63   747.5 1030.38   776.1 1032.47   795.2 1034.76
#Mann= 3 , 0 , 0
       0      .1       0   295.7    .045       0  321.18     .08       0
Bank Sta=295.7,321.18
XS Rating Curve= 0 ,0
Exp/Cntr=0.3,0.1

Type RM Length L Ch R = 1 ,16725.4 ,187.3,198.1,208.8
XS GIS Cut Line= 4
        1781703.      319057.153     1782038.534      319298.635
     1782085.182      319451.535     1782256.562      319587.552
#Sta/Elev= 30
       0 1064.15    57.7 1060.66    86.5 1059.54    96.1 1057.99   163.4 1041.51
   201.9 1029.97   211.5 1027.52   221.1 1026.22   240.4 1024.92   259.6  1019.9
   288.4 1015.95  293.46 1014.64   307.6 1011.02   317.3 1009.42   326.9 1009.05
   365.3 1012.53   422.8  1014.1   441.6  1015.2   460.4 1016.73     498 1020.87
   507.4 1021.31   535.6 1021.08   573.2 1021.73   592.3 1023.35   611.3 1024.23
   630.3 1024.15   696.9 1021.99   725.5 1022.54   763.5 1024.43     792 1024.24
#Mann= 3 , 0 , 0
       0      .1       0  293.46    .045       0   317.3     .07       0
Bank Sta=293.46,317.3
XS Rating Curve= 0 ,0
Exp/Cntr=0.3,0.1

Type RM Length L Ch R = 1 ,16527.2 ,329.9,342.8,355.6
XS GIS Cut Line= 2
     1781688.749      319142.861     1781971.425      319700.599
#Sta/Elev= 30
       0 1059.75    19.5 1058.38    29.3 1057.43    39.1 1055.97    68.4 1050.43
   156.3 1032.31   166.1 1030.25   185.6 1024.67   195.4 1022.82   205.2 1021.68
   214.9 1019.05   234.5  1010.7   241.9 1009.33   244.2  1008.9     254  1008.6
   256.9 1008.71   263.8 1008.96   293.1    1011   351.7  1014.5   361.5 1015.16
   371.3 1016.33     381  1018.8   429.9 1037.56   449.4 1044.79   488.5 1058.61
   498.3 1061.29     508 1063.38   547.1 1070.52   605.7 1079.95   625.3 1082.71
#Mann= 3 , 0 , 0
       0      .1       0   241.9    .045       0   256.9      .1       0
Bank Sta=241.9,256.9
XS Rating Curve= 0 ,0
Exp/Cntr=0.3,0.1

Type RM Length L Ch R = 1 ,16184.5 ,300.8,309.6,318.4
XS GIS Cut Line= 2
     1781535.032      319175.462     1781477.741      319753.587
#Sta/Elev= 30
       0 1051.85    38.7 1049.21    58.1 1047.32    67.8    1046    77.5 1044.12
    87.1 1041.84   125.9 1032.05   135.6 1028.97   145.2 1025.24   154.9 1022.43
   164.6 1021.37   174.3 1020.94     184 1020.23   271.1 1012.14   326.9 1007.54
   338.9  1007.2   348.6 1008.57   358.3 1011.86   367.9  1015.7   387.3 1022.56
     397 1026.37   406.7 1030.52   416.4 1035.12   445.4  1049.7   455.1 1054.14
   464.8 1057.95   513.2 1074.68   522.9 1077.74   532.5  1080.6     581 1093.93
#Mann= 3 , 0 , 0
       0     .05       0   326.9    .045       0   348.6      .1       0
Bank Sta=326.9,348.6
XS Rating Curve= 0 ,0
Exp/Cntr=0.3,0.1

Type RM Length L Ch R = 1 ,15874.8 ,455.8,426.9,398
XS GIS Cut Line= 2
     1781425.657      319024.421     1781165.241      319493.171
#Sta/Elev= 30
       0 1070.13    29.2 1065.88    58.5 1062.56    68.2 1061.01      78    1059
    97.5 1054.44     117 1049.38   165.7 1035.77     195 1028.24   214.5 1022.11
   224.2 1020.46     234 1019.78   243.7 1018.89   263.2 1016.52     273 1015.64
   360.7 1008.83   380.2 1006.24     390 1005.52   399.7 1006.24   400.1 1006.39
   409.5 1010.02   419.2 1015.56     429 1020.43   438.7 1024.94   448.5 1029.09
   458.2 1032.44     468 1033.99   487.5 1036.28     507 1038.78   536.2 1042.94
#Mann= 3 , 0 , 0
       0     .05       0   380.2    .045       0   400.1      .1       0
Bank Sta=380.2,400.1
XS Rating Curve= 0 ,0
Exp/Cntr=0.3,0.1

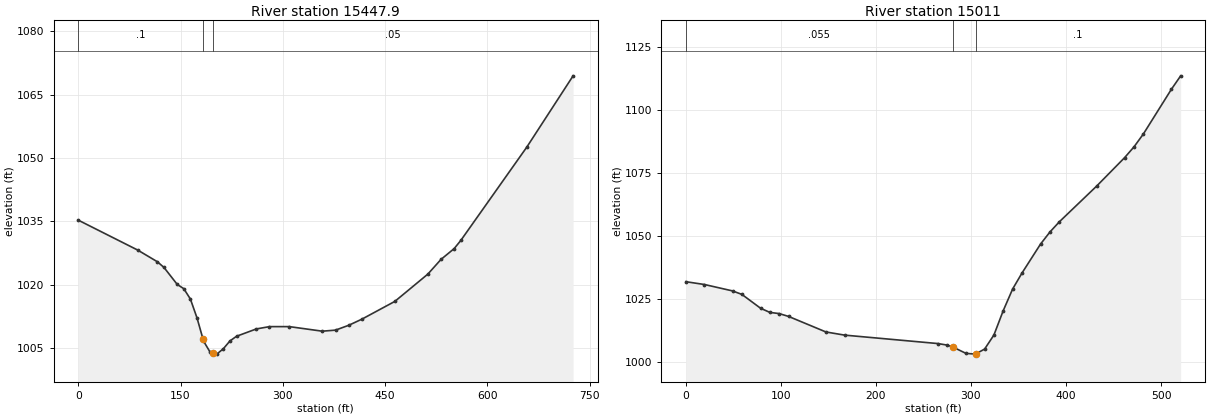
Type RM Length L Ch R = 1 ,15447.9 ,434.2,437,439.8
XS GIS Cut Line= 3
     1780758.611      319045.384     1781139.199      319430.671
     1781147.683      319614.488
#Sta/Elev= 30
       0  1035.3      87 1028.23     116 1025.45   125.7  1024.1   145.1 1020.09
   154.7 1019.08   164.4 1016.63   174.1 1012.16   182.7 1007.27   183.8 1006.64
   193.4 1004.03   197.7 1003.83   203.1 1003.59   212.8 1004.88   222.4 1006.71
   232.1 1007.82   261.1 1009.55   280.4  1010.1   309.5  1010.1   357.8 1009.02
   377.2 1009.27   396.5 1010.41   415.8 1011.86   464.2 1016.07   512.6 1022.53
   531.9 1026.01   551.2 1028.57   560.9 1030.49   657.8 1052.61   725.6 1069.46
#Mann= 3 , 0 , 0
       0      .1       0   182.7    .045       0   197.7     .05       0
Bank Sta=182.7,197.7
XS Rating Curve= 0 ,0
Exp/Cntr=0.3,0.1

Type RM Length L Ch R = 1 ,15011   ,280.9,297.6,314.3
XS GIS Cut Line= 2
     1780708.947      319373.615     1781024.693      319787.656
#Sta/Elev= 30
       0 1031.95    19.6 1030.84    49.1  1028.3      59 1026.91    78.6 1021.43
    88.4 1019.78    98.2 1019.31   108.1 1018.18   147.4 1012.02     167 1010.77
   265.3 1007.42   275.1  1006.8  280.96 1006.04   294.7 1003.54   304.6 1003.23
  305.08 1003.33   314.4 1005.24   324.2 1010.83     334 1020.49   343.9 1029.08
   353.7 1035.38   373.3 1046.91   383.2  1051.7     393  1055.7   432.3 1069.88
   461.8 1081.19   471.6 1085.44   481.4 1090.51   510.9 1108.25   520.7  1113.6
#Mann= 3 , 0 , 0
       0    .055       0  280.96    .045       0  305.08      .1       0
Bank Sta=280.96,305.08
XS Rating Curve= 0 ,0
Exp/Cntr=0.3,0.1