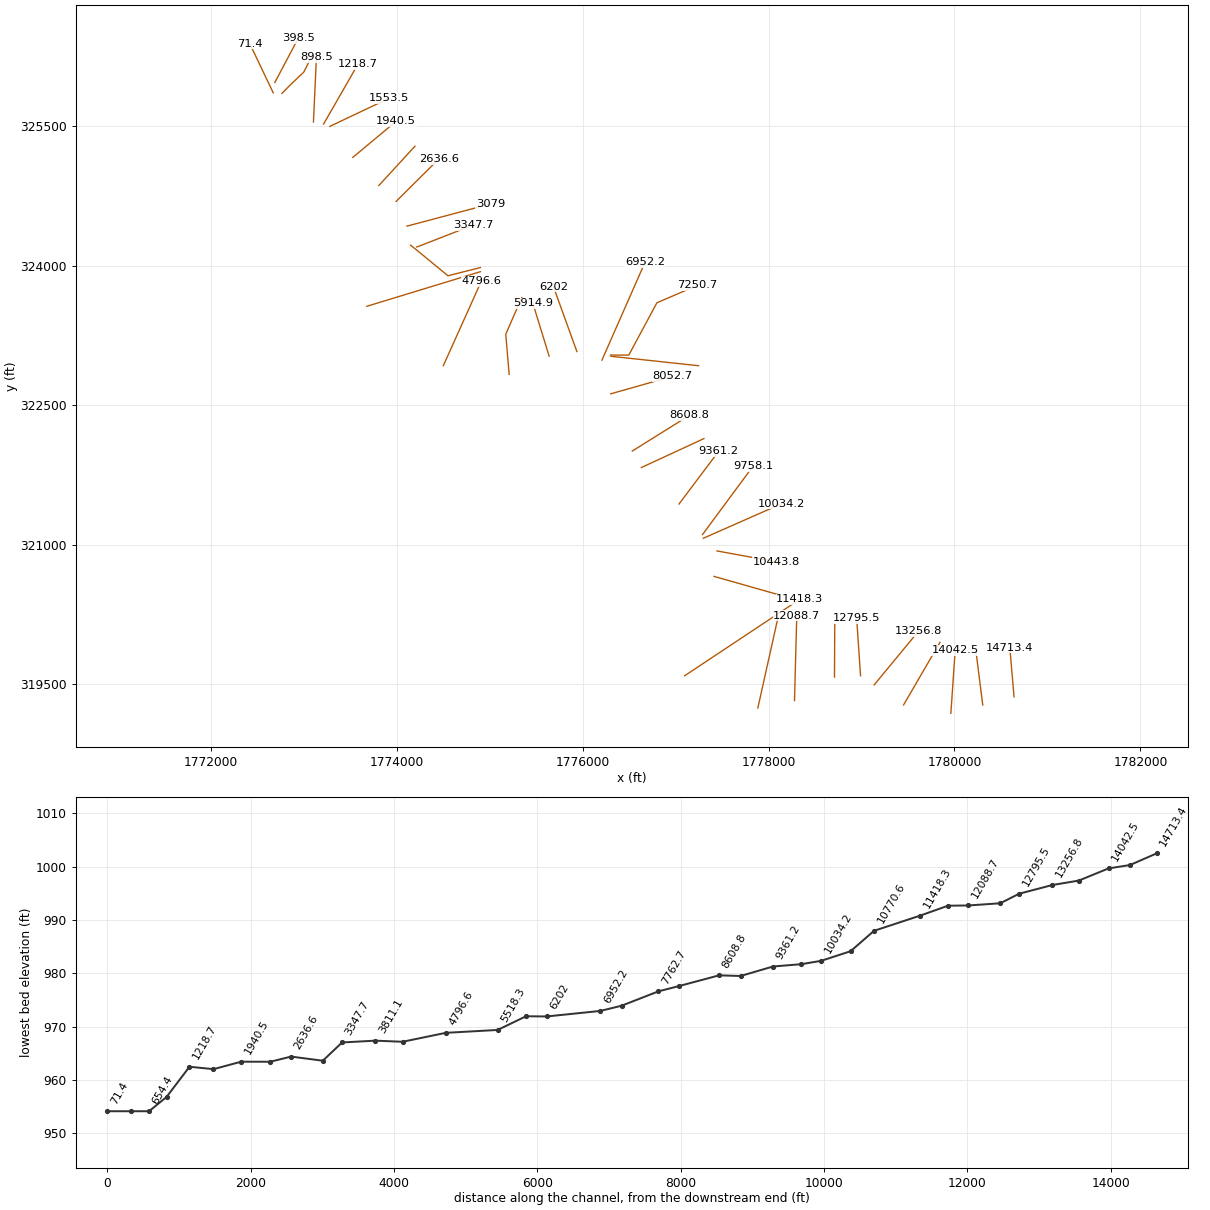
HEC-RAS study HusteadFrk.prj: HusteadFrk

--- HusteadFrk.g01 (geometry) --- (continued)

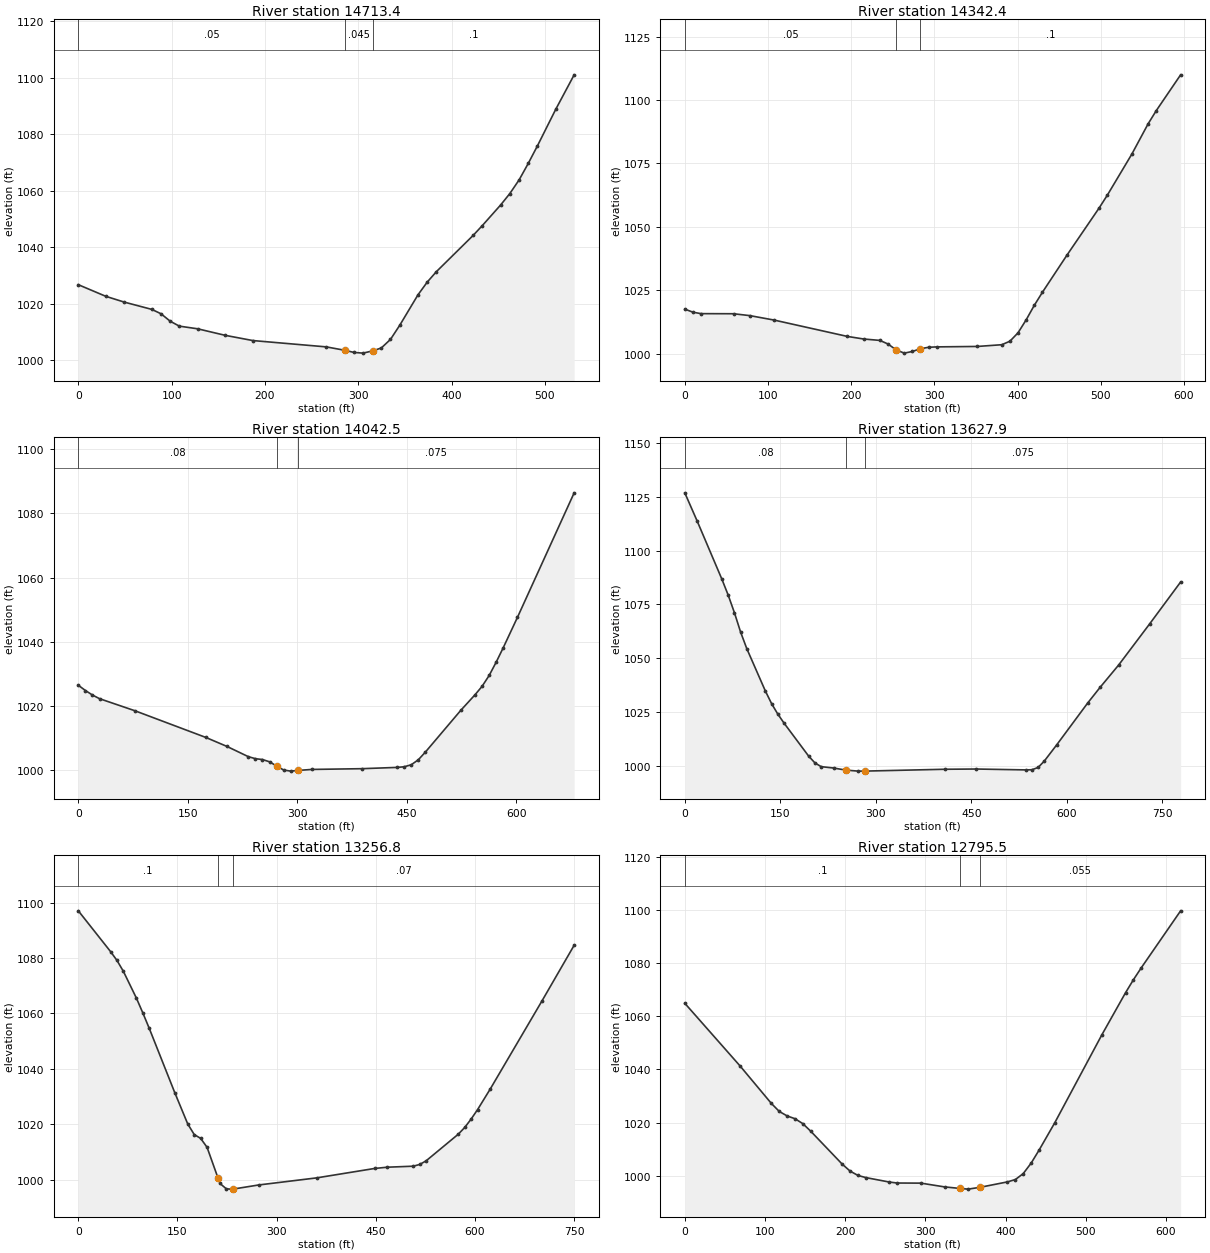
Type RM Length L Ch R = 1 ,14713.4 ,370.2,370.9,371.9
XS GIS Cut Line= 2
      1780640.51      319366.002     1780595.065      319895.375
#Sta/Elev= 30
       0 1026.73    29.5 1022.61    49.2 1020.57    78.7 1017.99    88.6 1016.44
    98.4 1013.81   108.2 1012.06   127.9 1011.11   157.4  1008.8     187 1006.95
   265.7 1004.71   285.81003.491   295.2 1002.76     305  1002.5   315.8 1003.32
   324.7 1004.34   334.5 1007.37   344.4 1012.36     364 1023.17   373.9 1027.67
   383.7 1031.36   423.1  1044.2   432.9 1047.67   452.6 1054.99   462.4 1059.02
   472.3 1063.84   482.1 1069.67     492 1075.93   511.6 1088.86   531.3 1101.05
#Mann= 3 , 0 , 0
       0     .05       0   285.8    .045       0   315.8      .1       0
Bank Sta=285.8,315.8
XS Rating Curve= 0 ,0
Exp/Cntr=0.3,0.1

Type RM Length L Ch R = 1 ,14342.4 ,304.2,299.9,295.4
XS GIS Cut Line= 2
     1780304.106      319277.683     1780229.343      319868.973
#Sta/Elev= 30
       0 1017.65     9.8 1016.44    19.5 1015.87    58.6 1015.83    78.2 1015.09
   107.5 1013.33   195.4  1006.9     215 1005.88   234.5 1005.33   244.3 1003.91
     254  1001.6   263.8 1000.32   273.6 1000.98   283.3 1002.06   293.1 1002.62
   302.9 1002.78   351.7 1002.95     381 1003.63   390.8 1005.01   400.6 1008.34
   410.4 1013.47   420.1 1019.14   429.9  1024.3   459.2 1038.83   498.3  1057.6
   508.1 1062.64   537.4 1078.72   556.9 1090.61   566.7 1095.81     596 1109.92
#Mann= 3 , 0 , 0
       0     .05       0     254    .045       0   283.3      .1       0
Bank Sta=254,283.3
XS Rating Curve= 0 ,0
Exp/Cntr=0.3,0.1

Type RM Length L Ch R = 1 ,14042.5 ,424.3,414.6,404.7
XS GIS Cut Line= 2
      1779961.03      319187.613     1780007.329      319865.623
#Sta/Elev= 30
       0 1026.45     9.7 1024.81    19.4  1023.4    29.1 1022.26    77.7 1018.49
   174.8 1010.18   203.9 1007.36     233 1004.19   242.7 1003.56   252.4 1003.29
   262.1 1002.59   272.3  1001.2   281.5 1000.02   291.2  999.68     301   999.9
   320.4 1000.21   388.3 1000.44   436.9 1000.84   446.6 1001.04   456.3 1001.66
     466 1003.22   475.7 1005.62   524.2 1018.63   543.7 1023.48   553.4 1026.12
   563.1  1029.5   572.8 1033.69   582.5  1038.2   601.9 1047.63   679.6 1086.44
#Mann= 3 , 0 , 0
       0     .08       0   272.3    .045       0     301    .075       0
Bank Sta=272.3,301
XS Rating Curve= 0 ,0
Exp/Cntr=0.3,0.1

Type RM Length L Ch R = 1 ,13627.9 ,375,371.1,366.7
XS GIS Cut Line= 2
     1779452.389      319278.243     1779843.636      319951.452
#Sta/Elev= 30
       0 1126.85    19.5 1113.67    58.4 1086.57    68.1  1079.3    77.9 1071.12
    87.6 1062.11    97.3 1054.41   126.5 1034.68   136.3 1028.79     146 1023.95
   155.7 1019.79   194.7  1004.3   204.4 1001.22   214.1  999.48   233.6  998.85
   253.1  997.86   272.5   997.4   282.3  997.41   408.8  998.27   457.4  998.38
   535.3  997.97     545  998.04   554.8   999.1   564.5 1002.07     584 1009.61
   632.6 1029.06   652.1 1036.35   681.3 1046.76     730  1065.9   778.6 1085.37
#Mann= 3 , 0 , 0
       0     .08       0   253.1    .045       0   282.3    .075       0
Bank Sta=253.1,282.3
XS Rating Curve= 0 ,0
Exp/Cntr=0.3,0.1

Type RM Length L Ch R = 1 ,13256.8 ,443.9,461.3,478.4
XS GIS Cut Line= 2
     1779135.814      319493.668     1779613.416      320072.163
#Sta/Elev= 30
       0 1097.06    48.7 1082.36    58.5 1079.14    68.2 1075.19    87.7 1065.63
    97.4  1060.3   107.2 1054.68   146.1 1031.29   165.6 1020.06   175.4 1016.26
   185.1 1014.88   194.8 1011.65   211.1 1000.72   214.3   998.6   224.1  996.64
   233.8  996.56   272.8  998.06   360.5 1000.62   448.2 1004.02   467.6 1004.48
   506.6 1004.84   516.4 1005.46   526.1 1006.76   574.8 1016.38   584.6 1018.82
   594.3 1021.86     604 1025.25   623.5 1032.82   701.5 1064.52   750.2 1084.63
#Mann= 3 , 0 , 0
       0      .1       0   211.1    .045       0   233.8     .07       0
Bank Sta=211.1,233.8
XS Rating Curve= 0 ,0
Exp/Cntr=0.3,0.1

Type RM Length L Ch R = 1 ,12795.5 ,265.9,263.8,261.9
XS GIS Cut Line= 2
     1778989.624      319593.119     1778947.672      320210.038
#Sta/Elev= 30
       0 1064.95    68.7 1041.41     108  1027.2   117.8  1024.2   127.6 1022.51
   137.4 1021.46   147.2  1019.6     157 1016.76   196.3 1004.34   206.1 1001.73
   215.9 1000.09   225.7  999.28   255.2  997.59     265  997.23   294.4  997.19
   323.9  995.77   343.5  995.18   353.3  994.93  368.15  995.61   402.4  997.66
   412.2  998.54     422 1000.77   431.9 1004.73   441.7 1009.58   461.3  1019.9
   520.2 1053.13   549.6 1068.92   559.4  1073.8   569.3 1078.35   618.3 1099.78
#Mann= 3 , 0 , 0
       0      .1       0   343.5    .045       0  368.15    .055       0
Bank Sta=343.5,368.15
XS Rating Curve= 0 ,0
Exp/Cntr=0.3,0.1

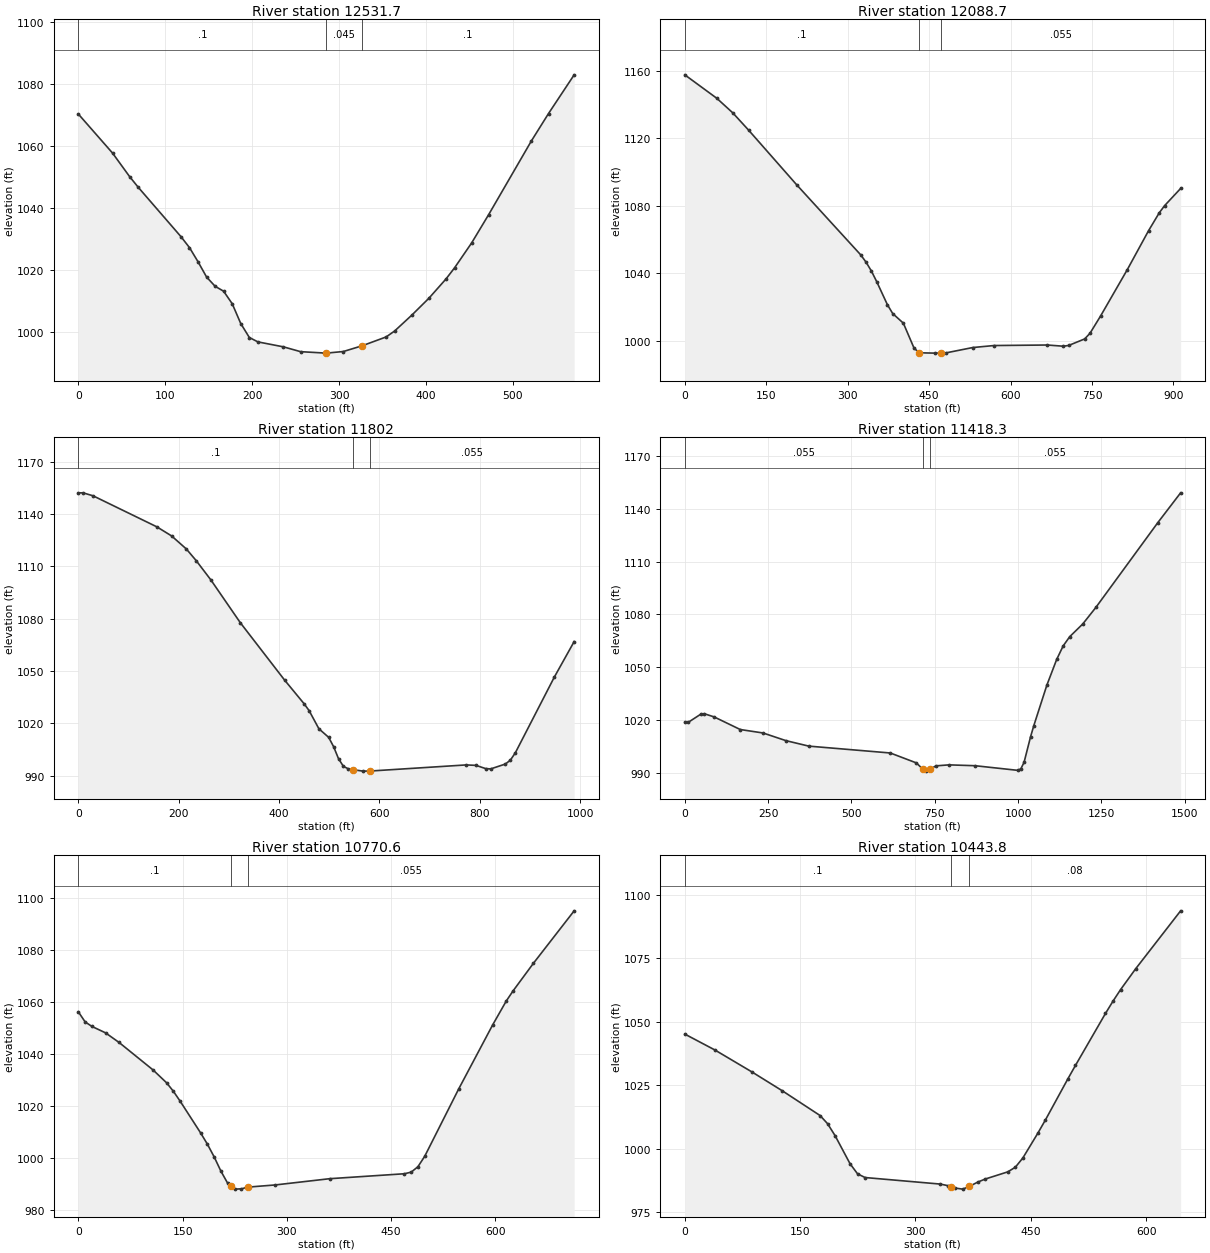
Type RM Length L Ch R = 1 ,12531.7 ,442.9,443,442.6
XS GIS Cut Line= 2
     1778709.246      319577.706     1778712.185      320148.332
#Sta/Elev= 30
       0  1070.3    39.4 1057.69      59 1050.11    68.9 1046.67   118.1 1030.73
   127.9  1027.2   137.7 1022.65   147.6 1017.69   157.4 1014.72   167.2 1013.12
   177.1 1009.08   186.9  1002.7   196.8  998.18   206.6  996.77   236.1  995.16
   255.8  993.61   285.3  993.14     305  993.66   326.8995.5286   354.2  998.36
     364 1000.28   383.7 1005.38   403.4 1010.84   423.1 1017.07   432.9 1020.64
   452.6 1028.69   472.2 1037.83   521.4 1061.63   541.1 1070.46   570.6 1082.95
#Mann= 3 , 0 , 0
       0      .1       0   285.3    .045       0   326.8      .1       0
Bank Sta=285.3,326.8
XS Rating Curve= 0 ,0
Exp/Cntr=0.3,0.1

Type RM Length L Ch R = 1 ,12088.7 ,291.1,286.7,282.4
XS GIS Cut Line= 2
     1778279.092      319324.893     1778303.636       320237.82
#Sta/Elev= 30
       0  1157.7    58.9 1143.81    88.4 1135.15   117.8 1124.82   206.2 1092.47
   324.1 1050.96   333.9 1046.64   343.7  1041.4   353.5  1035.1   373.2 1021.43
     383 1016.18   402.6 1010.48   422.3  995.67   432.1  992.92   461.5  992.73
   471.4  992.74   481.2  992.88   530.3  996.04   569.6  997.23   667.8  997.54
   697.2  996.83     707  997.27   736.5 1001.14   746.3 1004.46     766 1014.81
   815.1 1042.23   854.3 1065.34     874 1075.94   883.8 1080.15   913.3 1090.34
#Mann= 3 , 0 , 0
       0      .1       0   432.1    .045       0   471.4    .055       0
Bank Sta=432.1,471.4
XS Rating Curve= 0 ,0
Exp/Cntr=0.3,0.1

Type RM Length L Ch R = 1 ,11802   ,401,383.7,366.4
XS GIS Cut Line= 2
     1777884.991      319245.903     1778099.666      320210.365
#Sta/Elev= 30
       0 1152.06     9.8 1152.03    29.4 1150.35   156.5 1132.58   185.9 1127.37
   215.2 1119.92   234.8 1113.26   264.1  1102.2   322.8 1077.68   410.9 1044.87
     450 1031.24   459.8 1027.38   479.4 1016.94   498.9 1012.02   508.7 1006.69
   518.5  999.81   528.3  995.39   538.1     994   547.8  993.49   567.4  992.68
   581.1992.7239   772.8  996.23   792.4  995.98     812  994.11   821.8  993.96
   851.1  996.75   860.9  998.95   870.7 1003.08   948.9  1046.7   988.1 1066.88
#Mann= 3 , 0 , 0
       0      .1       0   547.8    .045       0   581.1    .055       0
Bank Sta=547.8,581.1
XS Rating Curve= 0 ,0
Exp/Cntr=0.3,0.1

Type RM Length L Ch R = 1 ,11418.3 ,667.4,647.7,628.7
XS GIS Cut Line= 2
     1777097.532      319592.129     1778337.116      320415.046
#Sta/Elev= 30
       0 1018.64     9.8 1018.54    48.9 1023.36    58.7 1023.49    88.1 1021.68
   166.4 1014.51   234.9 1012.54   303.4 1008.19     372 1005.07   616.7 1001.16
     695  995.51   714.6  991.88   724.4  990.84   734.5  991.78   753.7  993.84
   792.9   994.4   871.2  993.92   998.4   991.3  1008.2  992.07    1018   995.8
  1037.6 1010.39  1047.4 1016.76  1086.5 1039.76  1115.9 1054.36  1135.5  1062.1
  1155.1 1067.34  1194.2 1074.56  1233.4 1083.94  1419.4 1132.21  1487.9 1149.18
#Mann= 3 , 0 , 0
       0    .055       0   714.6    .045       0   734.5    .055       0
Bank Sta=714.6,734.5
XS Rating Curve= 0 ,0
Exp/Cntr=0.3,0.1

Type RM Length L Ch R = 1 ,10770.6 ,324.5,326.8,328.4
XS GIS Cut Line= 2
     1777413.342      320660.893     1778099.704      320466.226
#Sta/Elev= 30
       0 1056.14     9.8 1052.25    19.6 1050.51    39.1 1048.06    58.6 1044.36
   107.5 1033.79     127 1028.85   136.8 1025.57   146.6 1021.74   175.9  1009.6
   185.7 1005.25   195.5 1000.33   205.2  994.86     215  990.17  219.91  989.04
   224.8  987.97   234.6  988.08   244.3  988.75   283.4  989.58   361.6  991.98
   469.1  993.88   478.9   994.5   488.6  996.58   498.4  1000.6   547.3  1026.5
   596.2 1051.13   615.7 1060.28   625.5 1064.18   654.8  1074.8   713.4 1094.96
#Mann= 3 , 0 , 0
       0      .1       0  219.91    .045       0   244.3    .055       0
Bank Sta=219.91,244.3
XS Rating Curve= 0 ,0
Exp/Cntr=0.3,0.1

Type RM Length L Ch R = 1 ,10443.8 ,396.1,409.6,423
XS GIS Cut Line= 2
     1777445.222      320934.874     1778079.514      320818.839
#Sta/Elev= 30
       0 1045.14    39.1 1038.89    87.9 1030.14     127 1022.79   175.9  1013.1
   185.6 1009.91   195.4  1005.2   214.9  994.13   224.7  990.14   234.5   988.7
   332.2  986.13     342  985.52  346.46  985.06   351.7  984.55   361.5  984.14
   370.1  985.23     381  986.91   390.8  988.12   420.1  990.94   429.9  992.77
   439.6  996.39   459.2 1006.19     469 1011.37   498.3  1027.6     508 1032.79
   547.1 1053.27   556.9 1058.12   566.7 1062.63   586.2 1070.78   644.8 1093.63
#Mann= 3 , 0 , 0
       0      .1       0  346.46    .045       0   370.1     .08       0
Bank Sta=346.46,370.1
XS Rating Curve= 0 ,0
Exp/Cntr=0.3,0.1

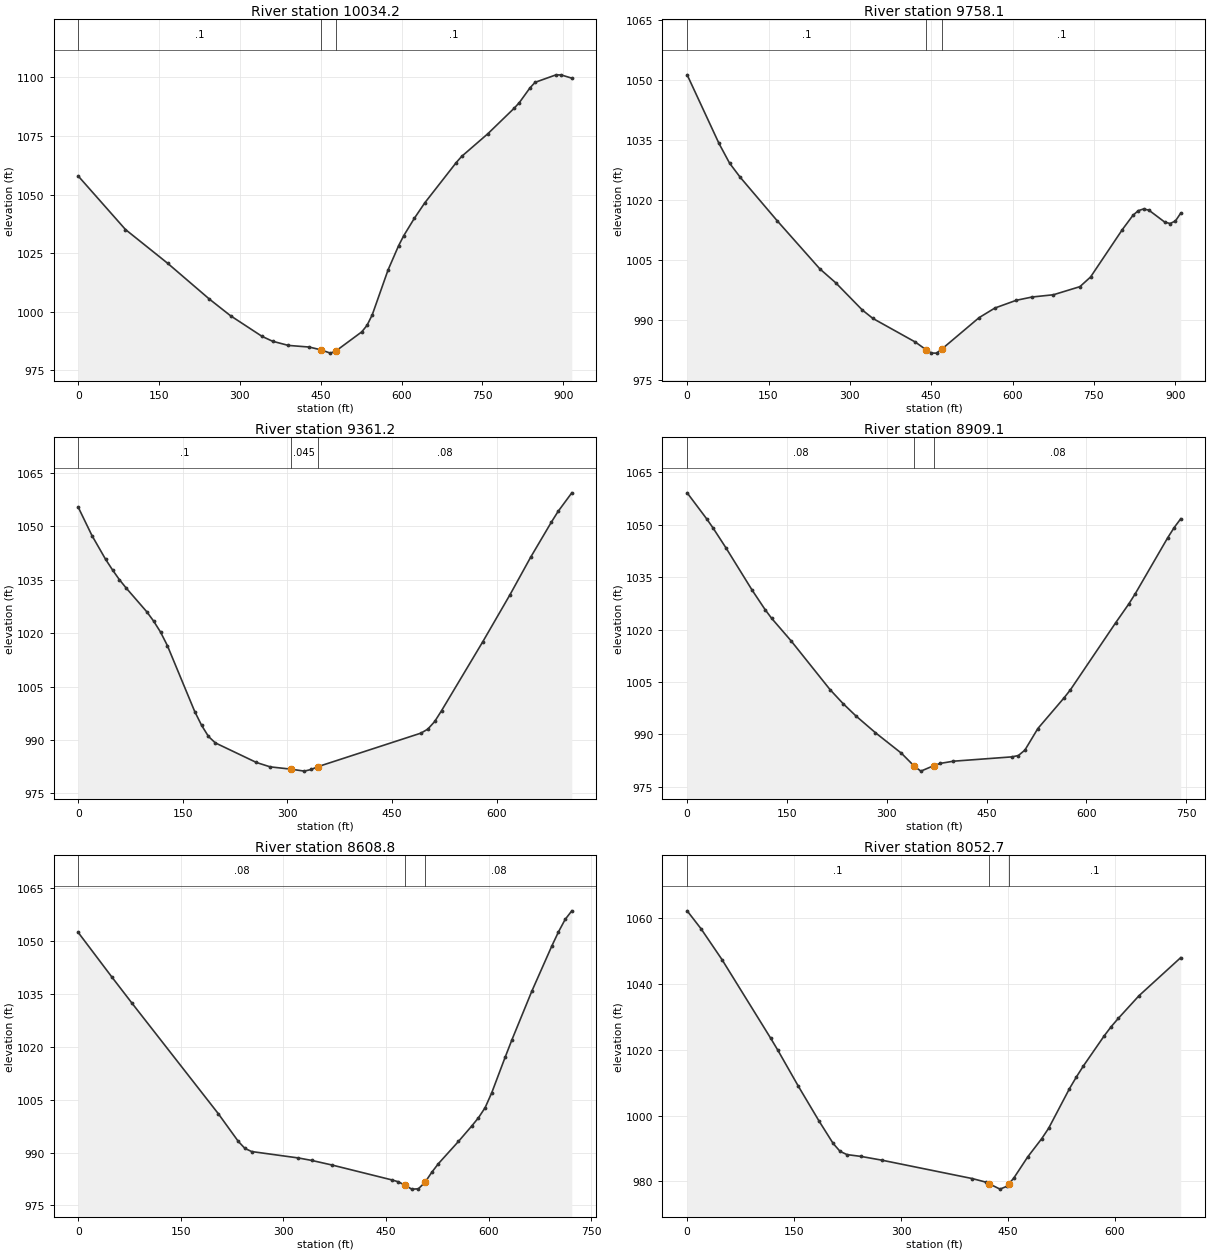
Type RM Length L Ch R = 1 ,10034.2 ,264.4,276.1,287.8
XS GIS Cut Line= 2
     1777298.351      321071.063     1778136.553      321440.607
#Sta/Elev= 30
       0 1057.93    87.7  1035.1   165.7 1020.74   243.6 1005.37   282.6  998.31
   341.1   989.5   360.6  987.42   389.8  985.64   428.8  984.93   450.9  983.72
   467.8  982.34   477.5  983.14   526.2  991.42     536  994.21   545.7  998.72
     575 1017.84   594.5 1028.17   604.2 1032.51   623.7 1039.86   643.2  1046.5
   701.6  1063.7   711.4 1066.27   760.1 1075.97   808.8 1086.82   818.6 1089.26
   838.1 1095.48   847.8 1097.92   886.8 1101.13   896.6 1101.06     916 1099.71
#Mann= 3 , 0 , 0
       0      .1       0   450.9    .045       0   477.5      .1       0
Bank Sta=450.9,477.5
XS Rating Curve= 0 ,0
Exp/Cntr=0.3,0.1

Type RM Length L Ch R = 1 ,9758.1  ,397.2,396.9,396.7
XS GIS Cut Line= 2
     1777290.613      321112.085     1777831.795      321843.674
#Sta/Elev= 30
       0 1051.38    58.7  1034.2    78.3 1029.25    97.8 1025.74   166.3  1014.8
   244.6 1002.81     274  999.31   322.9  992.51   342.5  990.39   420.8  984.47
   440.3  982.58   450.1  981.72   459.8  981.71   469.7  982.74   538.2  990.59
   567.5  993.01   606.7  994.93     636  995.76   675.2  996.32   724.1  998.35
   743.7 1000.76   802.4 1012.65   821.9 1016.21   831.7 1017.37   841.5  1017.8
   851.3  1017.5   880.6  1014.5   890.4 1014.16   900.2 1014.79     910 1016.76
#Mann= 3 , 0 , 0
       0      .1       0   440.3    .045       0   469.7      .1       0
Bank Sta=440.3,469.7
XS Rating Curve= 0 ,0
Exp/Cntr=0.3,0.1

Type RM Length L Ch R = 1 ,9361.2  ,462.6,452.1,441.5
XS GIS Cut Line= 2
     1777037.086       321439.25     1777462.182      322005.115
#Sta/Elev= 30
       0 1055.28    19.7 1047.33    39.3 1040.65    49.2 1037.69      59 1034.97
    68.8 1032.61    98.3 1025.96   108.1 1023.35     118 1020.28   127.8 1016.49
   167.1  997.97   176.9  994.12   186.8  990.99   196.6  989.19   255.6  983.69
   275.2  982.47   304.7  981.83   324.2  981.27   334.2  981.74     344  982.54
   491.5  991.93   501.3  993.05   511.2  995.19     521  998.22     580 1017.51
   619.3 1030.79   648.8 1041.26   678.3 1051.03   688.1 1054.09   707.8 1059.31
#Mann= 3 , 0 , 0
       0      .1       0   304.7    .045       0     344     .08       0
Bank Sta=304.7,344
XS Rating Curve= 0 ,0
Exp/Cntr=0.3,0.1

Type RM Length L Ch R = 1 ,8909.1  ,297.9,300.3,302.3
XS GIS Cut Line= 2
     1776632.102      321831.716     1777305.281      322143.053
#Sta/Elev= 30
       0 1059.12    29.3 1051.69      39 1049.04    58.6 1043.29    97.6 1031.29
   117.1 1025.72   126.9 1023.23   156.1 1016.79   214.7 1002.82   234.2  998.83
   253.7  995.27     283  990.47     322  984.61   341.6  980.85   351.2  979.49
   370.8  981.07   380.6  981.71   400.1  982.33     488  983.57   497.7  983.95
   507.5   985.5     527  991.68     566 1000.37   575.8 1002.73   644.1 1021.99
   663.6 1027.31   673.4 1030.27   722.2 1046.29   731.9 1049.19   741.7 1051.71
#Mann= 3 , 0 , 0
       0     .08       0   341.6    .045       0   370.8     .08       0
Bank Sta=341.6,370.8
XS Rating Curve= 0 ,0
Exp/Cntr=0.3,0.1

Type RM Length L Ch R = 1 ,8608.8  ,563.1,556.1,549.1
XS GIS Cut Line= 2
     1776534.688      322009.263     1777146.851      322391.622
#Sta/Elev= 30
       0 1052.48    48.8 1039.93      78 1032.56   204.8 1001.04   234.1  993.16
   243.8  991.17   253.6  990.28   321.9  988.46   341.4  987.76   370.6  986.48
   458.4  982.24   468.2  981.69   477.9  980.72   487.7  979.61   497.4  979.69
   507.2  981.56   516.9  984.36   526.7  986.84     556  993.14   575.5  997.54
   585.2  999.85     595 1002.72   604.7 1006.96   624.2    1017     634  1021.9
   663.2 1035.75   692.5  1048.6   702.3 1052.64     712 1056.16   721.8 1058.62
#Mann= 3 , 0 , 0
       0     .08       0   477.9    .045       0   507.2     .08       0
Bank Sta=477.9,507.2
XS Rating Curve= 0 ,0
Exp/Cntr=0.3,0.1

Type RM Length L Ch R = 1 ,8052.7  ,298,290,281.7
XS GIS Cut Line= 2
     1776302.163      322624.486     1776968.195      322813.158
#Sta/Elev= 30
       0 1062.26    19.5  1056.8    48.8 1047.45     117 1023.56   126.8 1020.01
     156 1008.89   185.2  998.24   204.8  991.49   214.5  989.09   224.2  988.11
   243.8  987.56     273  986.42   399.7  980.83   419.2  979.72  423.68  979.23
   438.7  977.61   448.5  978.48  451.49  979.28   458.2  981.01   477.7  987.44
   497.2  992.95     507  996.14   536.2 1008.19     546 1011.78   555.7 1015.08
     585 1024.27   594.7 1027.04   604.5 1029.51   633.7 1036.45   692.2 1048.03
#Mann= 3 , 0 , 0
       0      .1       0  423.68    .045       0  451.49      .1       0
Bank Sta=423.68,451.49
XS Rating Curve= 0 ,0
Exp/Cntr=0.3,0.1

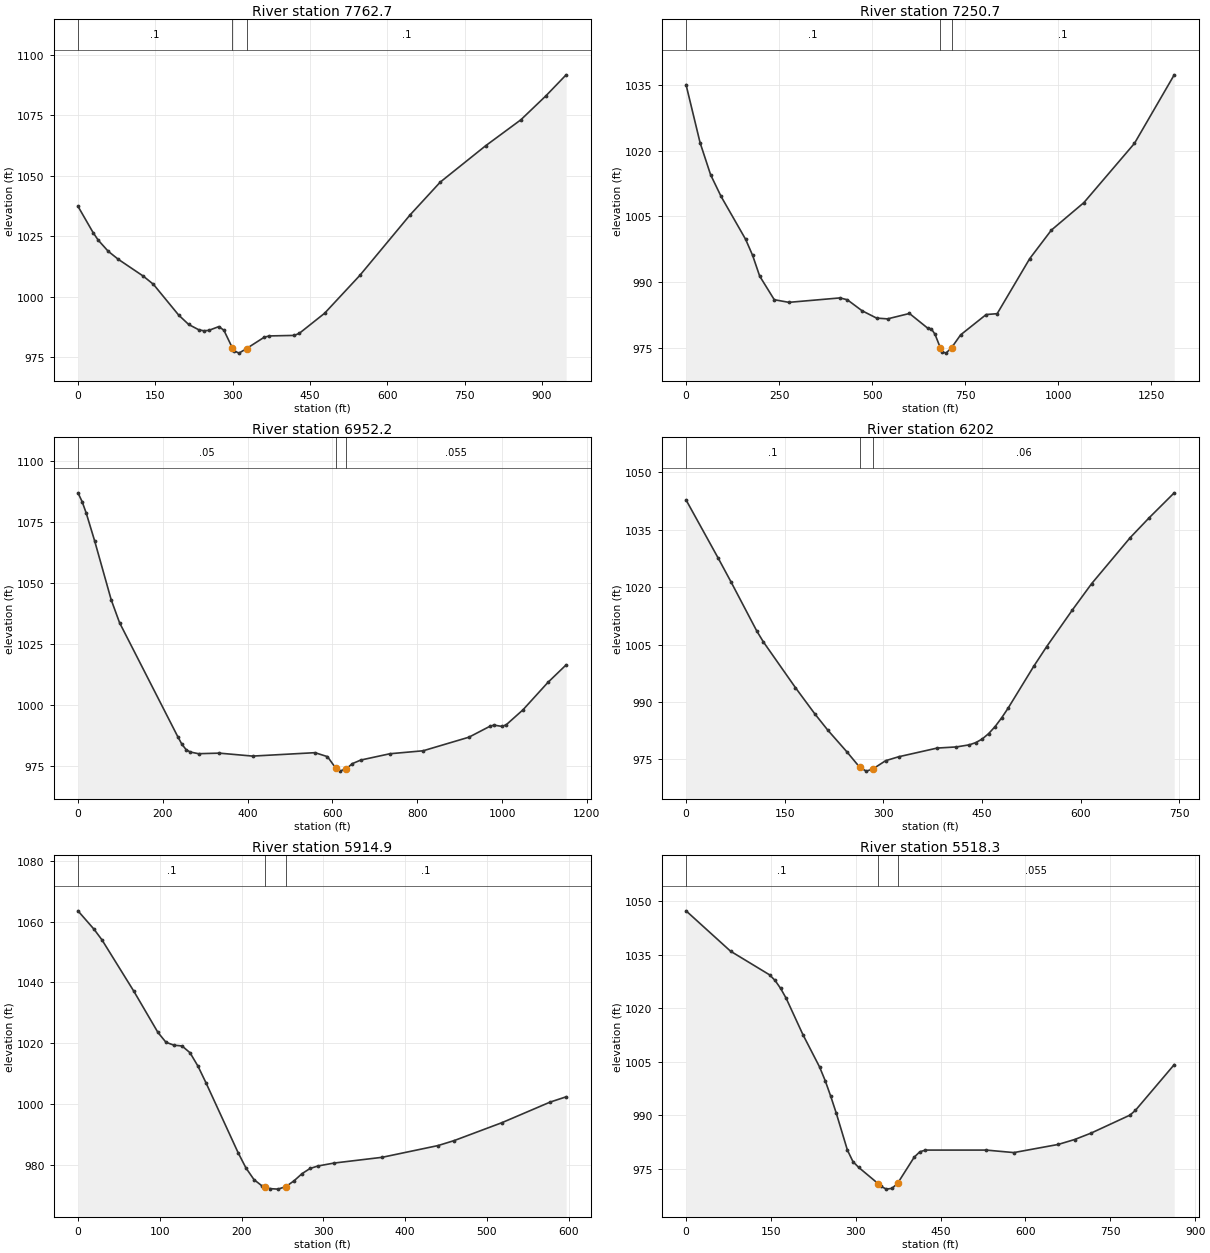
Type RM Length L Ch R = 1 ,7762.7  ,484.9,512,539.1
XS GIS Cut Line= 2
     1776306.099      323028.263     1777247.801      322926.811
#Sta/Elev= 30
       0 1037.37    29.3 1026.51    39.1 1023.41    58.6 1018.77    78.1 1015.45
   126.9 1008.44   146.5 1005.06   195.3  992.38   214.8  988.47   234.4  986.27
   244.1  985.85   253.9  986.02   273.4  987.59   283.2  986.07  299.62  978.75
   302.7  977.61   312.5  976.61  327.25  978.52   361.3  983.17     371  983.72
   419.9  983.94   429.6  984.82   478.5  993.09   546.8 1008.74   644.4 1033.79
     703 1047.37   790.9 1062.38   859.3 1073.13   908.1 1083.08   947.2 1091.74
#Mann= 3 , 0 , 0
       0      .1       0  299.62    .045       0  327.25      .1       0
Bank Sta=299.62,327.25
XS Rating Curve= 0 ,0
Exp/Cntr=0.3,0.1

Type RM Length L Ch R = 1 ,7250.7  ,296.4,298.5,300.3
XS GIS Cut Line= 4
     1776299.119      323041.377     1776497.036      323041.377
     1776799.119      323603.877     1777236.619      323791.377
#Sta/Elev= 30
       0 1034.98    37.7  1021.8      66  1014.5    94.2 1009.56   160.2   999.8
   179.1  996.13   197.9  991.45   237.2  986.07   276.5  985.47     414  986.48
   433.7  986.05     473  983.57   512.2  981.89   541.7  981.71   600.6  982.94
   649.8  979.59   659.6  979.43   669.4  978.19   683.9  975.07   689.1  974.23
   698.9  973.92   713.9975.1674   738.2  978.08   806.9   982.7   836.4  982.89
   923.8   995.4   982.1  1001.9  1069.5 1008.15  1205.5 1021.63  1312.4 1037.22
#Mann= 3 , 0 , 0
       0      .1       0   683.9    .045       0   713.9      .1       0
Bank Sta=683.9,713.9
XS Rating Curve= 0 ,0
Exp/Cntr=0.3,0.1

Type RM Length L Ch R = 1 ,6952.2  ,733,750.2,767.4
XS GIS Cut Line= 3
     1776207.894      322986.263     1776665.987       324027.51
     1776671.454      324039.938
#Sta/Elev= 30
       0 1087.12     9.8 1083.53    19.6 1078.76    39.2  1067.5    78.4 1043.23
    98.1 1033.83   235.4  987.06   245.2  983.92     255  981.77   264.8  980.77
   284.4  980.08   333.4  980.31   411.9   979.1     559   980.5   588.4  978.87
   607.6  974.22   617.8  972.93  633.13  973.98   647.2  976.02   666.8  977.47
   735.5  980.06   813.9  981.28   921.8  986.85   970.8  991.28   980.7  991.82
  1000.3  991.26  1010.1  991.99  1049.3  998.08  1108.1 1009.33  1151.1 1016.53
#Mann= 3 , 0 , 0
       0     .05       0   607.6    .045       0  633.13    .055       0
Bank Sta=607.6,633.13
XS Rating Curve= 0 ,0
Exp/Cntr=0.3,0.1

Type RM Length L Ch R = 1 ,6202    ,288,287.1,285.9
XS GIS Cut Line= 3
     1775938.397      323079.714     1775708.853      323715.047
     1775686.165      323777.842
#Sta/Elev= 30
       0 1042.82      49 1027.56    68.5 1021.34   107.7 1008.49   117.5 1005.71
   166.4  993.71   195.8  986.87   215.4  982.64   244.8  976.89   264.3  972.85
   274.1  971.89   283.9  972.44   303.5  974.62   323.1  975.64   381.8  977.92
   411.2  978.22   430.8  978.77   440.6  979.35   450.4   980.3   460.1   981.7
   469.9  983.54   479.7  985.78   489.5   988.3   528.7  999.31   548.2 1004.42
   587.4 1014.03   616.8 1020.94   675.5 1032.98   704.1 1038.13   742.3 1044.67
#Mann= 3 , 0 , 0
       0      .1       0   264.3    .045       0   283.9     .06       0
Bank Sta=264.3,283.9
XS Rating Curve= 0 ,0
Exp/Cntr=0.3,0.1

Type RM Length L Ch R = 1 ,5914.9  ,401.3,396.6,391.6
XS GIS Cut Line= 2
     1775640.037      323029.816     1775464.587      323600.226
#Sta/Elev= 30
       0 1063.61    19.6 1057.56    29.4 1054.03    68.5 1037.04    97.8 1023.54
   107.6 1020.31   117.4 1019.34   127.2  1019.1     137 1016.86   146.8  1012.4
   156.5 1006.97   195.7  983.99   205.4  978.89   215.2  975.07     225  972.99
   229.2   972.6   234.8  972.09   244.6  971.93   254.4  972.79   264.2  974.68
   273.9  977.02   283.7  978.73   293.5  979.56   313.1  980.52   371.8  982.41
   440.2  986.28   459.8  987.91   518.5  993.84   577.2  1000.6   596.8 1002.34
#Mann= 3 , 0 , 0
       0      .1       0   229.2    .045       0   254.4      .1       0
Bank Sta=229.2,254.4
XS Rating Curve= 0 ,0
Exp/Cntr=0.3,0.1

Type RM Length L Ch R = 1 ,5518.3  ,732.8,721.7,709.9
XS GIS Cut Line= 3
     1775210.061      322834.129     1775173.505      323265.491
     1775345.477      323659.649
#Sta/Elev= 30
       0 1047.26    78.7 1035.96   147.6 1029.35   157.4 1027.77   167.3 1025.52
   177.1 1022.75   206.6 1012.61   236.1 1003.54     246  999.72   255.8  995.34
   265.6   990.6   285.3  980.26   295.2  977.03     305  975.47  339.34  970.93
   344.4  970.16   354.2  969.36     364  969.58   373.9  970.96   403.4  978.32
   413.2   979.8   423.1  980.29   530.6  980.29   579.5  979.59   657.7  981.86
     687  983.25   716.3  985.06   784.8  990.08   794.5  991.43     863 1004.21
#Mann= 3 , 0 , 0
       0      .1       0  339.34    .045       0   373.9    .055       0
Bank Sta=339.34,373.9
XS Rating Curve= 0 ,0
Exp/Cntr=0.3,0.1

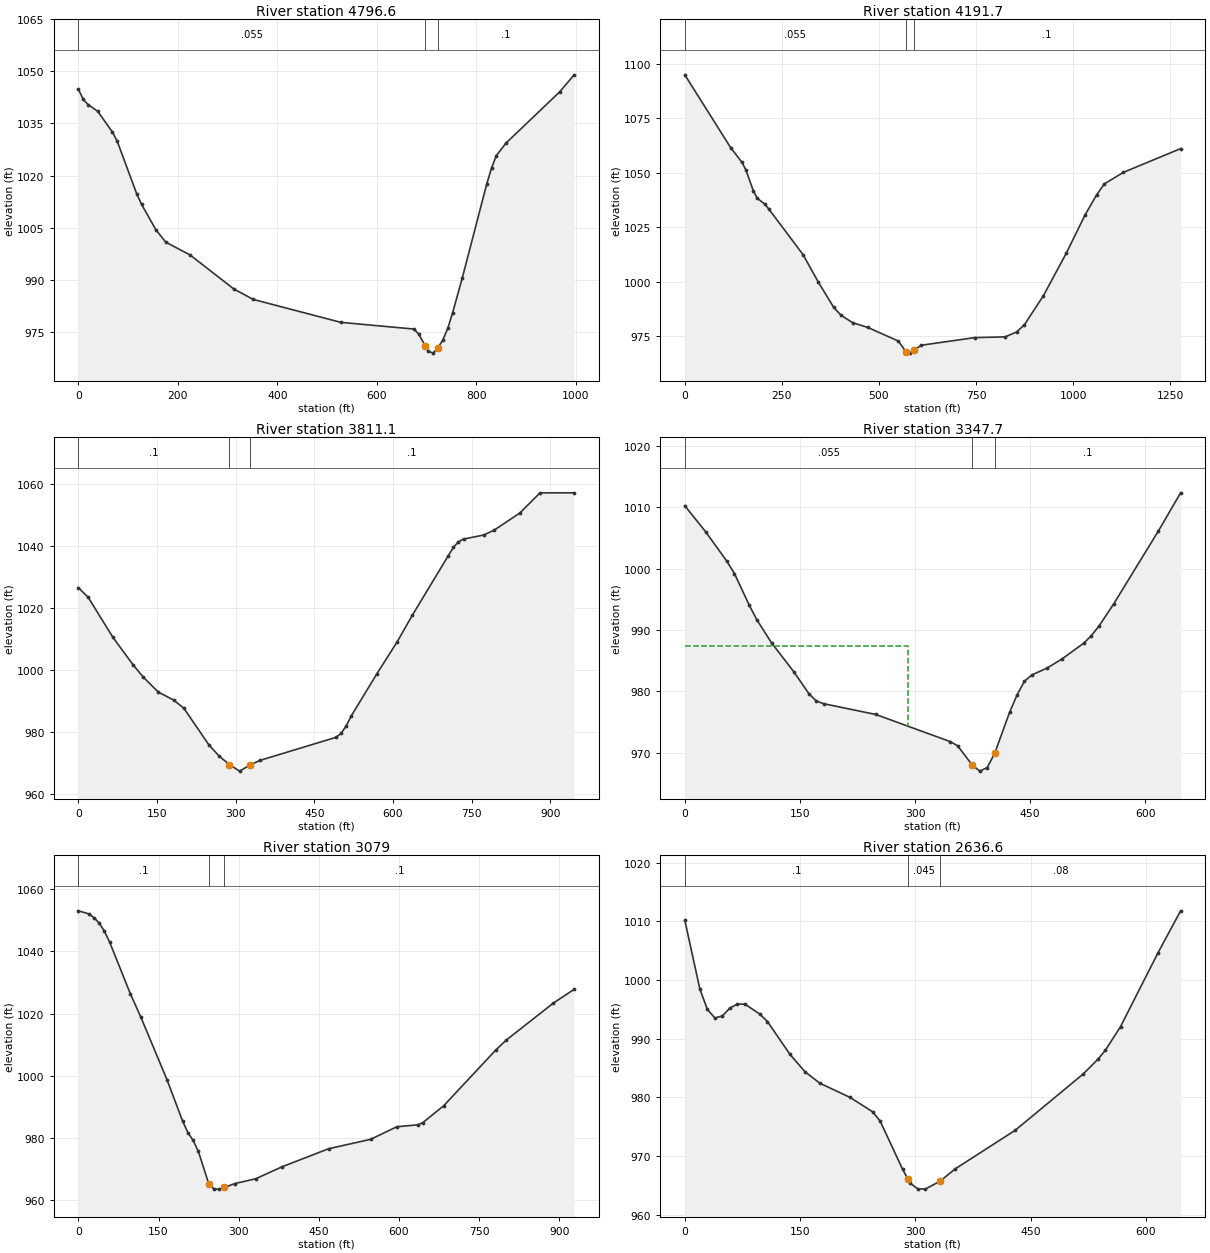
Type RM Length L Ch R = 1 ,4796.6  ,624.2,604.9,585.6
XS GIS Cut Line= 2
     1774502.305      322928.004     1774911.159      323836.858
#Sta/Elev= 30
       0 1044.87     9.8 1041.97    19.5 1040.44    39.1 1038.48    68.4 1032.54
    78.2 1029.87   117.2 1014.79     127 1011.71   156.3 1004.27   175.9 1000.78
   224.7   997.1   312.6   987.3   351.7  984.29   527.6  977.69   674.2  975.76
   683.9  974.37   697.6  970.81   703.5  969.34   713.2  968.82     723  970.43
   732.8  972.62   742.6  975.99   752.3  980.46   771.9  990.57   820.7 1017.45
   830.5 1022.14   840.3 1025.76   859.8 1029.37   967.3 1044.08   996.6 1049.01
#Mann= 3 , 0 , 0
       0    .055       0   697.6    .045       0     723      .1       0
Bank Sta=697.6,723
XS Rating Curve= 0 ,0
Exp/Cntr=0.3,0.1

Type RM Length L Ch R = 1 ,4191.7  ,401.2,380.6,358.1
XS GIS Cut Line= 2
     1773679.388      323566.025     1774900.742       323938.42
#Sta/Elev= 30
       0 1094.94   117.9 1061.55   147.3 1054.74   157.2 1051.34   176.8 1041.53
   186.6 1038.27   206.3 1035.53   216.1 1033.38   304.5 1012.37   343.8  999.78
   383.1  988.26   402.7  984.47   432.2  981.12   471.5  978.91     550  972.68
   569.7  967.75   579.5  967.14   589.3   968.4     609  970.77   746.5  974.26
     825   974.6   854.5  976.85   874.2  980.08   923.3  993.44   982.2 1012.95
  1031.3 1030.77  1060.8 1039.89  1080.4 1044.85  1129.5 1050.15  1276.9 1061.06
#Mann= 3 , 0 , 0
       0    .055       0   569.7    .045       0   589.3      .1       0
Bank Sta=569.7,589.3
XS Rating Curve= 0 ,0
Exp/Cntr=0.3,0.1

Type RM Length L Ch R = 1 ,3811.1  ,440.7,463.4,487.2
XS GIS Cut Line= 4
     1774148.919       324223.62     1774215.713      324171.251
     1774551.784       323894.15     1774900.742      323982.691
#Sta/Elev= 30
       0 1026.53    18.9 1023.34      66 1010.47   104.2 1001.66   123.6  997.71
   152.6  992.82   181.7  990.27     201  987.67   249.4  975.71   268.8  972.16
   288.2  969.45   307.5  967.35   326.9  969.28   346.2   970.8   491.4  978.25
   501.1  979.55   510.8   981.9   520.4  985.13   569.1  998.67     608 1009.03
   637.2 1017.69   705.3 1036.74   715.1 1039.44   724.8 1041.26   734.5 1042.15
   773.4 1043.48   792.9 1045.03   841.6 1050.51   880.5 1057.06   945.5 1057.06
#Mann= 3 , 0 , 0
       0      .1       0   288.2    .045       0   326.9      .1       0
Bank Sta=288.2,326.9
XS Rating Curve= 0 ,0
Exp/Cntr=0.3,0.1

Type RM Length L Ch R = 1 ,3347.7  ,272.5,268.7,264.8
XS GIS Cut Line= 3
     1774216.454      324204.349     1774259.088      324219.623
     1774818.586      324438.129
#Sta/Elev= 30
       0 1010.24    27.2 1005.99      55 1001.16    64.7  999.18      84  994.03
    93.7   991.7   113.1  987.89   142.2  983.16   161.5  979.65   171.2  978.44
   180.9  977.99   248.7  976.24   345.6  971.83   355.3  971.15   374.7  967.97
   384.4  967.01     394   967.6   403.7  969.91   423.1  976.59   432.8  979.42
   442.5  981.67   452.2  982.68   471.6  983.78   490.9  985.24     520  987.88
   529.7   989.1   539.4  990.61   558.8  994.26   616.9 1006.12   645.9 1012.34
#Mann= 3 , 0 , 0
       0    .055       0   374.7    .045       0   403.7      .1       0
#XS Ineff= 2 , 0
           290.3  987.45
Permanent Ineff=
       F       F
Bank Sta=374.7,403.7
XS Rating Curve= 0 ,0
Exp/Cntr=0.3,0.1

Type RM Length L Ch R = 1 ,3079    ,428,442.4,456.6
XS GIS Cut Line= 2
     1774110.889      324428.013     1775007.452      324666.377
#Sta/Elev= 30
       0 1053.06    19.5 1052.09    29.3 1050.86    39.1 1049.12    48.8  1046.5
    58.6    1043    97.6 1026.29   117.2 1018.79     166  998.72   195.3  985.37
   205.1  981.73   214.8  979.24   224.6  975.72   244.1  965.23   253.9   963.6
   263.7  963.58   273.4  964.12     293  965.37     332  966.92   380.8  970.74
   468.7  976.59   546.9  979.59   595.7  983.63   634.8  984.25   644.5  984.95
   683.6  990.39   781.2 1008.33   800.8 1011.52   888.6 1023.37   927.7 1027.82
#Mann= 3 , 0 , 0
       0      .1       0   244.1    .045       0   273.4      .1       0
Bank Sta=244.1,273.4
XS Rating Curve= 0 ,0
Exp/Cntr=0.3,0.1

Type RM Length L Ch R = 1 ,2636.6  ,290.9,290.3,289.6
XS GIS Cut Line= 2
     1773994.374      324694.142     1774451.868      325148.894
#Sta/Elev= 30
       0 1010.18    19.6  998.46    29.3     995    39.1  993.52    48.9  993.87
    58.6  995.21    68.4  995.88    78.2  995.88    97.7  994.18   107.5  992.92
   136.8  987.33   156.4  984.36   175.9  982.39     215  979.99   244.3  977.55
   254.1  975.97   283.4  967.74   290.4  966.04   293.2  965.36     303  964.42
   312.8  964.36   332.3  965.73   351.8  967.81     430   974.4     518  983.94
   537.6   986.5   547.3  988.04   566.9  992.05   615.7 1004.64   645.1 1011.78
#Mann= 3 , 0 , 0
       0      .1       0   290.4    .045       0   332.3     .08       0
Bank Sta=290.4,332.3
XS Rating Curve= 0 ,0
Exp/Cntr=0.3,0.1

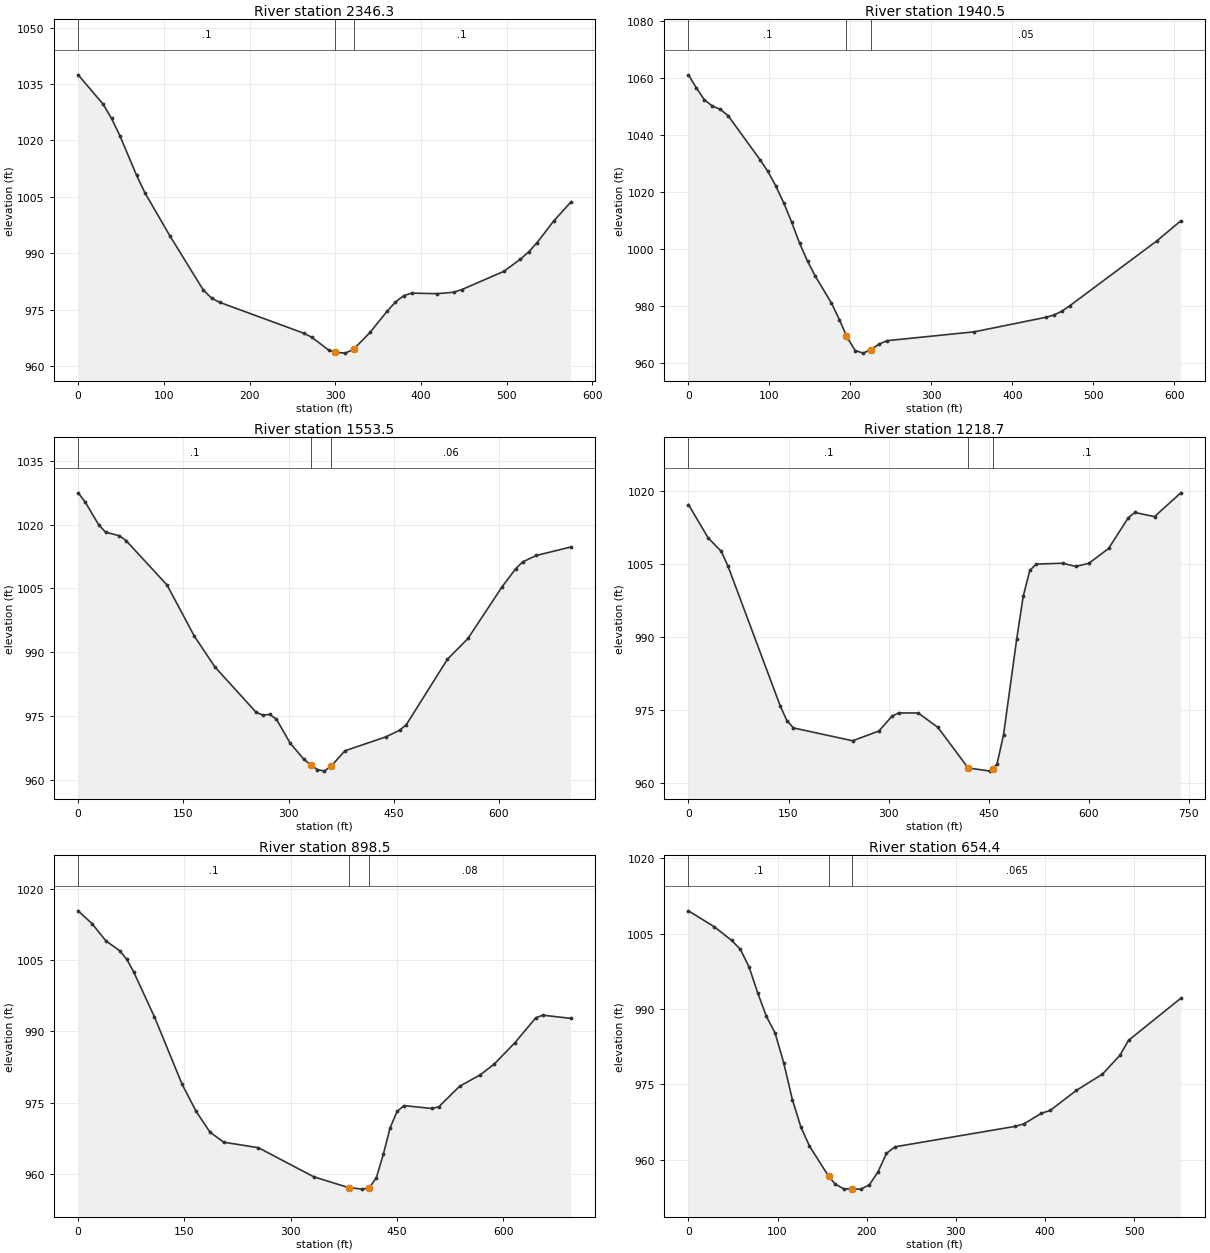
Type RM Length L Ch R = 1 ,2346.3  ,408.3,405.8,403
XS GIS Cut Line= 2
     1773808.115      324864.791     1774196.899      325287.609
#Sta/Elev= 30
       0 1037.46    29.2 1029.62    38.9 1025.88    48.7 1021.24    68.2  1010.7
    77.9 1006.05   107.1  994.58     146  980.18   155.8  977.99   165.5  976.87
   262.9  968.72   272.6  967.61   292.1  964.22  299.17  963.64   311.5  963.39
   321.3   964.4   340.7  968.95   360.2  974.48     370  976.93   379.7  978.69
   389.4  979.36   418.6  979.21   438.1   979.6   447.8  980.32   496.5  985.14
     516  988.39   525.7  990.37   535.4  992.79   554.9  998.59   574.4  1003.5
#Mann= 3 , 0 , 0
       0      .1       0  299.17    .045       0   321.3      .1       0
Bank Sta=299.17,321.3
XS Rating Curve= 0 ,0
Exp/Cntr=0.3,0.1

Type RM Length L Ch R = 1 ,1940.5  ,388.3,387,382.9
XS GIS Cut Line= 2
     1773528.576      325167.344     1773995.614      325556.758
#Sta/Elev= 30
       0 1061.12     9.8 1056.54    19.6 1052.36    29.4  1050.2    39.2 1049.03
      49 1046.77    88.3 1031.37    98.1  1027.2   107.9  1022.1   117.7 1016.16
   127.5 1009.36   137.3 1001.98   147.1  995.65   156.9  990.34   176.5  981.04
   186.4   975.2     195  969.57   196.2  968.79     206  964.32   215.8   963.4
   225.6  964.67   235.4  966.55   245.2  967.77   353.1  970.89   441.4  975.98
   451.2  976.76     461  978.09   470.8  979.99   578.7 1002.85   608.1 1009.86
#Mann= 3 , 0 , 0
       0      .1       0     195    .045       0   225.6     .05       0
Bank Sta=195,225.6
XS Rating Curve= 0 ,0
Exp/Cntr=0.3,0.1

Type RM Length L Ch R = 1 ,1553.5  ,325.5,334.8,346.9
XS GIS Cut Line= 2
     1773280.766      325500.774     1773914.857      325801.718
#Sta/Elev= 30
       0 1027.52     9.8 1025.41    29.2 1020.03      39 1018.26    58.5 1017.43
    68.2 1016.29   126.7 1005.82   165.7  993.76     195  986.52   253.5  975.89
   263.2  975.19     273  975.35   282.7  974.22   302.2  968.59   321.7   964.8
   331.4  963.48   341.2  962.37   350.9     962   360.7  963.16   380.2  966.78
   438.7  970.07   458.2  971.62   467.9  972.96   526.4  988.33   555.7  993.23
   604.4 1005.41   623.9 1009.67   633.6 1011.25   653.1 1012.77   701.9 1014.75
#Mann= 3 , 0 , 0
       0      .1       0   331.4    .045       0   360.7     .06       0
Bank Sta=331.4,360.7
XS Rating Curve= 0 ,0
Exp/Cntr=0.3,0.1

Type RM Length L Ch R = 1 ,1218.7  ,309.4,320.2,331
XS GIS Cut Line= 2
     1773214.566      325526.776     1773582.136      326166.732
#Sta/Elev= 30
       0 1017.16    29.5 1010.32    49.2 1007.55      59 1004.62   137.8  975.76
   147.6  972.82   157.4  971.32     246  968.68   285.4  970.67     305  973.71
   314.9  974.39   344.4  974.38   373.9  971.43  419.23   963.1   452.6  962.45
  456.43  962.98   462.5  963.88   472.3  969.91     492  989.51   501.8  998.35
   511.7 1003.64   521.5 1004.94   560.9 1005.11   580.6 1004.45   600.2  1005.1
   629.8 1008.14   659.3 1014.45   669.1 1015.53   698.6 1014.68     738 1019.56
#Mann= 3 , 0 , 0
       0      .1       0  419.23    .045       0  456.43      .1       0
Bank Sta=419.23,456.43
XS Rating Curve= 0 ,0
Exp/Cntr=0.3,0.1

Type RM Length L Ch R = 1 ,898.5   ,261.1,244.1,226
XS GIS Cut Line= 2
     1773105.152      325548.641     1773137.045      326242.983
#Sta/Elev= 30
       0 1015.37    19.6 1012.67    39.2 1009.04    58.7 1006.96    68.5  1005.2
    78.3 1002.54   107.7  993.04   146.8  978.84   166.4  973.19     186  968.79
   205.6  966.66   254.5   965.5   332.8  959.36   381.8   957.1   401.4  956.78
   411.2  957.09     421  959.17   430.8   964.1   440.5   969.7   450.3  973.16
   460.1  974.36   499.3  973.76   509.1   974.1   538.4  978.42   567.8  980.86
   587.4   983.1   616.8  987.64   646.1  992.86   655.9   993.4   695.1  992.74
#Mann= 3 , 0 , 0
       0      .1       0   381.8    .045       0   411.2     .08       0
Bank Sta=381.8,411.2
XS Rating Curve= 0 ,0
Exp/Cntr=0.3,0.1

Type RM Length L Ch R = 1 ,654.4   ,248.3,255.9,263.2
XS GIS Cut Line= 4
     1772766.823      325855.955     1772848.203      325939.505
     1773001.198      326084.905      1773102.11      326285.643
#Sta/Elev= 30
       0 1009.54    29.2 1006.34    48.6 1003.63    58.3 1001.86      68  998.36
    77.8  993.15    87.5  988.49    97.2   985.2   106.9  979.25   116.6  971.94
   126.2  966.44   135.8  962.68   157.3  956.65   164.6  955.11   174.2  954.16
   183.8   954.1   193.4   954.1     203  954.96   212.6  957.51   222.2  961.23
   231.8  962.53   366.8  966.61   376.5  967.11   396.1  969.22   405.8  969.77
   435.2  973.77   464.5  977.01     484  980.73   493.8  983.75   552.4  992.12
#Mann= 3 , 0 , 0
       0      .1       0   157.3    .045       0   183.8    .065       0
Bank Sta=157.3,183.8
XS Rating Curve= 0 ,0
Exp/Cntr=0.3,0.1

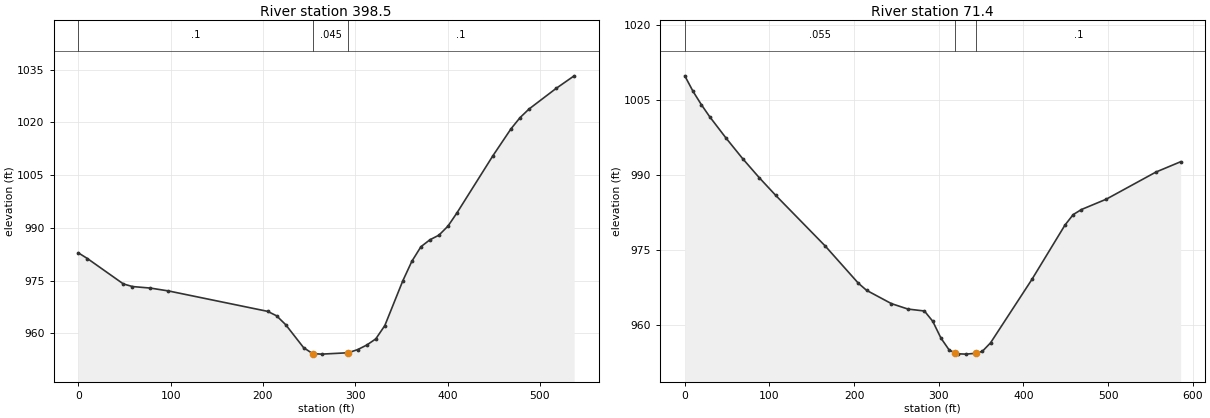
Type RM Length L Ch R = 1 ,398.5   ,305.9,327.1,346.6
XS GIS Cut Line= 2
     1772689.744      325973.669     1772941.383      326448.137
#Sta/Elev= 30
       0   982.9     9.8  981.29    48.8  974.06    58.6  973.32    78.1  972.88
    97.6  972.07   205.1  966.26   214.8  964.99   224.6  962.48   244.1  955.92
   253.9  954.24   263.6   954.1   292.4954.4929   302.7   955.4   312.5  956.69
   322.2  958.43     332  962.22   351.5  974.96   361.3  980.51   371.1  984.64
   380.8  986.61   390.6  987.93   400.4   990.5   410.1  994.25   449.2 1010.56
   468.7 1018.18   478.5 1021.36   488.2  1023.8   517.5 1029.65   537.1 1033.24
#Mann= 3 , 0 , 0
       0      .1       0   253.9    .045       0   292.4      .1       0
Bank Sta=253.9,292.4
XS Rating Curve= 0 ,0
Exp/Cntr=0.3,0.1

Type RM Length L Ch R = 1 ,71.4    ,63.8,71.4,78.6
XS GIS Cut Line= 2
     1772672.673      325861.577     1772420.785      326390.267
#Sta/Elev= 30
       0 1009.85     9.8 1006.72    19.5 1004.09    29.3 1001.68    48.8  997.36
    68.3  993.27    87.8  989.47   107.4   985.9   165.9  975.75     205   968.3
   214.7  966.88     244  964.22   263.5  963.13     283  962.74   292.8  960.69
   302.6  957.29   312.3  954.91  319.59  954.34   322.1  954.17   331.9   954.1
  343.95  954.27   351.4  954.66   361.1  956.36   409.9  969.05     449  979.95
   458.7  982.05   468.5  983.07   497.8  985.14   556.4  990.57   585.6  992.64
#Mann= 3 , 0 , 0
       0    .055       0  319.59    .045       0  343.95      .1       0
Bank Sta=319.59,343.95
XS Rating Curve= 0 ,0
Exp/Cntr=0.3,0.1

Chan Stop Cuts=-1
Use User Specified Reach Order=0
Composite Channel Slope=5